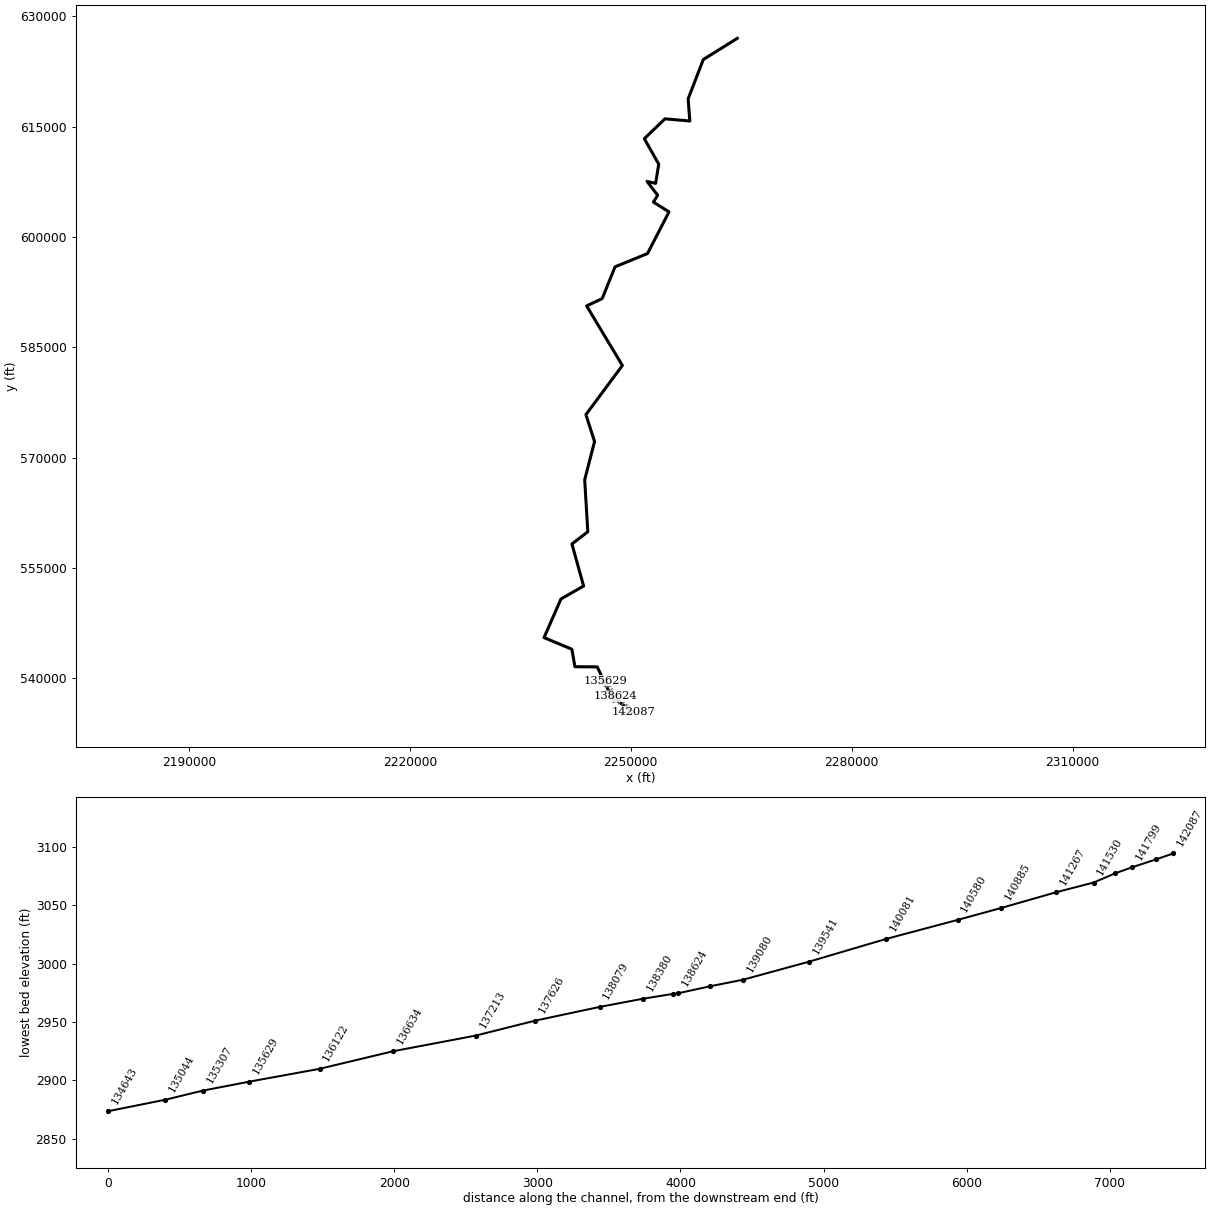
--- TYGVRV2.prj (project) ---

Proj Title=TYGVRV2
Current Plan=p01
Default Exp/Contr=0,0
English Units
Geom File=g01
Flow File=f01
Plan File=p01
BEGIN DESCRIPTION:
----------MODEL BY WOOD PLC 2022----------
AFH study
Randolph County, WV
HEC-RAS Version: RAS 6.2
Vertical Datum: NAVD88
Projection: NAD 1983 StatePlane West Virginia S FIPS 4702 (US Feet)
Terrain: 1-meter LIDAR (FEMA Region III 3DEP collected 2016-2018)
Land Use: 2019 NLCD
Hydrologic Method:
WV SIR2010-5033 regression equations
Additional Model Notes:
5 shared XS from Pocahontas County on the upstream extent
END DESCRIPTION:
DSS Export Rating Curves= 0
DSS Export Rating Curve Sorted= 0
DSS Export Volume Flow Curves= 0
DXF OffsetX= 0
DXF OffsetY= 0
DXF ScaleX= 0
DXF ScaleY= 0

--- TYGVRV2.p01 (plan) ---

Plan Title=Floodplain
Program Version=6.20
Short Identifier=Floodplain
Geom File=g01
Flow File=f01
Subcritical Flow
K Sum by GR= 0
Std Step Tol= 0.01
Critical Tol= 0.01
Num of Std Step Trials= 20
Max Error Tol= 0.3
Flow Tol Ratio= 0.001
Split Flow NTrial= 30
Split Flow Tol= 0.02
Split Flow Ratio= 0.02
Log Output Level= 0
Friction Slope Method= 1
Unsteady Friction Slope Method= 2
Unsteady Bridges Friction Slope Method= 1
Parabolic Critical Depth
Global Vel Dist= 0 , 0 , 0
Global Log Level= 0
CheckData=True
Encroach Param=-1 ,0,0, 0
Mapping Interval=1HOUR
Computation Time Step Use Courant=        0
Computation Time Step Use Time Series=    0
Computation Time Step Count To Double=0
Computation Time Step Max Doubling=0
Computation Time Step Max Halving=0
Computation Time Step Residence Courant=0
Run HTab= 0
Run UNet= 0
Run Sediment= 0
Run PostProcess= 0
Run WQNet= 0
Run RASMapper=-1
UNET Theta= 0
UNET Theta Warmup= 0
UNET ZTol= 0
UNET ZSATol= 0
UNET MxIter= 0
UNET Max Iter WO Improvement= 0
UNET MaxInSteps= 0
UNET DtIC= 0
UNET DtMin= 0
UNET MaxCRTS= 0
UNET WFStab= 0
UNET SFStab= 0
UNET WFX= 1
UNET SFX= 1
UNET Gravity=32.174
UNET 1D Methodology=Finite Difference
UNET DSS MLevel= 1
UNET Pardiso=0
UNET DZMax Abort= 0
UNET Use Existing IB Tables= 0
UNET Froude Reduction=False
UNET Froude Limit= 0
UNET Froude Power= 0
UNET D1 Cores= 0
UNET WindReference=Eulerian
UNET WindDragFormulation=Hsu (1988)
UNET D2 Coriolis=0
UNET D2 Cores= 0
UNET D2 Theta= 1
UNET D2 Theta Warmup= 1
UNET D2 Z Tol= 0.01
UNET D2 Volume Tol= 0.01
UNET D2 Max Iterations= 20
UNET D2 Equation= 0
UNET D2 RampUpFraction=0.1
UNET D2 TimeSlices= 1
UNET D2 Turbulence Formulation=Non-Conservative (original)
UNET D2 Eddy Viscosity=0.3
UNET D2 Transverse Eddy Viscosity=0.1
UNET D2 Smagorinsky Mixing=0
UNET D2 BCVolumeCheck=0
UNET D2 Cores=0
UNET D2 SolverType=PARDISO (Direct)
UNET D2 Minimum Iterations= 2147483647
UNET D2 Maximum Iterations= 2147483647
UNET D2 Restart Number= 10
UNET D2 Relaxation Coeff=1.3
UNET D2 SOR Precondition Iterations= 10
UNET D2 ILUT Maximum Fill= 8
UNET D2 ILUT Tolerance=1E-08
UNET D1D2 MaxIter= 0
UNET D1D2 ZTol=0.01
UNET D1D2 QTol=0.1
UNET D1D2 MinQTol=1
Write IC File= 0
Write IC File at Fixed DateTime=0
Write IC File at Sim End=0
Echo Input=False
Echo Parameters=False
Echo Output=False
Write Detailed= 0
HDF Write Warmup=0
HDF Write Time Slices=0
HDF Flush=0
HDF Compression= 1
HDF Chunk Size= 1
HDF Spatial Parts= 1
HDF Use Max Rows=0
HDF Fixed Rows= 1
Calibration Method= 0
Calibration Iterations= 20
Calibration Max Change=0.05
Calibration Tolerance=0.2
Calibration Maximum=1.5
Calibration Minimum=0.5
Calibration Optimization Method= 1
WQ AD Non Conservative
WQ ULTIMATE=-1
WQ Max Comp Step=1HOUR
WQ Output Interval=15MIN
WQ Output Selected Increments= 0
WQ Output face flow=0
WQ Output face velocity=0
WQ Output face area=0
WQ Output face dispersion=0
WQ Output cell volume=0
WQ Output cell surface area=0
WQ Output cell continuity=0
WQ Output cumulative cell continuity=0
WQ Output face conc=0
WQ Output face dconc_dx=0
WQ Output face courant=0
WQ Output face peclet=0
WQ Output face adv mass=0
WQ Output face disp mass=0
WQ Output cell mass=0
WQ Output cell source sink temp=0
WQ Output nsm pathways=0
WQ Output nsm derived pathways=0
WQ Create Restart=0
WQ Fixed Restart=0
WQ System Summary=0
WQ Write To DSS=0
Sorting and Armoring Iterations= 10
XS Update Threshold= 0.02
Bed Roughness Predictor= 0
Hydraulics Update Threshold= 0.02
Energy Slope Method= 1
Volume Change Method= 1
Sediment Retention Method= 0
Sediment TS Multiplier= 1
Warm Up Method= 0
XS Weighting Method= 0
Number of US Weighted Cross Sections= 1
Number of DS Weighted Cross Sections= 1
Upstream XS Weight=0
Main XS Weight=1
Downstream XS Weight=0
Number of DS XS's Weighted with US Boundary= 1
Upstream Boundary Weight= 1
Weight of XSs Associated with US Boundary= 0
Number of US XS's Weighted with DS Boundary= 1
Downstream Boundary Weight= 0.5
Weight of XSs Associated with DS Boundary= 0.5
Percentile Method= 0
Sediment Output Level= 3
Mass or Volume Output= 0
Output Increment Type= 1
Profile and TS Output Increment= 1
Transport Output Increment 1
XS Output Flag= 0
XS Output Increment= 10
Read HDF5 Sediment Hotstart= 0
Sediment Hotstart Type= 0
Write Gradation File= 0
Read Gradation Hotstart= 0
Write HDF5 File= 1
Write Binary Output= 1
Write DSS Sediment File= 0
DSS Sediment Output Type= 1
SV Curve= 0
Specific Gage Flag= 0
Subcell Erosion Methods= 0
Subcell Deposition Methods= 0
Advection Scheme= 1
Matrix Solver= 0
Implicit Weighting Factor= 1
Maximum Outer Loop Convergence Iterations= 5
Convergence Maximum Absolute= 0.001
Convergence RMSE= 0.0001
Grain Fractions Max Abs Error= 0.001
Max Subgrid Regions= 1
Max Subgrid Length Scale= 3.402823E+38
Initial Layer Thickness= 3.402823E+38
Min Layer Thickness= 3.402823E+38
Max Layer Thickness= 3.402823E+38
Number of Layers= 5

--- TYGVRV2.f01 (steady flow) ---

Flow Title=Flow
Program Version=6.20
Number of Profiles= 6
Profile Names=01pct,10pct,04pct,02pct,0_2pct,01plus
River Rch & RM=TYGVRV2,Main            ,142087
     761     406     538     646    1057    1125
River Rch & RM=TYGVRV2,Main            ,138079
     961     518     682     817    1329    1421
River Rch & RM=TYGVRV2,Main            ,133011
    1326     724     948    1131    1823    1961
River Rch & RM=TYGVRV2,Main            ,131607
    1344     734     961    1146    1848    1988
River Rch & RM=TYGVRV2,Main            ,129811
    1793     990    1289    1533    2451    2651
River Rch & RM=TYGVRV2,Main            ,124122
    2154    1198    1554    1845    2935    3185
River Rch & RM=TYGVRV2,Main            ,123136
    2382    1330    1723    2042    3240    3524
River Rch & RM=TYGVRV2,Main            ,115682
    3092    1744    2247    2657    4185    4573
River Rch & RM=TYGVRV2,Main            ,108195
    3687    2094    2689    3172    4973    5453
River Rch & RM=TYGVRV2,Main            ,97587
    4525    2590    3314    3901    6080    6692
River Rch & RM=TYGVRV2,Main            ,94240
    5510    3178    4051    4758    7376    8149
River Rch & RM=TYGVRV2,Main            ,88700
    5635    3254    4146    4867    7541    8335
River Rch & RM=TYGVRV2,Main            ,84830
    6834    3976    5047    5913    9113   10108
River Rch & RM=TYGVRV2,Main            ,66849
    8004    4684    5929    6934   10640   11837
River Rch & RM=TYGVRV2,Main            ,63528
    9792    5776    7283    8498   12968   14482
River Rch & RM=TYGVRV2,Main            ,54290
   10781    6383    8035    9365   14253   15945
River Rch & RM=TYGVRV2,Main            ,30802
   12575    7490    9400   10937   16576   18598
River Rch & RM=TYGVRV2,Main            ,17795
   14225    8513   10660   12386   18709   21039
Boundary for River Rch & Prof#=TYGVRV2,Main            , 1
Up Type= 0
Dn Type= 3
Dn Slope=0.00352
Boundary for River Rch & Prof#=TYGVRV2,Main            , 2
Up Type= 0
Dn Type= 3
Dn Slope=0.00352
Boundary for River Rch & Prof#=TYGVRV2,Main            , 3
Up Type= 0
Dn Type= 3
Dn Slope=0.00352
Boundary for River Rch & Prof#=TYGVRV2,Main            , 4
Up Type= 0
Dn Type= 3
Dn Slope=0.00352
Boundary for River Rch & Prof#=TYGVRV2,Main            , 5
Up Type= 0
Dn Type= 3
Dn Slope=0.00352
Boundary for River Rch & Prof#=TYGVRV2,Main            , 6
Up Type= 0
Dn Type= 3
Dn Slope=0.00352
DSS Import GetInterval= 0
DSS Import GetPeak= 0
DSS Import FillOption= 0

--- TYGVRV2.g01 (geometry) ---

Geom Title=Geometry
Program Version=6.20

River Reach=TYGVRV2         ,Main
Reach XY= 30
2250353.30807859535340.1945169122247341.88400003537579.506999999
2245445.58300002541545.9600000082242417.56478882541566.074006334
2242006.13900001543942.3170000312238224.00099999545525.410000011
2240522.86300004550781.0649999982243599.25000001552533.862000018
2242012.69700003558251.9839999972244168.25500003559917.391000018
2243743.67100003566974.945999995     2245085.005572186.348000005
2243909.59400004575836.4200000172248865.40700004 582522.14200002
2244007.41300003590621.600000009     2246124.315591617.094999999
2247867.12900001595933.085000008     2252273.854597734.235000014
2255197.06900001603403.163000017     2253077.727604734.498999998
2253654.56600001      605667.6842252215.92300002607548.958000004
2253371.69000001607278.7489999982253804.75100003      609884.838
     2251845.877613352.0090000032254645.03500003616055.273000002
2258023.78600003615757.7860000132257796.06500001618770.757000014
2259853.46200004624114.4399999982264471.55600001626996.812000006

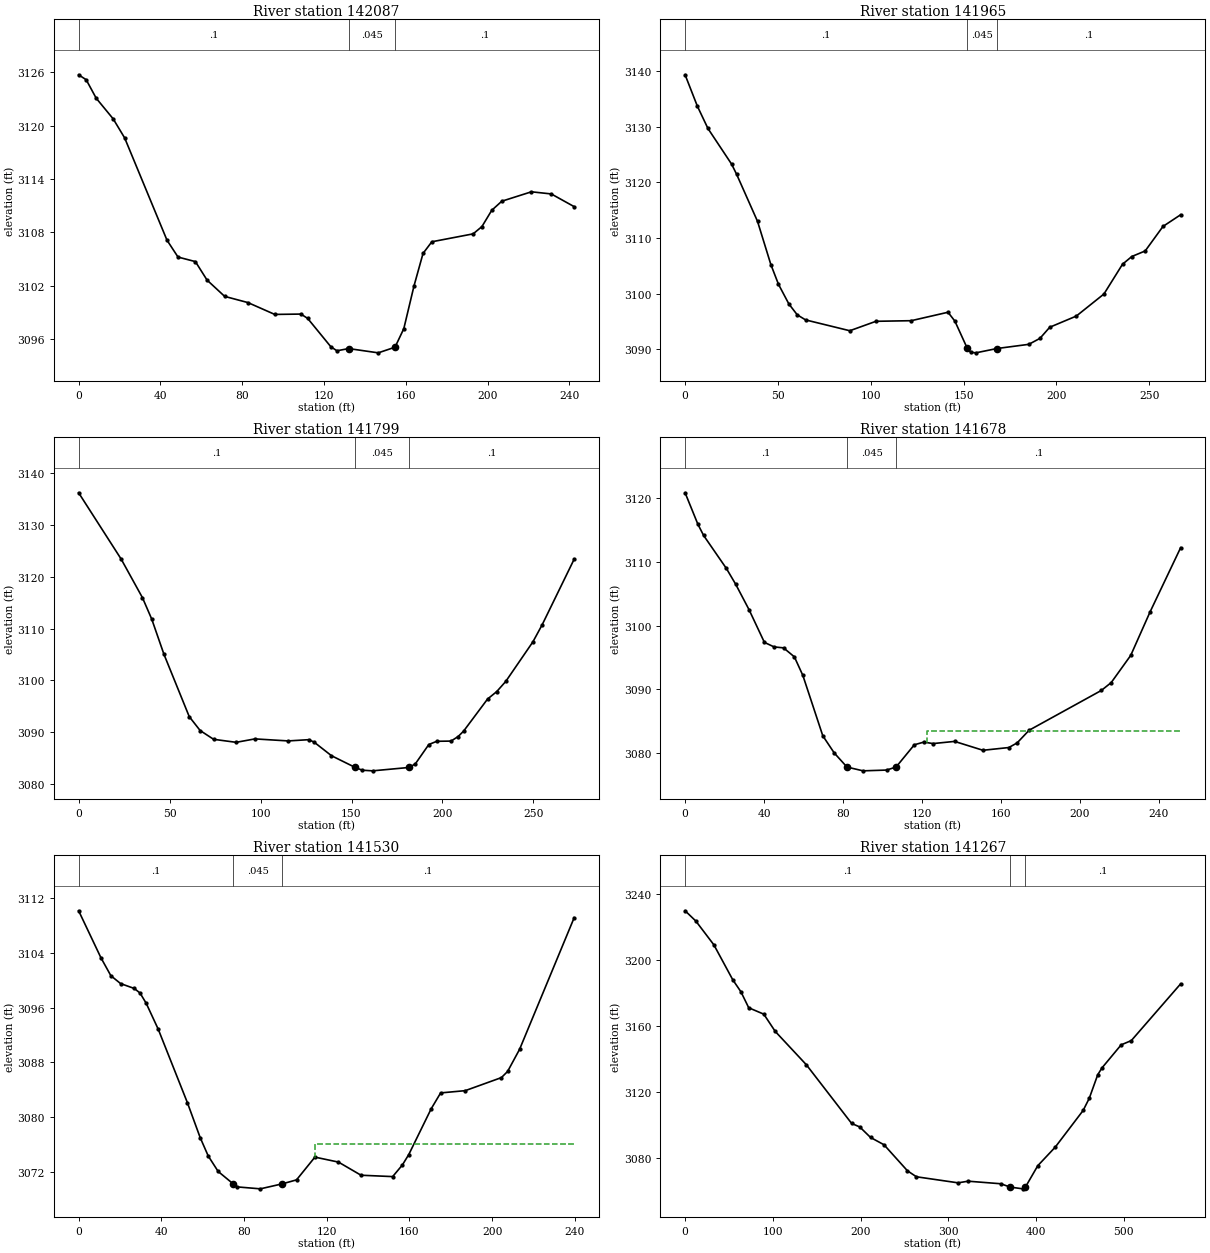
Type RM Length L Ch R = 1 ,142087  ,122.3,122.3,122.3
XS GIS Cut Line= 4
2250269.92578645535223.3268213792250328.29408546535299.654597014
2250371.69615396535369.995880442 2250407.6151072535422.377687249
#Sta/Elev= 30
       0 3125.72     3.7 3125.16     8.6 3123.08    16.9 3120.76    22.5 3118.62
    43.2 3107.12    48.6 3105.22    57.1 3104.71    62.8 3102.63    71.4  3100.8
    82.8  3100.1    95.9 3098.77   108.7 3098.81     112 3098.32   123.3 3095.14
   126.3 3094.68     132 3094.93   146.5 3094.45   154.73095.084     159 3097.17
     164 3101.99   168.4 3105.63   172.7 3106.94   192.9 3107.83   197.2 3108.65
     202 3110.48   206.9  3111.5   221.4 3112.56   231.1 3112.32   242.3 3110.89
#Mann= 3 ,-1,0
       0      .1       0     132    .045       0   154.7      .1       0
Bank Sta=132,154.7
XS Rating Curve= 0 ,0
Exp/Cntr=0.3,0.1

Type RM Length L Ch R = 1 ,141965  ,165.9,165.9,165.9
XS GIS Cut Line= 4
2250138.56288523535297.4169924792250227.87987656535387.795959212
2250280.57320751535432.4225566412250337.22977627535474.915475544
#Sta/Elev= 30
       0  3139.4     6.6 3133.75    12.3 3129.73    25.1 3123.28    27.8 3121.44
      39 3113.01    46.2 3105.21    50.3 3101.66    55.9 3098.12    60.4 3096.17
    64.9 3095.25    88.7  3093.3   102.8    3095   121.8 3095.11   141.6 3096.63
   145.3 3095.04     152 3090.12   153.8 3089.42   156.6 3089.32     168  3090.1
   185.1 3090.85   191.1 3091.92   196.4 3093.93   210.7 3095.94   225.6 3099.92
   235.6 3105.28   240.6 3106.67   247.8 3107.67   257.4 3112.09   266.9 3114.19
#Mann= 3 ,-1,0
       0      .1       0     152    .045       0     168      .1       0
Bank Sta=152,168
XS Rating Curve= 0 ,0
Exp/Cntr=0.3,0.1

Type RM Length L Ch R = 1 ,141799  ,121.4,121.4,121.4
XS GIS Cut Line= 4
 2250045.4323287535393.9418492682250129.24321959535497.208839832
2250172.64528809535575.0332385182250202.57774912535615.442060913
#Sta/Elev= 30
       0 3136.14    23.4 3123.36    35.1 3115.93    40.2  3111.8    46.9 3105.04
    60.8 3093.04    66.8 3090.36    74.2 3088.67    86.6 3088.09    96.9 3088.75
   115.2 3088.36   126.5  3088.6   129.4 3088.14     139 3085.51  152.033083.255
   155.9 3082.72   161.6  3082.6  181.763083.255   185.1 3083.95   192.5 3087.67
   196.9 3088.29   204.7 3088.33   208.6  3089.2   211.6 3090.24   224.8 3096.43
   229.8 3097.85   234.8 3099.82   249.7 3107.43   254.8 3110.72   272.4 3123.36
#Mann= 3 ,-1,0
       0      .1       0  152.03    .045       0  181.76      .1       0
Bank Sta=152.03,181.76
XS Rating Curve= 0 ,0
Exp/Cntr=0.3,0.1

Type RM Length L Ch R = 1 ,141678  ,147.9,147.9,147.9
XS GIS Cut Line= 5
2249984.07078358535500.2020859362250018.49311377 535549.59064664
2250060.39855921535616.9386839652250093.32426635535664.830621618
2250136.72633485535696.259705702
#Sta/Elev= 30
       0 3120.81     6.5 3115.87     9.4 3114.12    20.9 3108.97    25.6 3106.51
    32.4 3102.51    40.2 3097.38    45.1 3096.67    49.9 3096.52    55.4 3095.11
    59.7  3092.2    69.8 3082.75    75.6 3080.06   82.063077.853    90.2 3077.26
   102.1 3077.38  106.943077.854   116.2 3081.34     121 3081.76   125.7 3081.53
   136.6 3081.87     151 3080.48   164.1 3080.91   168.3 3081.63   174.4 3083.62
     211 3089.85     216 3091.08   225.9 3095.34   235.7 3102.15   251.2 3112.21
#Mann= 3 ,-1,0
       0      .1       0   82.06    .045       0  106.94      .1       0
#XS Ineff= 2 , 0
                          122.44         3083.55
Permanent Ineff=
       F       F
Bank Sta=82.06,106.94
XS Rating Curve= 0 ,0
Exp/Cntr=0.3,0.1

Type RM Length L Ch R = 1 ,141530  ,263,263,263
XS GIS Cut Line= 4
2249876.31392386535595.9859612412249906.24638489535643.877898894
 2249958.6281917535729.1854128392250000.53363715535801.023319318
#Sta/Elev= 30
       0 3110.16    10.8 3103.28    15.6 3100.66    20.3 3099.51    26.9  3098.8
    29.7 3098.13    32.7 3096.62    38.5 3092.84    52.6  3082.1    58.8 3076.98
    62.7 3074.29    67.5 3072.03   74.743070.223    76.8 3069.77    87.9 3069.49
   98.543070.224   105.4  3070.8   114.3 3074.13   125.7  3073.4   136.6 3071.48
   151.9 3071.28   156.6 3072.98   159.7 3074.51   170.5 3081.18   175.1 3083.52
     187 3083.85   204.5 3085.76   207.5 3086.66   213.3  3089.9   239.7 3109.15
#Mann= 3 ,-1,0
       0      .1       0   74.74    .045       0   98.54      .1       0
#XS Ineff= 2 , 0
                          114.14         3076.09
Permanent Ineff=
       F       F
Bank Sta=74.74,98.54
XS Rating Curve= 0 ,0
Exp/Cntr=0.3,0.1

Type RM Length L Ch R = 1 ,141267  ,381.9,381.9,381.9
XS GIS Cut Line= 4
2249604.88091086535537.8394302742249699.63062282535774.940384127
2249807.75409795535899.384383807 2249887.0746834536020.199278093
#Sta/Elev= 30
       0 3229.85    12.2 3223.64    32.8 3209.18    54.3 3188.01    63.6 3180.72
    72.5 3171.01    89.7 3167.12   102.7 3156.67   138.2 3136.42   189.8 3100.82
     199 3098.71   211.3 3092.34   226.7 3087.88   253.4 3072.09   263.6 3068.47
   311.1 3064.79   322.5 3065.79   359.8 3064.23  370.343062.218   384.9 3061.15
  387.813062.215   401.9 3075.18   421.8 3086.45   453.6 3108.71   460.6 3116.12
   470.2 3130.34     475 3134.49   496.9  3148.5   508.5  3151.1   564.7 3185.51
#Mann= 3 ,-1,0
       0      .1       0  370.34    .045       0  387.81      .1       0
Bank Sta=370.34,387.81
XS Rating Curve= 0 ,0
Exp/Cntr(USF)=0,0
Exp/Cntr=0.3,0.1

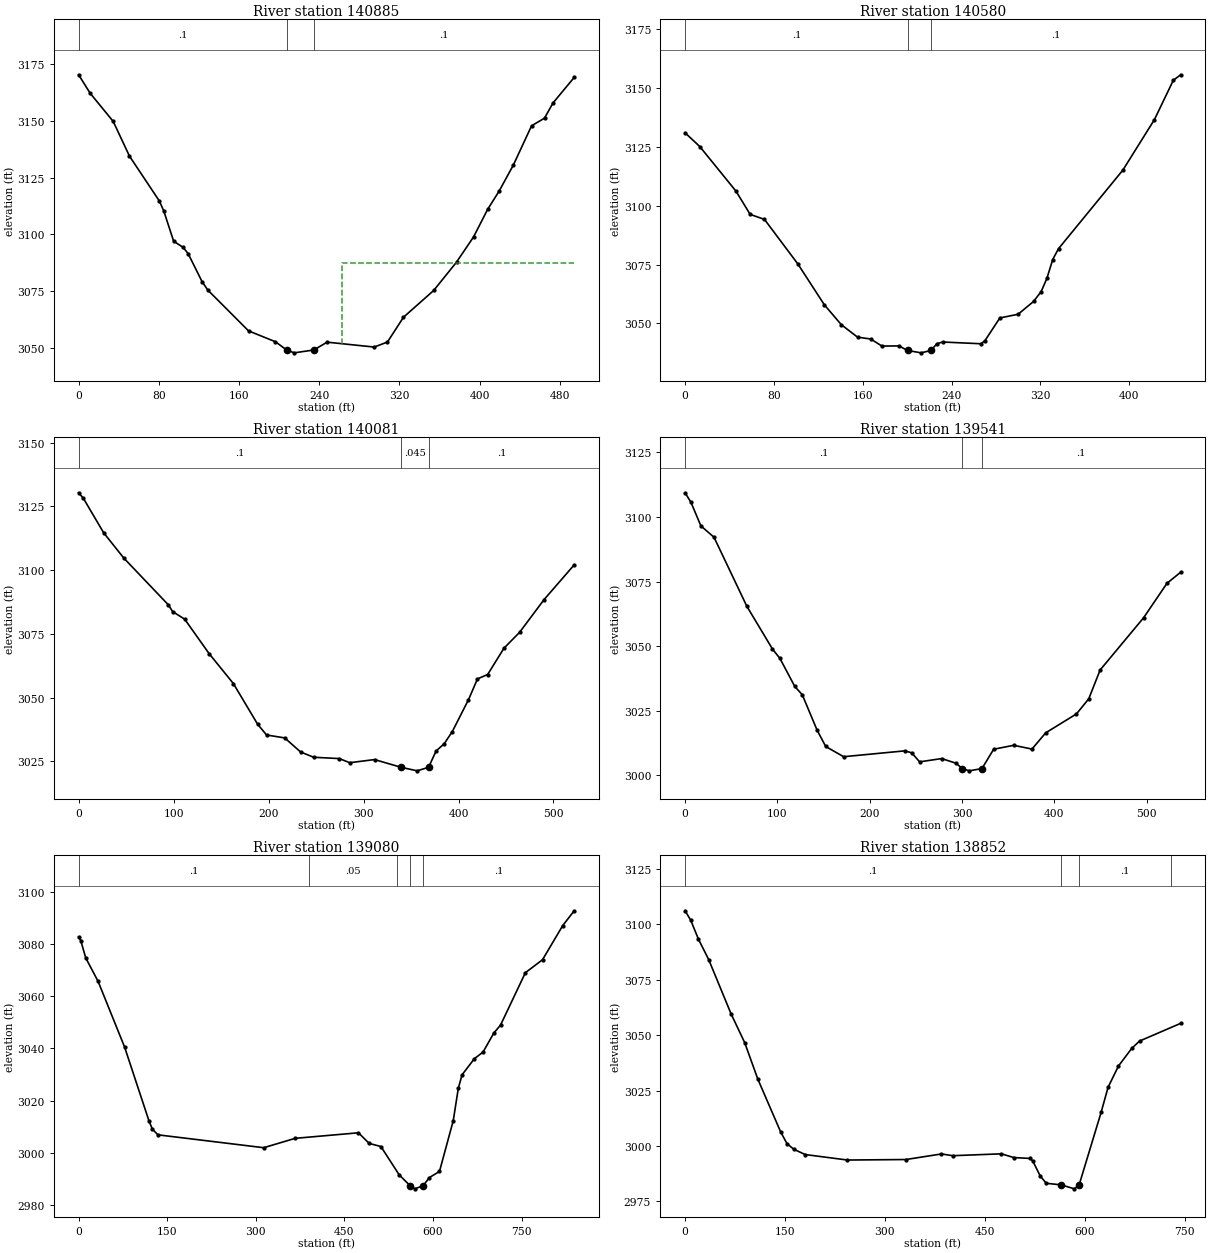
Type RM Length L Ch R = 1 ,140885  ,305.2,305.2,305.2
XS GIS Cut Line= 4
2249317.68746301535859.613505223 2249418.4966219536003.910133533
2249486.41802892536114.4856365682249628.12987441536238.915559183
#Sta/Elev= 30
       0 3170.36    11.5 3162.22    34.5 3149.79    50.7 3134.51    80.5 3114.72
    84.9 3110.36    94.8 3096.97   104.4 3094.19   109.3 3091.44   123.1 3079.19
   128.8 3075.45   169.5 3057.42   196.3 3052.63  207.593048.982   215.1 3047.73
  234.563048.982   247.9 3052.44   294.9 3050.28   308.1 3052.49   324.1 3063.43
   354.3 3075.26     377 3087.72     394 3098.84   408.1 3111.03   419.5 3119.04
   433.7 3130.53   451.9 3147.86   464.8 3151.23   473.3 3157.94   494.4 3169.18
#Mann= 3 ,-1,0
       0      .1       0  207.59    .045       0  234.56      .1       0
#XS Ineff= 2 , 0
                          262.82         3087.31
Permanent Ineff=
       F       F
Bank Sta=207.59,234.56
XS Rating Curve= 0 ,0
Exp/Cntr=0.3,0.1

Type RM Length L Ch R = 1 ,140580  ,498.3,498.3,498.3
XS GIS Cut Line= 4
2249123.77827811536118.8285570122249230.75257285536253.970282808
2249306.42385738536318.2262144852249440.83165617536429.716672477
#Sta/Elev= 30
       0 3130.93    13.2 3125.11    45.8 3106.18    58.6 3096.29    71.5 3094.15
   101.6 3075.21   125.4  3057.9   140.7 3049.45   155.3 3044.16   167.1 3043.37
   177.3 3040.37   192.7 3040.43  200.353038.498   212.5 3037.49  221.493038.498
   226.7 3041.34   231.9 3042.09   266.5 3041.35     270 3042.63   283.5 3052.31
   299.9 3053.87   313.8  3059.3   320.7 3063.51   325.9 3069.18   331.1 3077.13
   336.3 3081.72   394.3 3115.12   422.7 3136.55   439.7 3153.23   446.3 3155.58
#Mann= 3 ,-1,0
       0      .1       0  200.35    .045       0  221.49      .1       0
Bank Sta=200.35,221.49
XS Rating Curve= 0 ,0
Exp/Cntr=0.3,0.1

Type RM Length L Ch R = 1 ,140081  ,540.9,540.9,540.9
XS GIS Cut Line= 4
 2248818.7731873536340.5353075872248886.17420266 536521.36721808
2249006.13353111536671.5976638812249108.33469774536762.204272531
#Sta/Elev= 30
       0 3130.37       5 3128.19    26.3  3114.7    47.6 3104.72    94.6 3086.33
    98.9 3083.76   111.7 3080.74   137.3 3067.28   162.9  3055.5   188.5 3039.51
   197.9 3035.29     217 3034.15   233.7 3028.63   247.5 3026.55   274.6 3026.03
   285.4 3024.41   311.6 3025.64  339.493022.616   356.5 3021.22   368.53022.617
   376.4    3029     385 3031.88   393.5 3036.65   410.5 3049.13     420 3057.32
   430.7 3059.03   447.9 3069.38   464.3 3075.58   490.1 3088.44   521.8 3102.06
#Mann= 3 ,-1,0
       0      .1       0  339.49    .045       0   368.5      .1       0
Bank Sta=339.49,368.5
XS Rating Curve= 0 ,0
Exp/Cntr=0.3,0.1

Type RM Length L Ch R = 1 ,139541  ,460.3,460.3,460.3
XS GIS Cut Line= 4
2248366.69598793536519.4200420822248386.87474254536668.631700946
2248561.18050184536823.458019519 2248613.9317987536967.043802999
#Sta/Elev= 30
       0 3109.37     6.4 3105.64    17.1 3096.54    31.3 3092.15    66.9 3065.39
    94.6 3048.86   102.7 3045.21   118.8 3034.34   126.9 3031.14     143 3017.39
   152.3 3011.09   171.7 3007.13   237.9  3009.4   245.4 3008.65     254 3005.14
   277.9 3006.41   293.5  3004.6  300.163002.543   307.7 3001.66  321.533002.543
   334.2 3010.03   355.9 3011.55   375.7 3010.09   390.5 3016.37   423.9 3023.72
   437.2 3029.57   449.5 3040.73   496.5 3060.92   521.9  3074.3   536.7 3078.59
#Mann= 3 ,-1,0
       0      .1       0  300.16    .045       0  321.53      .1       0
Bank Sta=300.16,321.53
XS Rating Curve= 0 ,0
Exp/Cntr=0.3,0.1

Type RM Length L Ch R = 1 ,139080  ,228,228,228
XS GIS Cut Line= 4
2247688.66502397536715.6185614742247812.99189768536753.523234242
2248180.10854816537073.6621043052248283.42603462537270.300580118
#Sta/Elev= 30
       0 3082.64     3.7 3081.19      12 3074.62    32.9 3065.66    77.8 3040.51
   119.4 3012.06   124.9 3009.09   134.2  3006.9   313.4 3001.97   366.8 3005.56
   473.9 3007.68     492 3003.62   511.9 3002.42   542.9 2991.57  561.372987.429
   569.4 2986.23  583.372987.428   594.1 2990.56   611.1 2992.89   634.4  3012.3
     643 3024.71   649.3 3029.86   670.1 3036.01   684.9 3038.58   703.2 3045.88
   714.5 3048.89   756.6 3068.95   785.6 3073.91   819.9    3087   839.2 3092.64
#Mann= 5 ,-1,0
       0      .1       0  389.98     .05       0  539.98      .1       0
  561.37    .045       0  583.37      .1       0
Bank Sta=561.37,583.37
XS Rating Curve= 0 ,0
Exp/Cntr=0.3,0.1

Type RM Length L Ch R = 1 ,138852  ,228,228,228
XS GIS Cut Line= 4
2247559.61953815536822.0428615432247691.80903308 536907.08657602
2248002.33961023537221.4896462562248095.09545432537333.014890897
#Sta/Elev= 30
       0 3106.07     8.5 3101.79      20 3093.28    35.4 3084.08    69.2 3059.47
    89.5  3046.6   109.3 3030.08   143.3 3006.47   152.9 3001.08   163.4 2998.48
   180.5 2996.13   243.8 2993.66   331.5 2993.89     385  2996.4   401.9 2995.62
     475 2996.46   493.5 2994.78   518.1 2994.38     522 2993.26   533.4 2986.39
   542.4 2983.17  564.772982.461   584.6 2980.67   591.7 2982.46   624.7 3015.16
   635.1 3026.44   650.7 3036.04   670.8 3044.07   682.5 3047.33   744.1  3055.3
#Mann= 4 ,-1,0
       0      .1       0  564.77    .045       0   591.7      .1       0
  729.09     .05       0
Bank Sta=564.77,591.7
XS Rating Curve= 0 ,0
Exp/Cntr=0.3,0.1

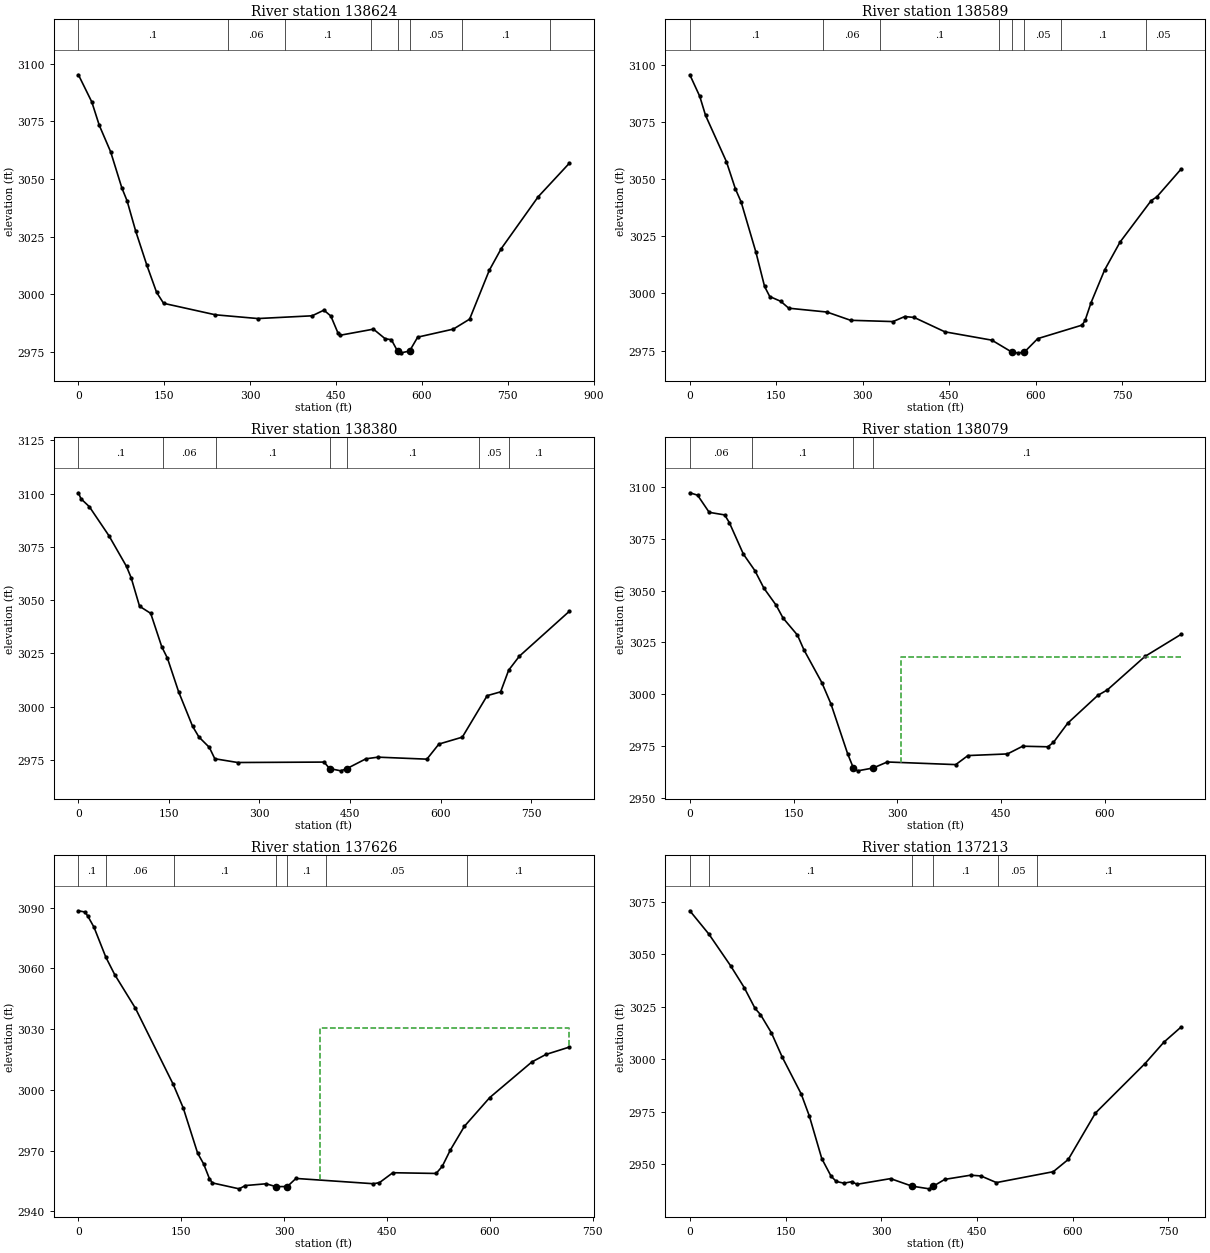
Type RM Length L Ch R = 1 ,138624  ,35,35,35
BEGIN DESCRIPTION:
structure
END DESCRIPTION:
XS GIS Cut Line= 6
2247510.73126913536910.5235051222247715.69821381536991.013214717
2247793.50786523 537306.170292072247829.89367345537358.789768573
 2247828.1885767537432.8470297222247967.22786755537538.179825823
#Sta/Elev= 30
       0 3095.21    23.4 3083.42    36.5 3073.25    56.3  3061.8    75.9 3046.12
      85 3040.54   100.2 3027.28   119.6 3012.56   136.6 3000.81   148.8 2996.05
   239.4 2991.06   313.6 2989.44   408.3 2990.63   428.9 2993.08     441 2990.52
   453.6 2983.08   457.5  2982.2   515.4 2984.84     536 2980.65   546.7 2980.27
   557.52975.325   563.6 2974.56   578.52975.335   592.7 2981.37     655 2984.86
   683.4 2989.18   717.8 3010.38   738.5 3019.71   803.1 3042.25   857.8 3056.88
#Mann= 8 ,-1,0
       0      .1       0  260.69     .06       0  360.69      .1       0
  510.69     .05       0   557.5    .045       0   578.5     .05       0
  669.28      .1       0  823.36     .05       0
Bank Sta=557.5,578.5
XS Rating Curve= 0 ,0
Exp/Cntr(USF)=0,0
Exp/Cntr=0.3,0.1

Type RM Length L Ch R = 1 ,138589  ,209.6,209.6,209.6
BEGIN DESCRIPTION:
structure
END DESCRIPTION:
XS GIS Cut Line= 6
2247492.59828832536932.4109154492247687.88529229537006.354538311
2247749.50497801537295.4930636072247799.74872175537378.916638119
2247800.69671692537435.7963480132247948.58396264537557.139729121
#Sta/Elev= 30
       0 3095.53    17.2 3086.12    27.3 3077.76    63.4 3057.62      79  3045.7
      89 3039.94   114.6 3018.04   129.6 3003.06   138.6 2998.65   157.7 2996.57
   171.5 2993.56   237.8 2991.88   278.7 2988.28   352.3 2987.72   372.7 2989.92
   389.1 2989.51   442.3 2983.24   523.7  2979.6  559.06 2974.28   568.6 2974.06
   579.72974.277   603.3 2980.27   680.3 2986.18   685.4  2988.2   695.8    2996
   719.2 3010.21   746.1 3022.46   800.1 3040.59   809.6 3042.14   851.5 3054.22
#Mann= 8 ,-1,0
       0      .1       0  230.33     .06       0  330.33      .1       0
  535.96     .05       0  559.06    .045       0   579.7     .05       0
  643.35      .1       0  790.24     .05       0
Bank Sta=559.06,579.7
XS Rating Curve= 0 ,0
Exp/Cntr(USF)=0,0
Exp/Cntr=0.3,0.1

Type RM Length L Ch R = 1 ,138380  ,300.6,300.6,300.6
XS GIS Cut Line= 4
2247300.56020567537147.8759071422247488.72964323537256.997943048
2247676.72197802537582.5512878022247874.74249278537678.779667829
#Sta/Elev= 30
       0 3100.38     4.2 3097.58    18.1 3093.86    50.4 3080.31    79.7 3065.81
    87.4 3060.51   101.3 3047.14   119.8 3043.79   138.1 3028.13   147.5 3022.77
     166 3007.04   189.1 2990.86   199.7 2985.77   216.9 2980.92     226 2975.57
   263.9 2973.81   407.1 2974.01  416.082970.982   434.8  2969.9  445.062970.983
   476.4 2975.55   496.4 2976.32   577.4 2975.38   597.3 2982.46   636.1 2985.71
   677.3 3005.18   699.6 3006.97   712.9 3017.14   730.7 3023.72   813.6 3044.81
#Mann= 7 ,-1,0
       0      .1       0     140     .06       0  227.52      .1       0
  416.08    .045       0  445.06      .1       0  663.45     .05       0
  713.45      .1       0
Bank Sta=416.08,445.06
XS Rating Curve= 0 ,0
Exp/Cntr(USF)=0,0
Exp/Cntr=0.3,0.1

Type RM Length L Ch R = 1 ,138079  ,453.5,453.5,453.5
XS GIS Cut Line= 4
2247118.74644942537483.7669496342247330.33004419537581.015491499
2247594.27280018537702.736461382 2247745.6439043537812.137485266
#Sta/Elev= 30
       0  3097.3    11.2 3096.14      28 3087.85    50.4  3086.6    57.1 3082.92
    77.5 3067.64      94 3059.74   107.2 3051.18   124.8    3043   134.8 3036.79
   155.7 3028.52     165 3021.44   190.9  3005.6   204.1 2995.32   228.3 2971.18
  236.582964.324   242.8 2962.94  265.322964.326   285.6 2967.22   384.7 2965.95
   402.3 2970.32   459.5 2971.11   481.5 2974.84   517.8 2974.56   525.9 2976.65
   546.7 2985.99     590 2999.35     604 3002.06   658.4 3018.23   710.3 3028.83
#Mann= 4 ,-1,0
       0     .06       0      90      .1       0  236.58    .045       0
  265.32      .1       0
#XS Ineff= 2 , 0
                          306.14         3017.93
Permanent Ineff=
       F       F
Bank Sta=236.58,265.32
XS Rating Curve= 0 ,0
Exp/Cntr=0.3,0.1

Type RM Length L Ch R = 1 ,137626  ,412.2,412.2,412.2
XS GIS Cut Line= 4
2246967.17082581  537883.9310547 2247144.7899609 537956.42879026
2247453.27126675 538088.125931582247637.60610613538129.642310387
#Sta/Elev= 30
       0 3088.45     9.7 3087.82      14 3085.64    22.7 3080.36      40 3065.53
    52.9 3056.94    83.2 3040.28   138.3  3002.7   152.9 2991.06   173.9 2968.72
   182.5 2963.51   191.2 2956.04   195.5 2954.01   234.5 2951.09   243.4 2952.71
   273.8 2953.59   287.9 2952.19   304.7 2952.23   317.3 2956.23   430.4 2953.61
   439.1 2954.16   458.6 2959.05   521.7 2958.69   530.6 2962.14   542.5 2970.27
     563 2981.98   599.9 2996.16   661.4 3013.77   681.9 3017.47   716.2 3021.13
#Mann= 7 ,-1,0
       0      .1       0      40     .06       0     140      .1       0
   287.9    .045       0   304.7      .1       0  361.84     .05       0
  567.26      .1       0
#XS Ineff= 2 , 0
                          352.35         3030.76
Permanent Ineff=
       F       F
Bank Sta=287.9,304.7
XS Rating Curve= 0 ,0
Exp/Cntr=0.3,0.1

Type RM Length L Ch R = 1 ,137213  ,579.2,579.2,579.2
XS GIS Cut Line= 4
2246776.11090867538284.3572440082246985.97950882538360.454266479
2247331.90958439538413.6368947522247483.55511332538538.021513107
#Sta/Elev= 30
       0 3070.82    29.9 3059.69    63.9 3044.62    85.2 3034.26   102.2 3024.31
   110.7 3021.38   127.7 3012.76   144.7 3001.18   174.5 2983.58   187.3 2973.03
   206.8 2952.74   221.3 2944.41   229.5 2941.89   241.6 2941.06   253.8 2941.79
   261.9 2940.54   314.5 2943.25  347.962939.676   375.2 2938.38  381.672939.675
   399.5 2942.89     440 2944.88   456.1 2944.52   480.4 2941.36   569.5 2946.55
     593 2952.39   635.6  2974.5   713.3 2998.07   742.8 3008.24   769.4 3015.35
#Mann= 6 ,-1,0
       0     .06       0      30      .1       0  347.96    .045       0
  381.67      .1       0  483.24     .05       0  543.24      .1       0
Bank Sta=347.96,381.67
XS Rating Curve= 0 ,0
Exp/Cntr=0.3,0.1

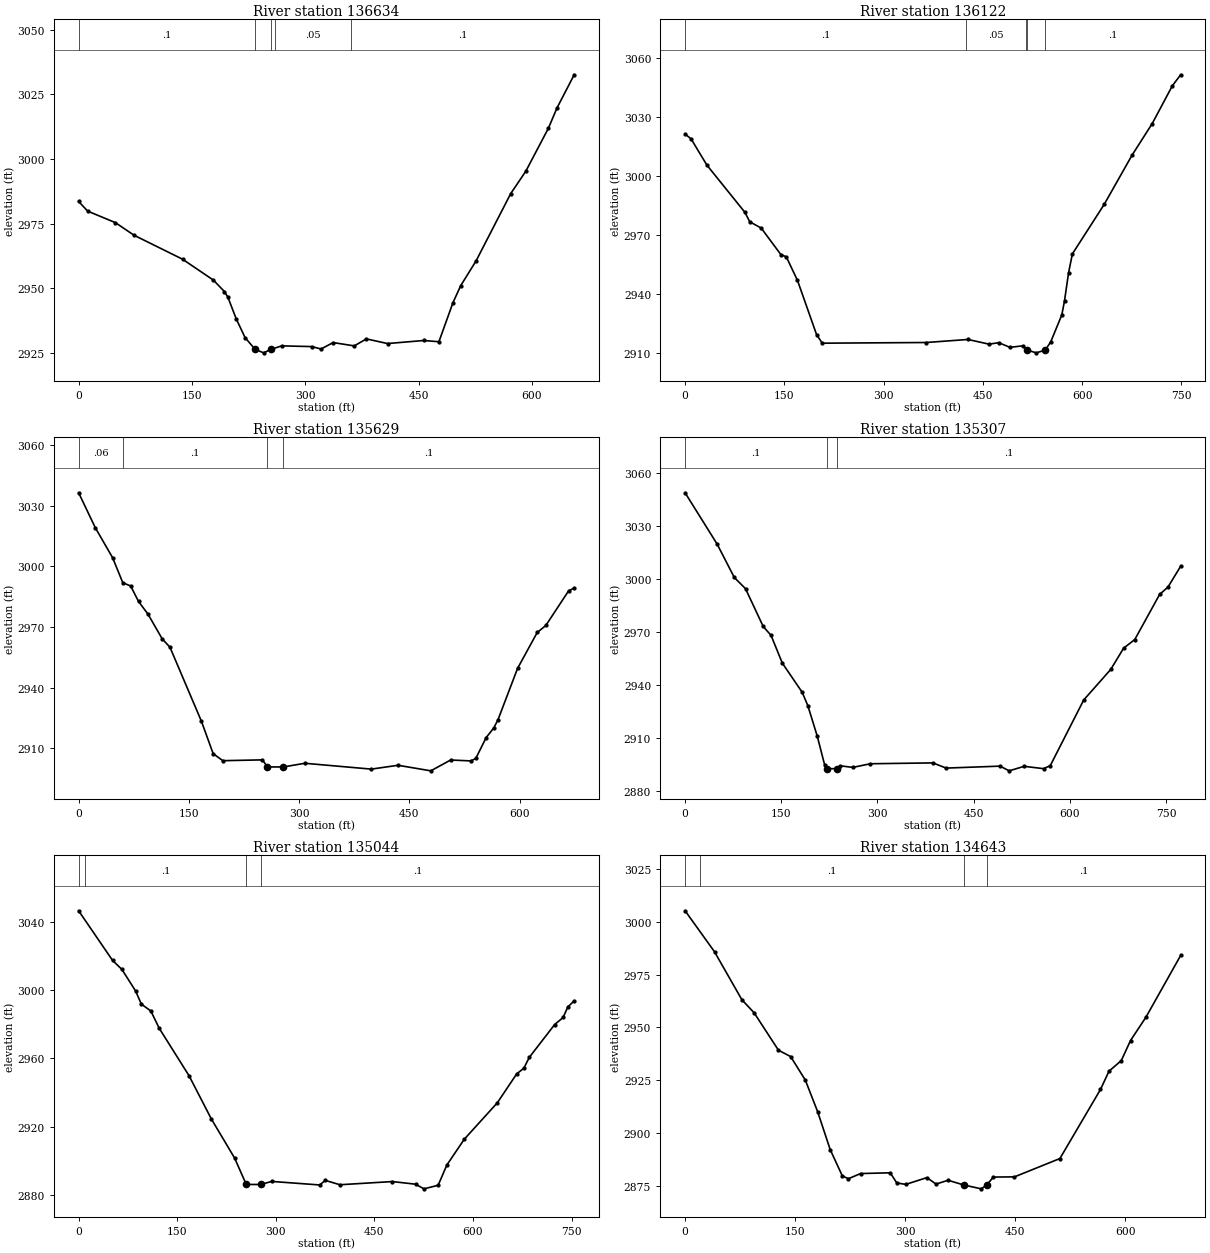
Type RM Length L Ch R = 1 ,136634  ,512.2,512.2,512.2
XS GIS Cut Line= 4
2246674.29514697538786.6103934112246863.58246933538899.160637333
2247123.94543065538899.5355798942247294.39252846538940.042050892
#Sta/Elev= 30
       0 2983.55      12 2979.81    48.7 2975.35    73.3 2970.48   137.5 2961.19
   178.3  2953.1   192.9 2948.68   197.6 2946.41   208.5 2938.13   220.2 2930.85
  233.412926.314   244.8 2924.92  254.972926.313   268.8 2927.62   308.8 2927.34
   320.8  2926.4   336.8  2928.9   364.8 2927.61   380.8 2930.32   408.8 2928.52
   456.8  2929.7   476.8 2929.22   495.4 2944.36   505.6 2950.92     526 2960.55
   571.8 2986.59   591.8 2995.28   621.7 3011.92   632.9 3019.68   655.8 3032.63
#Mann= 5 ,-1,0
       0      .1       0  233.41    .045       0  254.97      .1       0
  260.22     .05       0  360.22      .1       0
Bank Sta=233.41,254.97
XS Rating Curve= 0 ,0
Exp/Cntr=0.3,0.1

Type RM Length L Ch R = 1 ,136122  ,493.5,493.5,493.5
XS GIS Cut Line= 4
2246448.31509015538881.6991989352246561.11605124539052.212185506
2246788.53087243539316.4218088752246908.33779075539471.107767522
#Sta/Elev= 30
       0 3021.34       9 3018.89    32.9 3005.53    90.5  2981.4    97.7 2976.65
     115 2973.43   144.7 2959.94   152.9  2958.8   169.8 2946.78   198.7 2919.12
   207.3 2914.81   364.1 2915.15   427.4  2916.7   459.1 2914.32   473.9 2915.05
   490.9 2912.68   510.8  2913.5  516.772911.302   530.6 2909.89  544.262911.303
   552.5 2915.54   569.2 2929.25   573.3 2936.49   579.3 2950.51   585.1 2960.27
   633.2  2985.5   675.4 3010.64   705.8  3026.7   736.1 3045.88   748.7 3051.53
#Mann= 5 ,-1,0
       0      .1       0  424.45     .05       0  514.45      .1       0
  516.77    .045       0  544.26      .1       0
Bank Sta=516.77,544.26
XS Rating Curve= 0 ,0
Exp/Cntr=0.3,0.1

Type RM Length L Ch R = 1 ,135629  ,321.6,321.6,321.6
XS GIS Cut Line= 5
2246159.70596015539144.2495248282246283.58314433 539283.75422645
2246321.06143964539427.0973980222246464.22592314539556.839214936
2246573.79112743 539654.03915519
#Sta/Elev= 30
       0 3036.43    22.6  3019.2    46.3 3004.26    60.1 2991.93    70.8 2990.31
    81.5 2982.67    94.5 2976.32   113.6 2964.22   124.3 2959.99   167.1 2923.38
   183.1 2907.33   196.3 2903.86   250.1 2904.27256.95512900.768278.6936 2900.77
   307.9 2902.58   398.3 2899.69   434.7 2901.59   479.3 2898.84   506.3  2904.2
   533.8 2903.75   540.5 2904.97   554.6 2915.28     565 2920.07   570.7  2924.1
   597.4 2949.57   624.1  2967.3   635.8 2970.76   666.9 2987.94   674.4 2989.29
#Mann= 4 ,-1,0
       0     .06       0      60      .1       0256.9551    .045       0
278.6936      .1       0
Bank Sta=256.9551,278.6936
XS Rating Curve= 0 ,0
Exp/Cntr=0.3,0.1

Type RM Length L Ch R = 1 ,135307  ,263.5,263.5,263.5
XS GIS Cut Line= 4
2245834.98215424539444.2942380372246027.76835047539535.077155837
2246343.97851359539730.9234504182246492.90330009539845.167122257
#Sta/Elev= 30
       0 3048.99      50 3019.84    76.7 3000.94    94.2 2994.58   121.8 2973.13
     134 2968.09   151.6 2952.35   182.6 2935.78   191.4 2928.19     206 2910.99
   217.8  2894.3  220.972892.481   237.1  2892.4   241.8 2894.09   261.4 2893.17
   288.9 2895.24   386.3 2895.73     407 2892.78   491.2 2893.89   505.3 2891.22
   528.7 2893.78   558.9 2892.46   569.4 2894.16   621.6 2931.44   663.8  2948.8
   683.8 2960.82   701.2 2965.72   739.9 2991.29     753 2995.52   772.7 3007.28
#Mann= 3 ,-1,0
       0      .1       0  220.97    .045       0   237.1      .1       0
Bank Sta=220.97,237.1
XS Rating Curve= 0 ,0
Exp/Cntr(USF)=0,0
Exp/Cntr=0.3,0.1

Type RM Length L Ch R = 1 ,135044  ,400.8,400.8,400.8
XS GIS Cut Line= 4
2245712.60552724539641.1132918282245927.36578294539777.067138967
2246205.19615658539885.4161144162246382.24802563539981.773441784
#Sta/Elev= 30
       0 3046.78    51.6 3017.63    65.8 3012.34    86.7 2999.65    95.4 2991.96
   109.9 2987.88   122.6 2977.76   167.9 2949.92     202 2924.41   237.4 2901.44
     255 2885.98  277.152885.958   293.7 2887.76   366.7 2885.68   375.4 2888.35
   397.6 2885.81   477.3 2887.68   512.6 2886.13   525.5  2883.4     547 2885.49
   560.3 2897.41   586.8 2912.55     637 2933.93   666.5 2950.93   677.4 2954.26
   685.8  2960.7   724.3 2979.93   737.2 2984.09   744.3 2990.26     754 2993.86
#Mann= 4 ,-1,0
       0     .08       0      10      .1       0     255    .045       0
  277.15      .1       0
Bank Sta=255,277.15
XS Rating Curve= 0 ,0
Exp/Cntr=0.3,0.1

Type RM Length L Ch R = 1 ,134643  ,478.1,478.1,478.1
XS GIS Cut Line= 4
2245605.49983576540033.7738200832245810.78472604540090.196477907
2246100.34077326540159.7932857942246257.32662338540208.842688629
#Sta/Elev= 30
       0 3005.18    40.1 2985.76    77.4 2963.05      94 2956.91   127.2 2939.17
   143.8 2936.16   163.8 2925.03   180.7 2909.97   197.7 2892.12   214.3 2879.61
   222.6 2878.34     239 2880.77   279.5 2881.14   288.4 2876.35   300.7 2875.64
   329.5 2878.86   341.9 2875.79   358.3 2877.59  379.812875.361   403.6 2873.54
  410.942875.361     420 2879.11   448.8 2879.21   510.7 2887.89     566 2920.59
   577.6 2929.25   594.3 2934.23   606.9 2943.76   627.9 2954.79   675.2 2984.02
#Mann= 4 ,-1,0
       0     .06       0      20      .1       0  379.81    .045       0
  410.94      .1       0
Bank Sta=379.81,410.94
XS Rating Curve= 0 ,0
Exp/Cntr=0.3,0.1