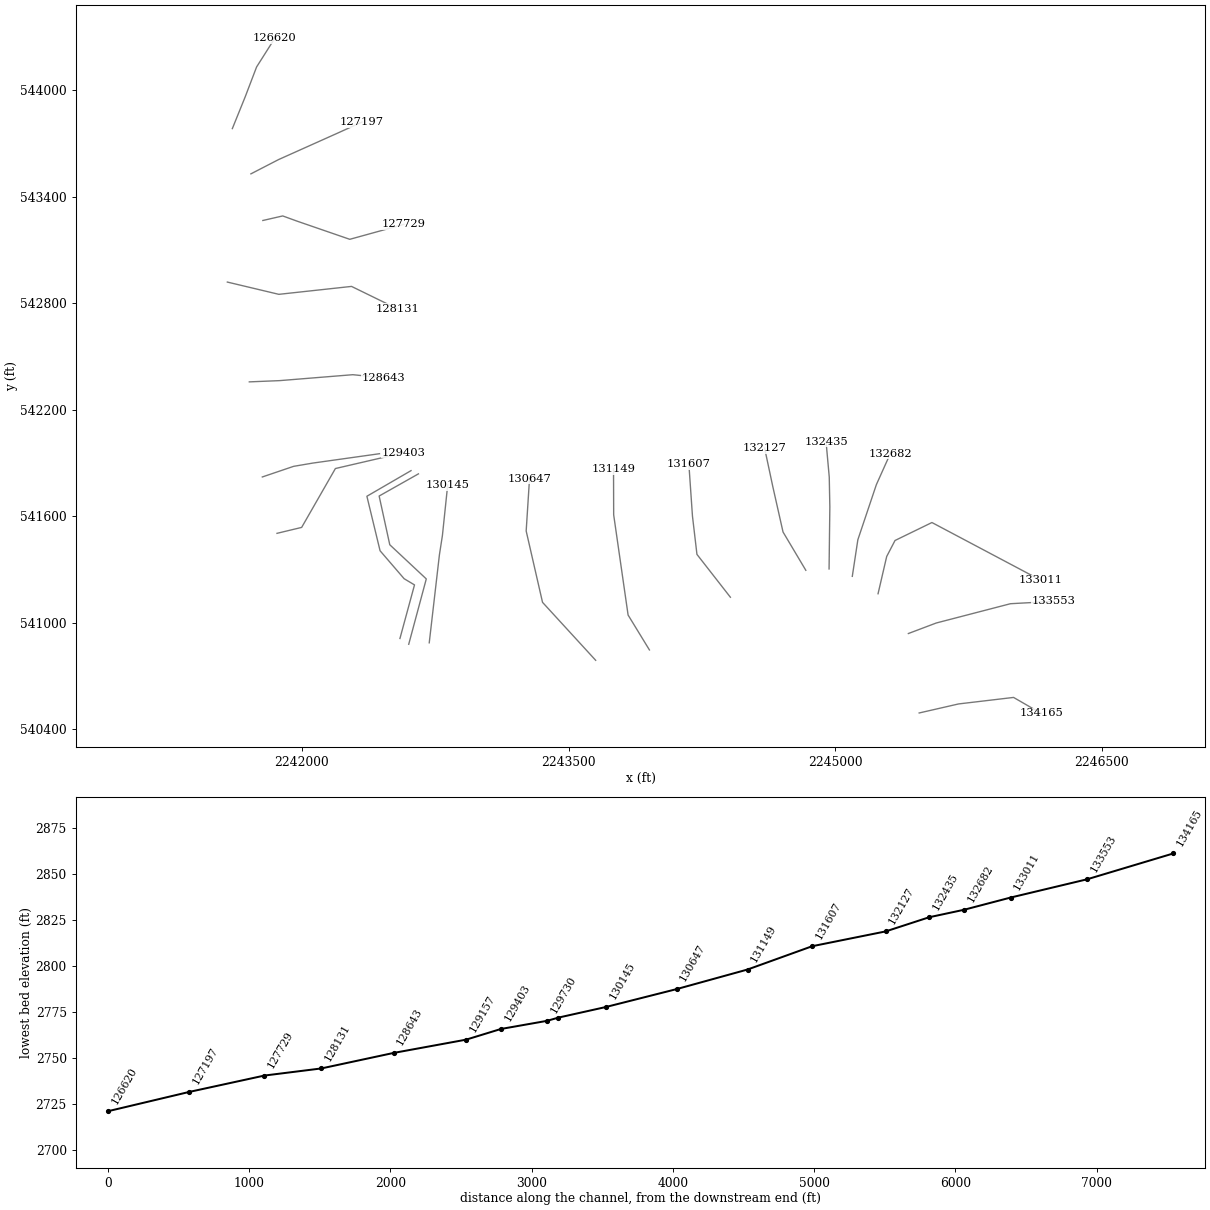
HEC-RAS study TYGVRV2.prj: TYGVRV2

--- TYGVRV2.g01 (geometry) --- (continued)

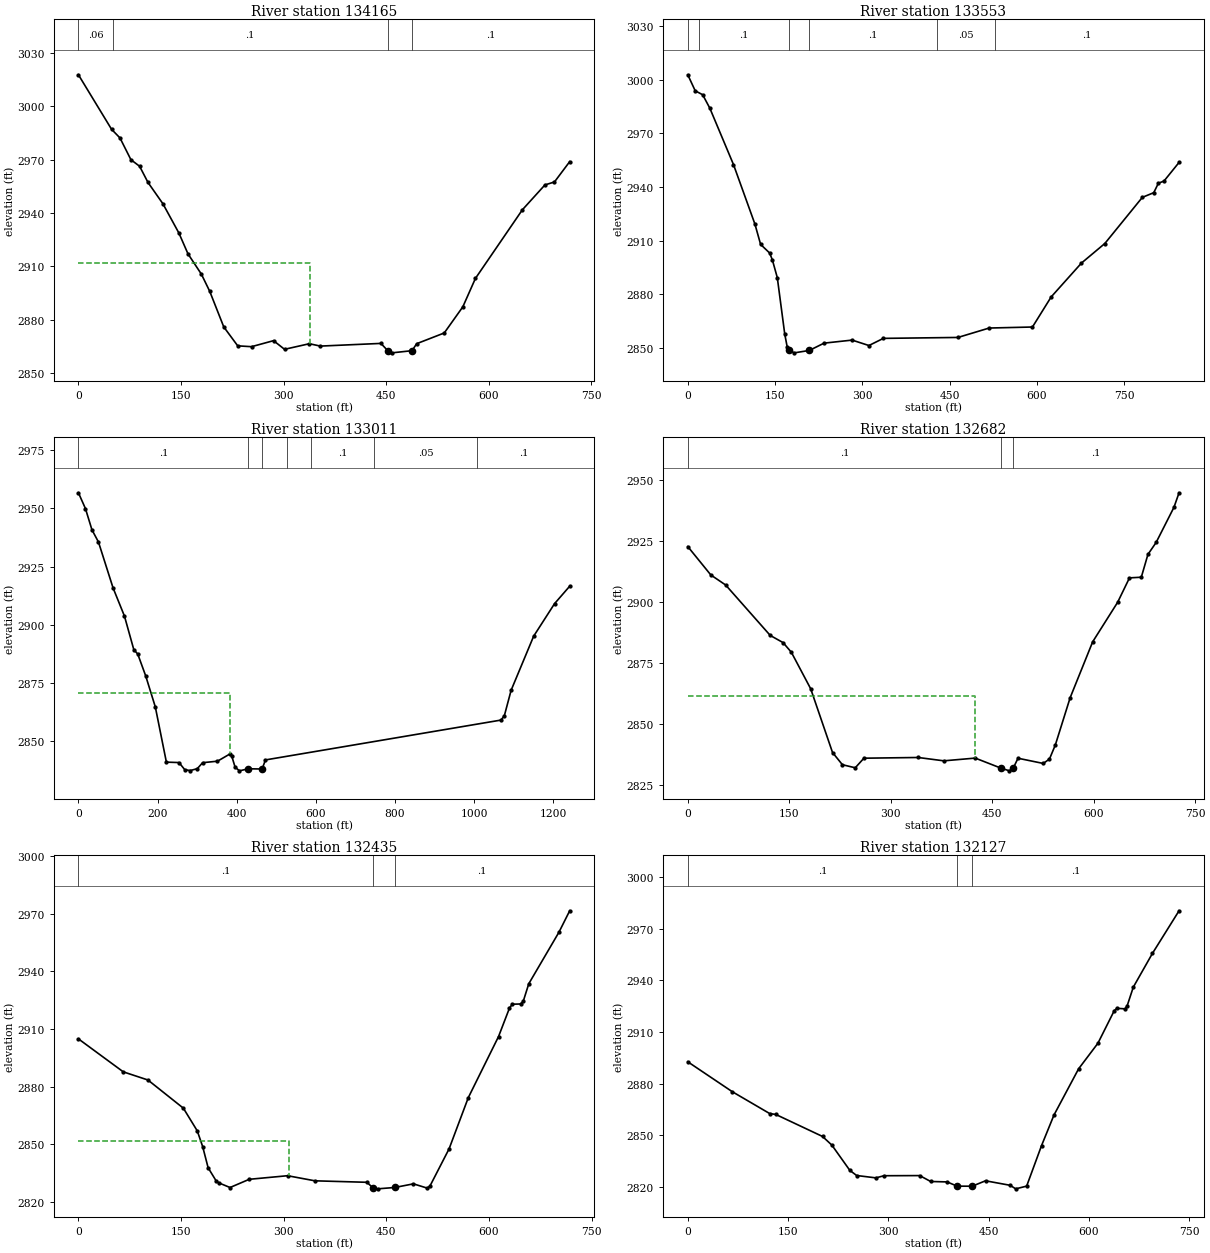
Type RM Length L Ch R = 1 ,134165  ,611.2,611.2,611.2
XS GIS Cut Line= 4
2245472.95080329540492.3173441562245694.72519049540543.217172932
2246004.11937048540579.8762596092246159.52947517540490.048053264
#Sta/Elev= 30
       0 3017.62    48.5 2986.99    60.8 2982.13    76.8 2969.91    89.5 2966.23
   101.8 2957.12   123.6 2945.16     147  2928.7   160.3 2917.01   179.8 2905.67
   192.1 2895.96   212.6 2875.99     233 2865.36   253.2 2864.89   285.4 2868.27
   301.5 2863.41   337.8 2866.55   353.9 2865.22   442.5 2866.73  452.482862.637
   458.6 2861.43  487.952862.636   494.8 2866.57   535.1 2872.59   562.3 2887.28
   580.7 2903.23   649.4 2941.79   682.4 2955.76   696.3 2957.41   718.6 2968.83
#Mann= 4 ,-1,0
       0     .06       0      50      .1       0  452.48    .045       0
  487.95      .1       0
#XS Ineff= 2 , 0
          338.48 2912.14
Permanent Ineff=
       F       F
Bank Sta=452.48,487.95
XS Rating Curve= 0 ,0
Exp/Cntr=0.3,0.1

Type RM Length L Ch R = 1 ,133553  ,542.2,542.2,542.2
XS GIS Cut Line= 4
2245412.21175695540939.7715443522245569.11609851540999.096868704
2245986.68591001541107.7073768662246231.64675313541121.040933822
#Sta/Elev= 30
       0 3002.73    12.8 2993.77    25.6 2991.58    37.9 2984.07    78.6 2952.55
   115.4 2919.33   125.2 2907.96   140.7 2903.14   145.4 2899.31   153.9 2889.38
   166.7 2857.81   170.9 2850.67  173.822848.691   183.3 2847.36  208.912848.695
   234.3 2852.78   282.5 2854.48   311.4 2851.45   336.2 2855.44   464.4 2855.96
   518.1 2861.22   592.5 2861.79   624.7 2878.62   676.8 2897.54   716.9 2908.45
   781.4 2934.24     801 2936.85     809 2942.15   818.6 2943.34   844.5 2953.76
#Mann= 6 ,-1,0
       0     .06       0      20      .1       0  173.82    .045       0
  208.91      .1       0  427.75     .05       0  527.75      .1       0
Bank Sta=173.82,208.91
XS Rating Curve= 0 ,0
Exp/Cntr=0.3,0.1

Type RM Length L Ch R = 1 ,133011  ,329.3,329.3,329.3
XS GIS Cut Line= 5
2245241.57514426541163.8244344772245290.15752089541373.557449087
2245337.08488431 541463.797743292245544.71916644541564.937226156
2246157.91600619541239.767221598
#Sta/Elev= 30
       0 2956.61    17.8 2949.82    34.2 2940.74    50.7 2935.49    87.6 2915.82
   116.4 2903.74     140 2889.38     150 2887.47     170 2878.16   194.4 2864.82
   222.4 2841.14   254.3 2840.96     269 2837.88   282.5 2837.53   300.5 2838.34
     314  2840.9   351.6 2841.55   382.7 2844.61   387.2 2843.96   396.1    2839
   407.1 2837.41  429.31 2838.29  464.412838.198   472.9 2842.09  1068.3 2859.17
  1076.8 2861.04  1093.9 2871.94  1150.9 2895.14  1203.8  2909.1    1242 2916.56
#Mann= 7 ,-1,0
       0      .1       0  429.31    .045       0  464.41      .1       0
     527     .05       0  587.96      .1       0  747.96     .05       0
 1007.96      .1       0
#XS Ineff= 2 , 0
           383.1 2870.69
Permanent Ineff=
       F       F
Bank Sta=429.31,464.41
XS Rating Curve= 0 ,0
Exp/Cntr=0.3,0.1

Type RM Length L Ch R = 1 ,132682  ,246.9,246.9,246.9
XS GIS Cut Line= 4
2245096.67625454541261.8266964012245127.93497055541467.998479083
2245232.07925631541778.2656236952245310.08963151541952.093735759
#Sta/Elev= 30
       0 2922.66    34.1 2911.02      56 2906.91   121.9 2886.25   140.9 2883.31
   153.1 2879.37   181.7 2864.41     214 2838.29   228.6 2833.29   247.6 2832.03
   260.4 2835.96   340.6 2836.25   378.5 2834.88     425    2836   462.9  2831.9
   475.6 2830.78   481.3 2831.96   488.2 2835.94   525.5 2833.81   534.7  2835.6
   543.4 2841.38   565.3 2860.74   598.6 2883.64   635.5 2899.82     653 2909.83
   670.5  2910.1   680.3 2919.45   692.4 2924.33   718.8 2938.76   726.3 2944.69
#Mann= 3 ,-1,0
       0      .1       0   462.9    .045       0   481.3      .1       0
#XS Ineff= 2 , 0
          425.03 2861.32
Permanent Ineff=
       F       F
Bank Sta=462.9,481.3
XS Rating Curve= 0 ,0
Exp/Cntr=0.3,0.1

Type RM Length L Ch R = 1 ,132435  ,307.8,307.8,307.8
XS GIS Cut Line= 4
2244965.97424148541303.5470987712244970.32034632541652.735597199
2244967.02214172541820.7349967712244948.96346237 542020.80554235
#Sta/Elev= 30
       0 2904.86    65.6 2887.67   101.6 2883.43   153.4 2868.74   173.7 2856.93
   181.6 2848.75   189.6 2837.69   201.6 2830.68   205.6 2829.76   221.6  2827.4
   249.7 2831.68   305.7 2833.55   345.7 2830.89   421.7 2830.12   430.2 2827.32
   437.3 2826.71  462.392827.418   489.7 2829.31   509.7  2827.1   513.7 2828.07
   541.8 2847.55   569.9 2874.25   614.1 2906.08   630.1 2920.93   634.2 2922.93
   646.2 2923.04   650.2 2924.45   658.3 2933.59   702.4 2960.45   718.1 2971.61
#Mann= 3 ,-1,0
       0      .1       0   430.2    .045       0  462.39      .1       0
#XS Ineff= 2 , 0
          307.94 2851.66
Permanent Ineff=
       F       F
Bank Sta=430.2,462.39
XS Rating Curve= 0 ,0
Exp/Cntr(USF)=0,0
Exp/Cntr=0.3,0.1

Type RM Length L Ch R = 1 ,132127  ,520.4,520.4,520.4
XS GIS Cut Line= 4
2244835.09146175541295.9493790782244706.91811467541511.580787298
2244649.97222094541764.4852571652244603.17222061541984.044632142
#Sta/Elev= 30
       0 2892.75    66.6 2875.38   122.4 2862.72   131.7 2862.17   201.5 2849.41
   215.5 2844.37   242.3 2829.74   252.5 2826.75   281.2 2825.38   293.5 2826.62
   346.8  2826.7   363.2 2823.28   387.8 2823.03   402.8 2820.57   425.2 2820.53
   445.2 2823.68   482.1 2821.06   490.3 2819.01   506.7 2820.58     529 2844.12
   547.6 2861.87   584.4 2888.67   613.3 2903.53   637.6 2922.35   641.7 2923.79
   653.9 2923.48   657.1 2925.35   666.2 2936.09   694.8 2955.67   734.6  2980.4
#Mann= 3 ,-1,0
       0      .1       0   402.8    .045       0   425.2      .1       0
Bank Sta=402.8,425.2
XS Rating Curve= 0 ,0
Exp/Cntr=0.3,0.1

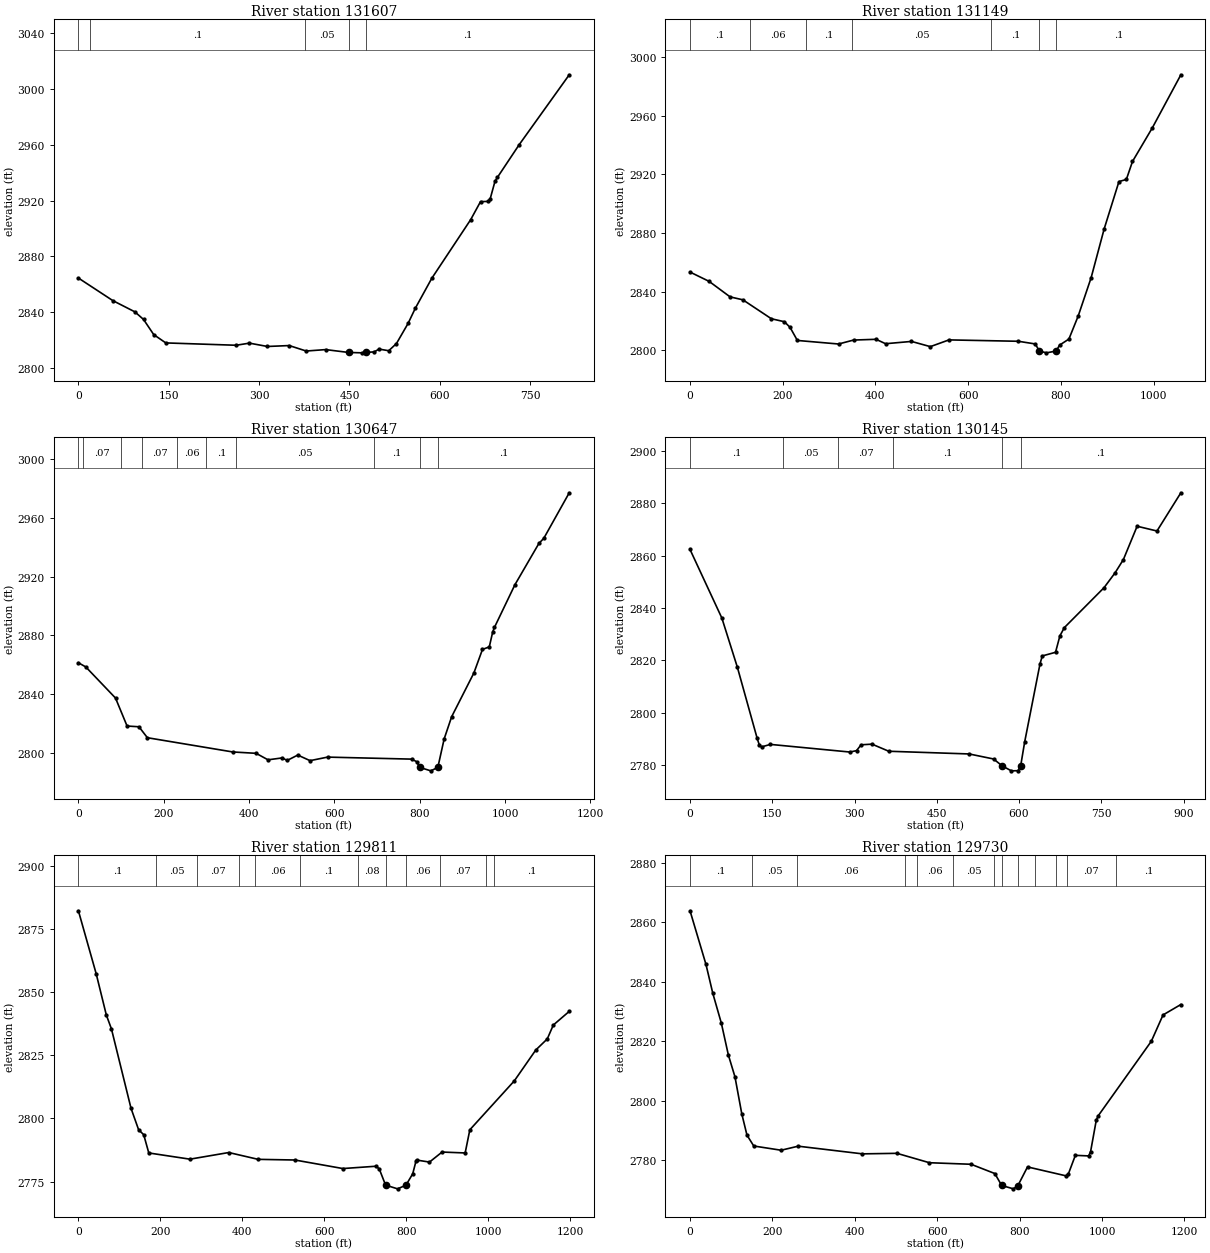
Type RM Length L Ch R = 1 ,131607  ,457.8,457.8,457.8
XS GIS Cut Line= 4
 2244410.7176482541144.1350413392244222.50357128541385.541860945
2244197.27998369 541601.091606432244177.15147582541892.201200506
#Sta/Elev= 30
       0 2864.54    57.1 2848.39    93.8 2840.31   108.2 2834.85   125.1    2824
   145.1 2818.07   261.9 2816.39   283.9 2817.91   313.8 2815.52     350 2816.17
   378.2 2812.26   410.5 2813.28   448.5 2811.24   470.9 2810.96   477.3 2811.26
     491 2811.64   499.1 2813.65   515.2 2812.47     528  2817.6   547.3 2832.01
   559.3 2842.86   586.6  2864.3   651.3  2906.4   667.6 2919.27   679.6 2919.42
   683.6 2921.24   691.6 2933.81   695.6 2936.62   731.7 2960.02   814.9 3010.14
#Mann= 5 ,-1,0
       0     .06       0      20      .1       0  376.11     .05       0
   448.5    .045       0   477.3      .1       0
Bank Sta=448.5,477.3
XS Rating Curve= 0 ,0
Exp/Cntr=0.3,0.1

Type RM Length L Ch R = 1 ,131149  ,502.6,502.6,502.6
XS GIS Cut Line= 4
2243955.09345472540847.3640492122243835.08463412 541043.89478521
2243753.91056552541608.4252550622243753.10907565541866.802028121
#Sta/Elev= 30
       0 2853.34    41.3 2846.98    86.5 2836.41     114 2834.43   175.5 2821.52
   203.7 2819.48   215.9  2815.6   231.6 2806.72   320.5  2804.3   352.8 2806.99
   401.3 2807.51   421.9  2804.5   477.8 2806.06   518.5 2802.51   558.7  2807.1
   708.4 2806.16   744.8 2804.34  753.842799.503     769 2798.28  789.892799.502
   797.3 2803.54   817.4 2807.66   837.4 2823.31   865.4  2849.5   893.4 2882.64
   925.4 2915.02   941.4 2916.47   954.6 2928.71   997.4 2951.63    1059 2987.81
#Mann= 7 ,-1,0
       0      .1       0     130     .06       0  250.27      .1       0
  350.27     .05       0  650.27      .1       0  753.84    .045       0
  789.89      .1       0
Bank Sta=753.84,789.89
XS Rating Curve= 0 ,0
Exp/Cntr=0.3,0.1

Type RM Length L Ch R = 1 ,130647  ,501.1,501.1,501.1
XS GIS Cut Line= 4
2243652.52085365540789.0112655472243353.58964329541115.434912374
2243261.55592691 541517.313674412243280.40997891541812.163283183
#Sta/Elev= 30
       0 2861.32    17.4 2858.44      87 2837.24   114.1 2818.16   141.9 2817.67
   161.7  2810.2   361.8 2800.49   416.5 2799.56   444.4 2795.13   477.2 2796.42
   489.5 2794.75   514.2 2798.37   542.9 2794.56   583.9 2796.98   780.9 2795.61
   793.2 2793.81  799.712789.984     826 2787.62  842.432789.987   857.2 2809.36
   874.8 2824.53   926.9 2854.35     947  2870.4     963 2872.14     971 2882.29
     975 2885.37  1023.1 2914.52  1079.2 2942.63  1090.8 2946.19  1150.4  2977.2
#Mann= 10 ,-1,0
       0      .1       0      10     .07       0     100      .1       0
     150     .07       0     230     .06       0     300      .1       0
     370     .05       0  692.62      .1       0  799.71    .045       0
  842.43      .1       0
Bank Sta=799.71,842.43
XS Rating Curve= 0 ,0
Exp/Cntr=0.3,0.1

Type RM Length L Ch R = 1 ,130145  ,334.9,334.9,334.9
XS GIS Cut Line= 4
2242716.09251344540887.4973567672242773.41121223541383.433057501
2242790.24206557541491.9065901172242819.94951344541776.563011998
#Sta/Elev= 30
       0  2862.3    58.1 2836.14    86.3 2817.43   122.5 2790.25   126.5 2787.65
   130.5 2787.02   146.7 2787.96   291.6 2785.05   303.7 2785.59     312 2787.81
   331.9 2788.06   362.5 2785.35   509.1 2784.32   553.6  2782.4  569.192779.789
     586 2777.88   598.2 2777.93  603.042779.787   610.3 2788.88   638.4 2818.78
   642.5 2821.71   666.6 2823.09   674.6 2829.38   682.7 2832.51   755.1 2847.74
   775.2  2853.4   790.4 2858.48   815.4 2871.17   851.6 2869.35   895.2 2883.93
#Mann= 6 ,-1,0
       0      .1       0     170     .05       0     270     .07       0
     370      .1       0  569.19    .045       0  603.04      .1       0
Bank Sta=569.19,603.04
XS Rating Curve= 0 ,0
Exp/Cntr=0.3,0.1

Type RM Length L Ch R = 1 ,129811  ,80.4,80.4,80.4
BEGIN DESCRIPTION:
structure
END DESCRIPTION:
XS GIS Cut Line= 5
2242600.66876892540879.3373667032242699.49954057 541247.35195061
2242494.03556793 541439.811874352242434.21694299541714.197306167
2242655.28577431 541839.03617562
#Sta/Elev= 30
       0 2882.18    43.3 2857.31    68.2 2840.89    80.6 2835.44   128.4 2803.99
   146.9 2795.52   159.3 2793.57   171.7 2786.34   272.1 2783.88   366.8 2786.51
   438.5 2783.81   528.1 2783.55   645.1 2780.17   725.4 2781.08   733.6 2780.13
   749.3 2773.61   778.6 2772.14  799.04  2773.6   815.5  2778.1   823.6  2783.2
   826.6 2783.49   856.4 2782.73   887.1  2786.7   943.4 2786.34   954.8 2795.51
  1063.4 2814.89  1115.6 2827.07  1143.7 2831.47  1158.4 2836.96  1197.3 2842.37
#Mann= 12 ,-1,0
       0      .1       0     190     .05       0     290     .07       0
  391.05      .1       0  431.05     .06       0  541.05      .1       0
  682.58     .08       0   749.3    .045       0  799.04     .06       0
  882.58     .07       0  993.41     .05       0 1013.41      .1       0
Bank Sta=749.3,799.04
XS Rating Curve= 0 ,0
Exp/Cntr(USF)=0,0
Exp/Cntr=0.3,0.1

Type RM Length L Ch R = 1 ,129730  ,326.9,326.9,326.9
BEGIN DESCRIPTION:
structure
END DESCRIPTION:
XS GIS Cut Line= 6
 2242551.2533831540911.8474889562242633.17889118541213.541423467
2242574.66067112  541248.65235552242439.41856255541406.001347206
2242365.29548381541712.8969012772242613.67281783541857.241844082
#Sta/Elev= 30
       0 2863.86    38.7 2845.84    55.3 2836.11      76 2826.09    93.1 2815.36
   109.1 2808.03   125.7 2795.56   138.2 2788.44   154.7 2784.78   221.1 2783.36
   262.5 2784.72   418.5 2782.14   502.1 2782.32     581 2779.16   682.1 2778.64
   739.8 2775.52   756.4 2771.51     785 2770.38   795.9  2771.5   819.1 2777.75
   912.2 2774.76   918.1 2775.33   935.2 2781.64   967.5 2781.45   972.2  2782.9
     986 2793.48   990.7 2794.94  1119.6    2820    1148 2828.84  1191.3 2832.35
#Mann= 13 ,-1,0
       0      .1       0     150     .05       0     260     .06       0
  520.86      .1       0  550.86     .06       0  638.35     .05       0
  738.35     .06       0   756.4    .045       0   795.9     .06       0
  838.35     .07       0  888.35      .1       0  914.07     .07       0
 1034.07      .1       0
Bank Sta=756.4,795.9
XS Rating Curve= 0 ,0
Exp/Cntr(USF)=0,0
Exp/Cntr=0.3,0.1

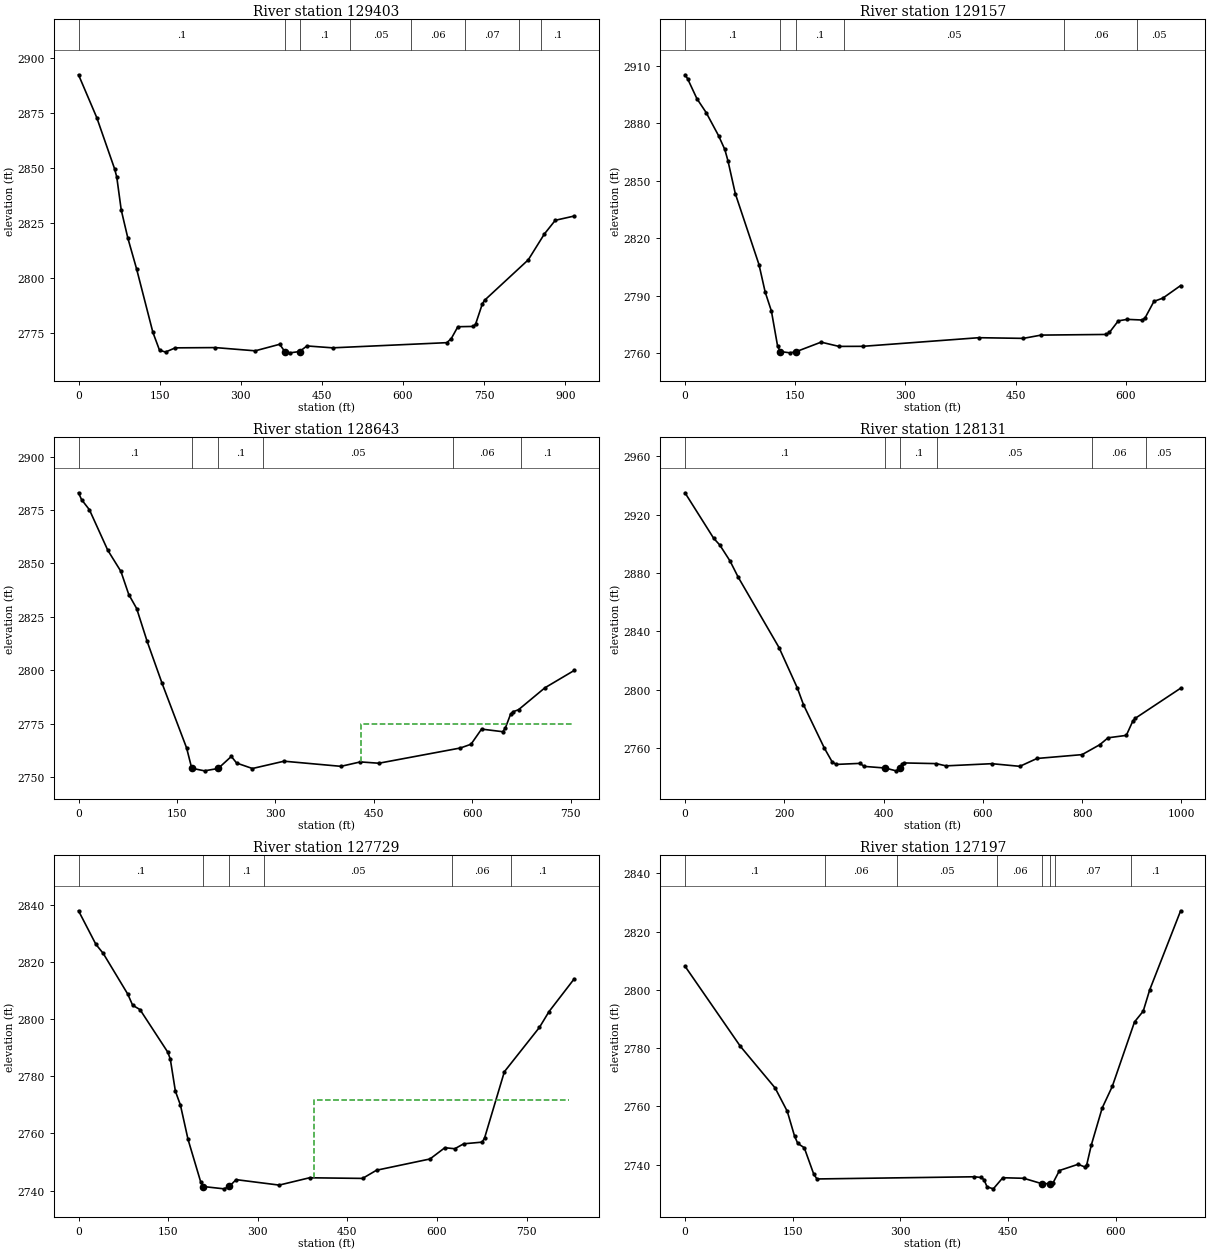
Type RM Length L Ch R = 1 ,129403  ,246.7,246.7,246.7
XS GIS Cut Line= 4
  2241859.408045541504.0796032672241998.21585276541537.482745237
2242188.06617687541869.0640498922242569.68881916541957.485590596
#Sta/Elev= 30
       0 2892.57    33.7  2873.1    66.6 2849.83    70.7 2846.05      79 2831.01
    91.3 2818.13   107.3 2804.26   137.5 2775.32   149.8 2767.15   160.9 2766.31
   178.9 2768.22     253 2768.34   326.8 2766.87   372.1 2769.85   381.4 2766.53
   391.3 2765.95408.79212766.549   422.4 2769.09   469.7 2768.23     681 2770.58
   689.2 2772.38   701.5 2777.84   730.3 2777.98   734.4 2779.08   746.7 2788.19
   750.8 2789.86   831.7  2808.3   861.5 2820.07   881.7 2826.31   916.6 2828.24
#Mann= 8 ,-1,0
       0      .1       0   381.4    .045       0408.7921      .1       0
  502.77     .05       0  614.86     .06       0  714.86     .07       0
  814.86     .05       0  854.86      .1       0
Bank Sta=381.4,408.7921
XS Rating Curve= 0 ,0
Exp/Cntr=0.3,0.1

Type RM Length L Ch R = 1 ,129157  ,513.8,513.8,513.8
XS GIS Cut Line= 4
2241776.86862837541821.584568192 2241952.8127997541881.368525329
2242060.89592891541899.766593064 2242436.1226623541952.542683943
#Sta/Elev= 30
       0 2905.26     3.5 2903.26    16.2 2892.81    28.8 2885.55    45.7 2873.48
    54.2 2866.27    58.4 2860.48    68.5  2843.2   100.7  2806.2   109.1 2791.88
   117.6 2781.94     126 2763.71  129.672760.813   142.9 2760.14   151.4 2760.77
   185.2 2765.72   209.5  2763.5     242 2763.54   399.8 2768.04   460.3 2767.69
   484.6  2769.4   573.5 2769.74   577.5 2770.78   589.6 2776.83   601.7 2777.61
     622 2777.27     626 2778.36   638.1 2787.01   650.2 2788.69   674.4 2795.25
#Mann= 6 ,-1,0
       0      .1       0  129.67    .045       0   151.4      .1       0
  215.82     .05       0  515.46     .06       0  615.46     .05       0
Bank Sta=129.67,151.4
XS Rating Curve= 0 ,0
Exp/Cntr=0.3,0.1

Type RM Length L Ch R = 1 ,128643  ,511.5,511.5,511.5
XS GIS Cut Line= 4
2241703.62304489542357.1542185622241874.41635087542364.197911482
2242285.92644695542397.5576812152242456.60246713542380.438885077
#Sta/Elev= 30
       0 2883.07     4.6 2879.89    16.6 2875.13    44.6 2856.17    64.6 2846.27
    76.6 2835.43    88.6  2828.9   104.6  2813.5   127.4 2793.82   164.7 2763.64
  172.542754.117     192 2752.91   212.8 2754.02   232.9 2759.66   240.9 2756.56
     265    2754   313.2 2757.42   399.9 2755.02   429.5 2757.09   457.6 2756.47
     582 2763.61   598.1 2765.36   614.2 2772.45   646.4 2771.23   650.4 2772.92
   658.4 2779.43   662.4  2780.6   670.5 2781.52   710.7 2791.78   755.3 2799.89
#Mann= 6 ,-1,0
       0      .1       0  172.54    .045       0   212.8      .1       0
  280.94     .05       0  570.94     .06       0   673.8      .1       0
#XS Ineff= 2 , 0
                          431.19         2774.65
Permanent Ineff=
       F       F
Bank Sta=172.54,212.8
XS Rating Curve= 0 ,0
Exp/Cntr=0.3,0.1

Type RM Length L Ch R = 1 ,128131  ,402.3,402.3,402.3
XS GIS Cut Line= 4
2241579.97303985542919.2881694082241869.79203309542850.204901647
2242278.78162668542894.8039515742242538.50464714542767.902692404
#Sta/Elev= 30
       0 2935.02    57.8 2903.84    70.1 2899.23    90.7 2888.31   107.1 2877.24
   189.4 2828.98   226.4 2801.19   238.7 2789.79   280.8 2760.03   296.3 2750.71
   304.4 2748.88   352.6 2749.59   360.7 2747.53  403.682746.397   425.1 2744.48
  433.862746.394   437.1 2748.99   441.2  2749.9     506 2749.43   525.7 2747.89
   618.2 2749.38   674.5 2747.57   709.1 2752.96   799.9 2755.59   835.6 2762.41
   852.2 2767.12     889 2768.78   902.3 2778.75   906.8 2780.44   998.4  2801.1
#Mann= 6 ,-1,0
       0      .1       0  403.68    .045       0  433.86      .1       0
  507.94     .05       0  819.35     .06       0  929.35     .05       0
Bank Sta=403.68,433.86
XS Rating Curve= 0 ,0
Exp/Cntr=0.3,0.1

Type RM Length L Ch R = 1 ,127729  ,532.2,532.2,532.2
XS GIS Cut Line= 5
2241779.86739295  543266.10850872241891.60139004543291.765949846
  2241972.604019543262.3363123732242269.00203687543160.080564531
2242572.74687258543244.092777103
#Sta/Elev= 30
       0 2837.92      29 2826.21    41.4 2822.99    82.4 2808.77    90.6 2804.86
   102.9 2803.34   149.3 2788.47   153.6 2786.04   162.1 2774.82   170.6  2769.9
   183.3 2757.91   204.5 2743.03   208.8 2741.43   243.5 2740.62   252.22741.457
   263.8 2743.84   335.8 2741.93   386.6 2744.49   475.4 2744.27   498.7 2747.13
   588.2 2751.07   613.1 2755.01   629.7 2754.65   644.6 2756.38   675.4 2756.96
   679.5 2758.37   712.7  2781.6   771.4 2797.12   787.4 2802.64   829.5 2814.08
#Mann= 6 ,-1,0
       0      .1       0   208.8    .045       0   252.2      .1       0
  310.83     .05       0  624.37     .06       0  724.37      .1       0
#XS Ineff= 1 ,-1
   393.7   821.5 2771.54
Permanent Ineff=
       F
Bank Sta=208.8,252.2
XS Rating Curve= 0 ,0
Exp/Cntr=0.3,0.1

Type RM Length L Ch R = 1 ,127197  ,576.5,576.5,576.5
XS GIS Cut Line= 4
2241712.65207768543528.7765067762241868.14570318  543609.1235213
 2242202.2463488543759.0006039932242337.83953239543820.538593323
#Sta/Elev= 30
       0 2808.12    77.1 2780.62   125.5 2766.33   142.4 2758.33   152.5 2749.86
     157 2747.32   166.1 2745.81   179.4 2736.68   183.8 2735.11     403 2735.86
   411.8 2735.63   416.2 2734.92   420.6  2732.4   429.3 2731.72   442.5 2735.53
   471.7 2735.34  496.68  2733.5   508.9  2733.5   512.6 2733.84   521.4 2738.01
   547.3 2740.14   556.5 2739.25   559.4 2740.01   565.8  2746.8   580.9 2759.47
   594.9 2766.84   625.9 2788.98     638 2792.68     647 2799.96   690.1 2827.12
#Mann= 8 ,-1,0
       0      .1       0  195.03     .06       0  295.03     .05       0
  435.03     .06       0  496.68    .045       0   508.9     .06       0
  515.03     .07       0   621.2      .1       0
Bank Sta=496.68,508.9
XS Rating Curve= 0 ,0
Exp/Cntr=0.3,0.1

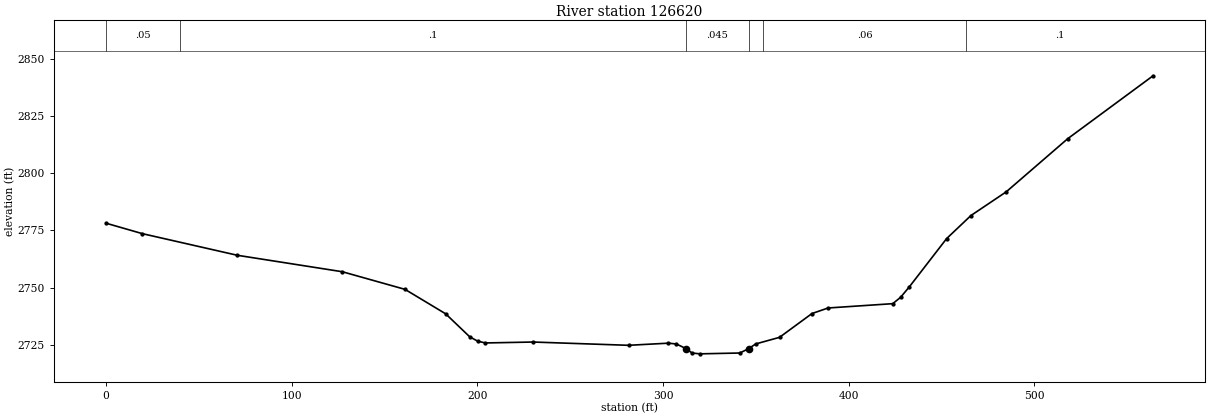
Type RM Length L Ch R = 1 ,126620  ,498.9,498.9,498.9
XS GIS Cut Line= 4
2241608.15706308543783.6407707312241680.79194431543963.364630582
2241744.62416154544130.8425704692241846.79810633544292.048418688
#Sta/Elev= 30
       0 2778.17    19.6 2773.61    70.7 2764.19   127.2 2757.02     161 2749.33
   182.9 2738.66   195.8 2728.68   200.1 2726.74   204.3 2725.96     230 2726.36
   281.4 2724.93   302.8 2725.86   307.1 2725.52  312.462723.458   315.6 2721.56
   319.9 2721.21   341.3 2721.57  346.062723.457   349.9 2725.53   362.7  2728.4
   380.2 2738.79   388.9 2741.21   423.7 2743.09   427.9 2745.85   432.7  2750.5
   452.7 2771.46   465.8 2781.52   484.8 2791.85   517.9 2815.01   563.9 2842.47
#Mann= 6 ,-1,0
       0     .05       0      40      .1       0  312.46    .045       0
  346.06      .1       0  353.85     .06       0  463.08      .1       0
Bank Sta=312.46,346.06
XS Rating Curve= 0 ,0
Exp/Cntr=0.3,0.1