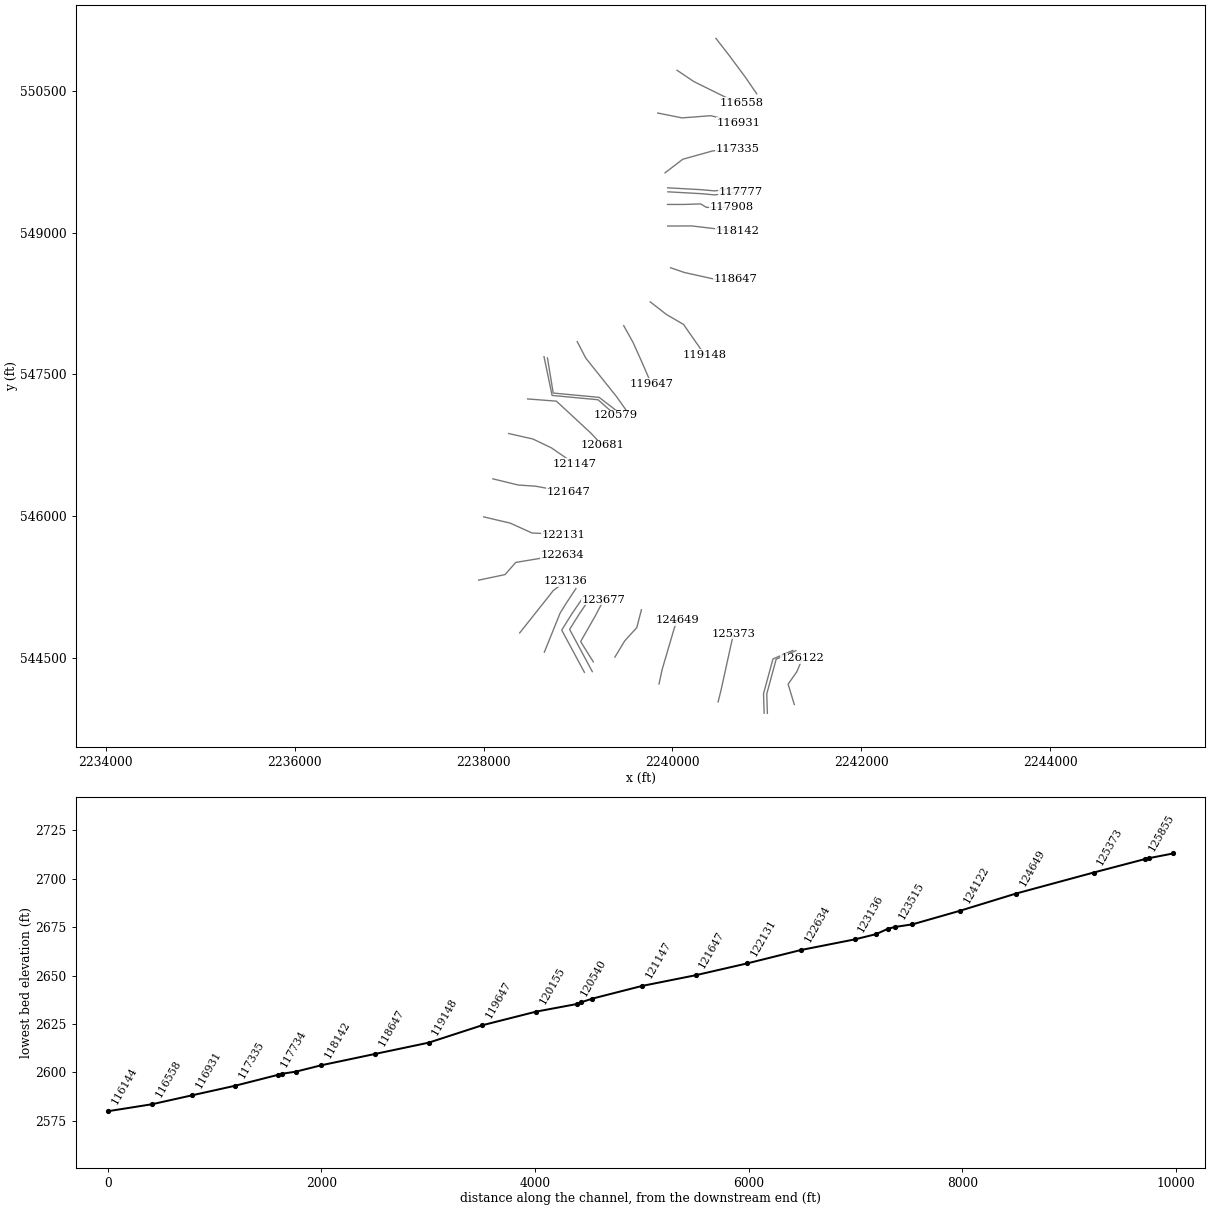
HEC-RAS study TYGVRV2.prj: TYGVRV2

--- TYGVRV2.g01 (geometry) --- (continued)

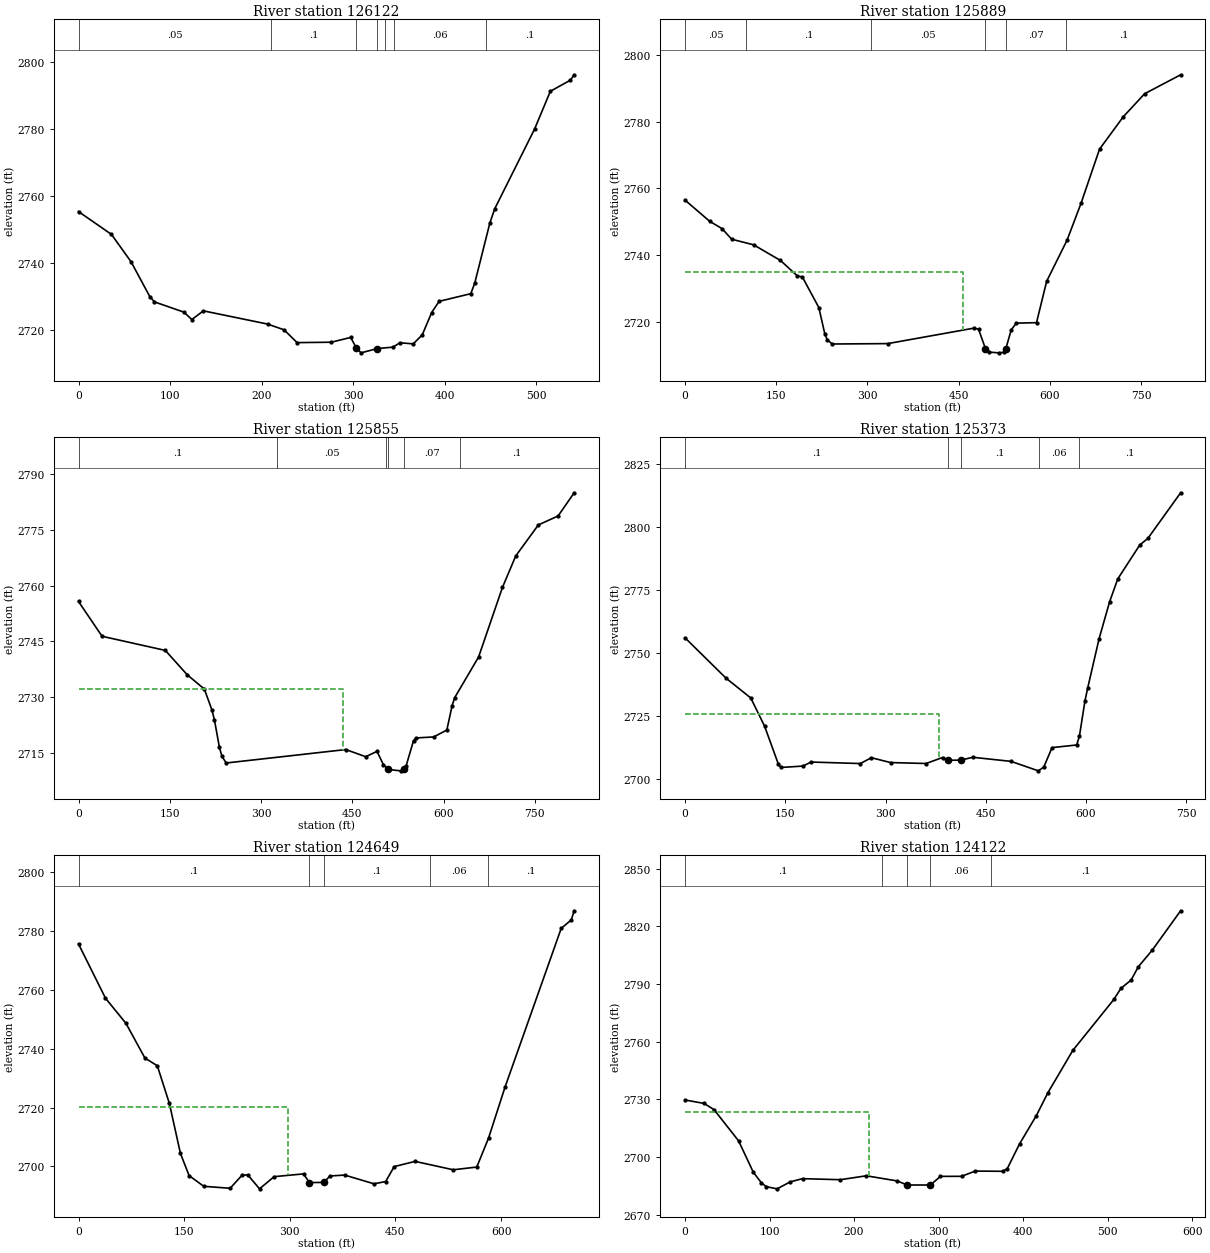
Type RM Length L Ch R = 1 ,126122  ,232.5,232.5,232.5
XS GIS Cut Line= 4
2241289.29074411544006.704544439 2241223.9066142544221.427358976
2241315.84577323544352.9247272652241376.98973221544497.050437806
#Sta/Elev= 30
       0  2755.3      36 2748.48    57.4 2740.32    77.9 2729.92      83 2728.34
   115.1 2725.29   123.8 2723.08   136.4 2725.67   206.5 2721.73   224.5 2720.02
   238.8 2716.19   276.2 2716.31   297.4 2717.74   303.5 2714.57   308.7 2713.14
   326.6 2714.43   343.6 2714.84   351.1 2716.14   365.7 2715.82   375.5 2718.49
   385.8 2725.15   393.9  2728.5   428.6  2730.8     433 2734.06   449.4  2751.9
   454.7 2756.12   498.2 2779.89   515.5  2791.2   537.3  2794.5   541.5 2796.12
#Mann= 7 ,-1,0
       0     .05       0     210      .1       0   303.5    .045       0
   326.6      .1       0  334.46     .07       0  344.46     .06       0
  444.91      .1       0
Bank Sta=303.5,326.6
XS Rating Curve= 0 ,0
Exp/Cntr=0.3,0.1

Type RM Length L Ch R = 1 ,125889  ,33.7,33.7,33.7
BEGIN DESCRIPTION:
structure
END DESCRIPTION:
XS GIS Cut Line= 4
2241004.31377306543912.4111869792240997.89289911544118.252279263
2241097.37757808544485.9678015212241306.51183244544576.228794002
#Sta/Elev= 30
       0 2756.48    40.8 2750.08    60.8 2747.94    76.8 2744.73   112.8 2743.06
   156.8 2738.38   184.9  2733.7   192.9 2733.42     220 2724.24   229.7 2716.45
   233.8 2714.57   242.1  2713.3   333.3 2713.42   474.4 2718.04   482.5 2717.77
   493.9  2711.9     499 2710.88   515.6 2710.65   523.9 2710.79  527.382711.908
   536.3 2717.56   544.6 2719.56   577.8  2719.7   594.5 2732.13     628 2744.44
   650.9 2755.46   681.4 2771.76   720.6 2781.51   755.5 2788.38   814.7 2794.07
#Mann= 6 ,-1,0
       0     .05       0     100      .1       0  305.94     .05       0
   493.9    .045       0  527.38     .07       0  626.88      .1       0
#XS Ineff= 2 , 0
          457.76    2735
Permanent Ineff=
       F       F
Bank Sta=493.9,527.38
XS Rating Curve= 0 ,0
Exp/Cntr(USF)=0,0
Exp/Cntr=0.3,0.1

Type RM Length L Ch R = 1 ,125855  ,482.1,482.1,482.1
BEGIN DESCRIPTION:
structure
END DESCRIPTION:
XS GIS Cut Line= 4
2240970.14637899543914.5455506472240963.72550504544120.386642931
2241063.21018401544488.1021651892241272.34443837 544578.36315767
#Sta/Elev= 30
       0 2755.73    38.7 2746.38   142.7 2742.58   178.7 2736.03   206.8  2732.2
   219.2 2726.63   223.5 2723.83   231.6 2716.53   235.8 2714.09   242.8 2712.33
   439.3 2715.94     472 2714.02   490.7 2715.45     501 2711.91   509.3 2710.59
   529.3 2710.22  535.032710.583   538.3 2711.46   550.7 2718.35   554.8 2719.06
   583.8 2719.33   605.4 2721.18   614.1 2727.76   618.4 2729.91   657.6 2740.81
   696.8  2759.5   718.6 2767.94   755.8  2776.3   788.3 2778.71   814.7 2784.94
#Mann= 6 ,-1,0
       0      .1       0  325.94     .05       0  505.94     .07       0
   509.3    .045       0  535.03     .07       0  626.88      .1       0
#XS Ineff= 2 , 0
          433.94 2732.21
Permanent Ineff=
       F       F
Bank Sta=509.3,535.03
XS Rating Curve= 0 ,0
Exp/Cntr(USF)=0,0
Exp/Cntr=0.3,0.1

Type RM Length L Ch R = 1 ,125373  ,724.4,724.4,724.4
XS GIS Cut Line= 4
2240482.92045639544033.6629929722240514.24454319544159.793950371
 2240613.5578068544611.2790992122240646.52124886 544756.80576602
#Sta/Elev= 30
       0 2756.01    61.3 2740.01    98.4 2732.13     119 2721.01   139.6 2705.96
   143.7 2704.57   176.4 2705.12   188.7 2706.72   262.4 2706.12   278.8 2708.44
   307.5 2706.51   360.7 2706.14   385.3 2708.52   393.5 2707.43   412.8 2707.47
   430.4 2708.61   487.7 2706.99   528.7 2703.23   536.8 2704.72   549.1 2712.44
     586 2713.49   590.1 2717.02   598.3 2730.84   602.4 2736.02   619.4 2755.51
   635.2 2770.26   647.5 2779.37   680.3 2792.78   692.6 2795.46   741.5 2813.51
#Mann= 5 ,-1,0
       0      .1       0   393.5    .045       0   412.8      .1       0
  529.96     .06       0  589.96      .1       0
#XS Ineff= 2 , 0
          379.49 2725.66
Permanent Ineff=
       F       F
Bank Sta=393.5,412.8
XS Rating Curve= 0 ,0
Exp/Cntr=0.3,0.1

Type RM Length L Ch R = 1 ,124649  ,526.5,526.5,526.5
XS GIS Cut Line= 4
2239857.44795674544223.7960552122239891.16101024544378.999738887
2240007.34522736544774.6623687052240047.25477538544901.070856708
#Sta/Elev= 30
       0 2775.63    38.3 2757.19    67.3 2748.68    94.3 2736.85   111.9 2734.23
     129 2721.44   144.7 2704.46     157 2696.91   177.8 2693.26   215.3 2692.59
     232 2696.98   240.3 2697.17     257  2692.4   277.8 2696.54   319.5 2697.48
   327.8 2694.54   348.3 2694.57     357 2696.77   377.9 2697.08   419.6 2694.11
   436.2 2694.89   448.2 2699.96   477.9 2701.73   532.1 2698.88   565.5  2699.8
   582.2 2709.63   605.7 2727.03   685.4 2780.93   699.7 2783.81   703.8 2786.91
#Mann= 5 ,-1,0
       0      .1       0   327.8    .045       0   348.3      .1       0
  498.82     .06       0  581.19      .1       0
#XS Ineff= 2 , 0
          297.47 2720.14
Permanent Ineff=
       F       F
Bank Sta=327.8,348.3
XS Rating Curve= 0 ,0
Exp/Cntr=0.3,0.1

Type RM Length L Ch R = 1 ,124122  ,445.2,445.2,445.2
XS GIS Cut Line= 4
2239390.41696626544507.9269541222239495.29023604544681.161166874
2239621.68354331 544819.579176982239671.37400777545009.505438406
#Sta/Elev= 30
       0 2729.71    22.6 2727.92    34.3 2724.71    63.4 2708.46    80.8 2692.13
    90.3 2686.65    96.1  2684.6     109 2683.47   124.5  2687.1   139.1 2688.77
   183.8 2688.22   214.5 2690.26   251.3 2687.56262.79892685.458  290.272685.469
   302.2 2689.96   327.1 2689.98   343.4 2692.72   375.9 2692.59   381.3 2694.02
   395.7 2706.81   415.6 2721.54   429.3 2733.49   458.8 2755.52   507.4 2782.07
   515.6 2787.78   527.7  2792.1   536.3 2799.05   552.9 2807.78   586.3 2828.16
#Mann= 5 ,-1,0
       0      .1       0  232.51     .06       0262.7989    .045       0
  290.27     .06       0  362.51      .1       0
#XS Ineff= 2 , 0
          217.47 2723.59
Permanent Ineff=
       F       F
Bank Sta=262.7989,290.27
XS Rating Curve= 0 ,0
Exp/Cntr=0.3,0.1

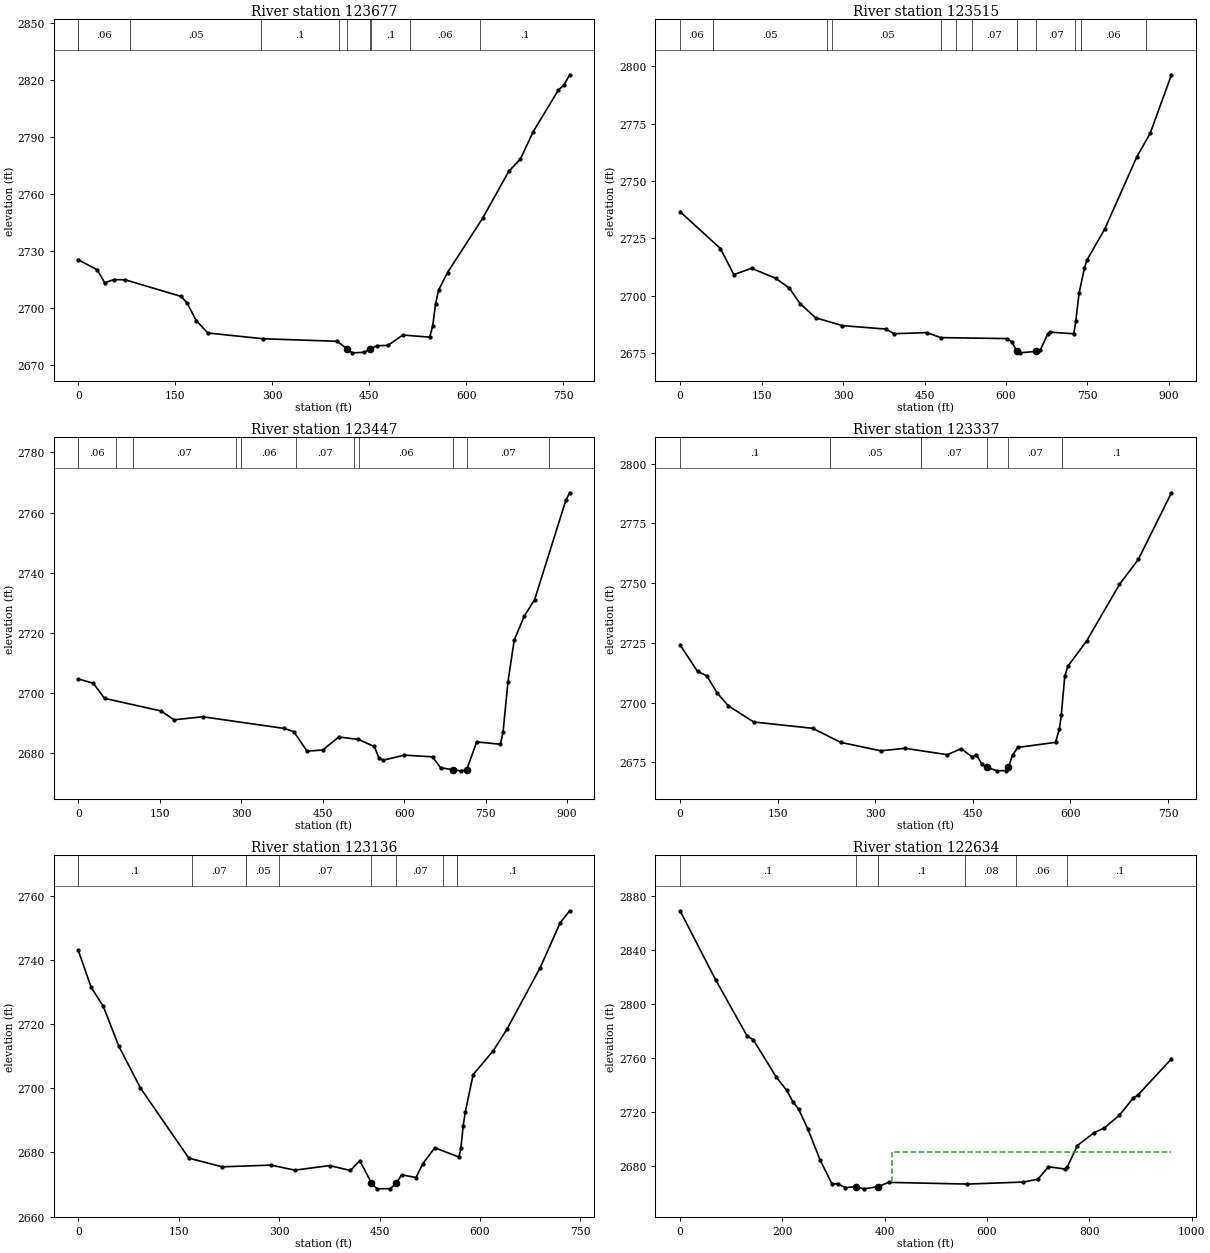
Type RM Length L Ch R = 1 ,123677  ,162.1,162.1,162.1
XS GIS Cut Line= 4
2239161.46102766544458.2640441762239027.78255907544672.749427844
 2239186.1192383544949.8119195342239273.07386232545116.770538705
#Sta/Elev= 30
       0 2725.45    29.2 2720.16    40.8 2713.36    55.4 2715.04    72.7 2714.88
     159 2706.17   168.4 2702.61   182.5  2693.4   200.5 2686.89   285.5 2683.88
   400.7 2682.52  415.872678.424   423.7 2676.45   442.1  2676.7  451.752678.424
   461.5  2680.2   479.1 2680.38     502 2685.82   543.5 2684.71   548.1  2690.4
   552.7 2702.42   557.3 2709.44   571.1 2718.73   625.3 2747.25   665.8 2771.96
   683.9  2778.5   703.4 2792.75   742.5 2814.76   751.5 2817.54   760.1 2822.85
#Mann= 9 ,-1,0
       0     .06       0      80     .05       0  282.73      .1       0
  402.73     .05       0  415.87    .045       0  451.75     .05       0
  452.73      .1       0  512.73     .06       0  621.85      .1       0
Bank Sta=415.87,451.75
XS Rating Curve= 0 ,0
Exp/Cntr=0.3,0.1

Type RM Length L Ch R = 1 ,123515  ,68.3,68.3,68.3
BEGIN DESCRIPTION:
structure
END DESCRIPTION:
XS GIS Cut Line= 4
 2239151.3930537544354.338548718 2238911.1216494544801.094571824
2239017.13191452544970.7700363542239128.53666432545133.574731318
#Sta/Elev= 30
       0 2736.62    74.4 2720.54      99 2709.18   131.5 2711.96     176  2707.6
     201 2703.35   221.2 2696.51   249.6 2690.39   298.4 2686.99   378.4 2685.48
   394.3 2683.46   454.4 2683.92     480 2681.75   601.7 2681.33   611.1 2679.83
  620.082675.733   625.3 2675.12   655.1 2675.74     663 2676.28   676.5 2683.16
   681.9 2684.13   724.8 2683.43   728.5 2688.92   734.5 2701.04   744.2 2711.91
     749 2715.55   781.7 2729.02   841.1 2760.63   865.4 2770.73   904.6 2796.26
#Mann= 12 ,-1,0
       0     .06       0      60     .05       0     270     .07       0
     280     .05       0     480     .07       0  507.27     .06       0
  537.27     .07       0  620.08    .045       0   655.1     .07       0
  727.34     .08       0  737.34     .06       0  857.34      .1       0
Bank Sta=620.08,655.1
XS Rating Curve= 0 ,0
Exp/Cntr(USF)=0,0
Exp/Cntr=0.3,0.1

Type RM Length L Ch R = 1 ,123447  ,109.9,109.9,109.9
BEGIN DESCRIPTION:
structure
END DESCRIPTION:
XS GIS Cut Line= 4
2239067.68868259544347.2036784042238827.41727829 544793.95970151
2238933.42754341544963.6351660392239044.83229321545126.439861004
#Sta/Elev= 30
       0 2704.67    27.7 2703.23    48.4 2698.22   152.1 2694.04   176.3  2691.1
   229.3  2692.1   379.2 2688.22   396.9 2687.12   421.2 2680.66     450 2681.06
   479.6 2685.39   515.8 2684.56     545 2682.23   553.5 2678.33   561.5 2677.67
   600.1 2679.35   652.1 2678.79   666.9 2675.17   690.3 2674.47   704.4 2674.13
  714.912674.468   733.4 2683.75   777.1 2682.97   781.9 2686.98     791 2703.76
   802.5 2717.57   820.7 2725.45   840.1 2731.06   897.5 2764.05   904.6 2766.56
#Mann= 11 ,-1,0
       0     .06       0      70     .05       0     100     .07       0
     290     .05       0     300     .06       0     400     .07       0
  507.27     .05       0  517.27     .06       0   690.3    .045       0
  714.91     .07       0  867.34      .1       0
Bank Sta=690.3,714.91
XS Rating Curve= 0 ,0
Exp/Cntr(USF)=0,0
Exp/Cntr=0.3,0.1

Type RM Length L Ch R = 1 ,123337  ,200.7,200.7,200.7
XS GIS Cut Line= 4
2238643.80029257544560.3191057672238810.86063214 544974.60409086
2238879.81262096545085.3860860842238978.06723257 545233.93987749
#Sta/Elev= 30
       0 2724.12    26.8 2713.02    40.9 2711.21      57 2704.01    74.2 2698.61
   113.1 2691.83   203.8 2689.19   246.8 2683.31   308.3 2679.78     346 2680.81
   410.7 2678.14   432.2 2680.65   449.2 2677.14   455.3  2678.2   463.9 2674.18
  471.232672.876   487.3 2671.38   501.6 2671.52  504.812672.874     511 2678.01
   519.2 2681.18   577.2 2683.31   583.1  2689.1     586 2694.81   591.3 2711.03
   596.1 2715.19   624.9 2725.78   675.4 2749.45   704.3  2759.9   755.3 2787.83
#Mann= 6 ,-1,0
       0      .1       0     230     .05       0     370     .07       0
  471.23    .045       0  504.81     .07       0  587.19      .1       0
Bank Sta=471.23,504.81
XS Rating Curve= 0 ,0
Exp/Cntr(USF)=0,0
Exp/Cntr=0.3,0.1

Type RM Length L Ch R = 1 ,123136  ,502.1,502.1,502.1
XS GIS Cut Line= 4
     2238382.448      544763.934      2238665.65      545120.147
2238737.46690496545211.812802179 2238867.5339125545309.434197129
#Sta/Elev= 30
       0 2742.99    19.2 2731.48    37.4 2725.51    60.6 2713.11    92.8 2700.12
   165.1 2678.23   214.9 2675.52   287.8 2676.06   323.5 2674.49   375.6 2675.91
   406.4 2674.38   420.6 2677.44  437.952670.495   446.2 2668.66   466.2 2668.73
  475.172670.494   483.2 2673.02   504.6 2672.19   514.6 2676.49   532.6 2681.46
   568.7 2678.57   571.6  2681.4   574.9 2688.16   578.2 2692.69   589.9 2704.28
   619.9 2711.72   640.4 2718.43   689.9 2737.56   720.1 2751.69   734.1 2755.35
#Mann= 8 ,-1,0
       0      .1       0     170     .07       0     250     .05       0
     300     .07       0  437.95    .045       0  475.17     .07       0
  545.07     .06       0  565.07      .1       0
Bank Sta=437.95,475.17
XS Rating Curve= 0 ,0
Exp/Cntr=0.3,0.1

Type RM Length L Ch R = 1 ,122634  ,502.5,502.5,502.5
XS GIS Cut Line= 4
2237948.09621265545322.6059259672238227.32265511545381.399487684
2238341.07324783545510.204313206     2238837.503      545592.967
#Sta/Elev= 30
       0 2869.09    69.6 2817.91   130.9 2776.49   143.2 2773.55   188.1 2745.93
   208.6 2736.04   220.8 2727.53   231.9 2722.05   249.4 2707.74     274 2684.29
   297.1 2666.72   308.5 2666.87   322.9 2664.08   343.8 2664.77   359.5 2663.19
   386.4 2664.71   407.7 2667.97   561.7 2666.72   671.2 2668.22   699.6 2670.35
   719.9 2679.56   752.3 2677.85   756.4    2679   776.6 2695.25   809.1 2704.74
   829.4 2708.29   858.7 2717.72   886.1 2730.49   894.2 2732.34   960.5 2759.46
#Mann= 6 ,-1,0
       0      .1       0   343.8    .045       0   386.4      .1       0
  557.19     .08       0  657.19     .06       0  757.19      .1       0
#XS Ineff= 2 , 0
                          413.45          2690.1
Permanent Ineff=
       F       F
Bank Sta=343.8,386.4
XS Rating Curve= 0 ,0
Exp/Cntr=0.3,0.1

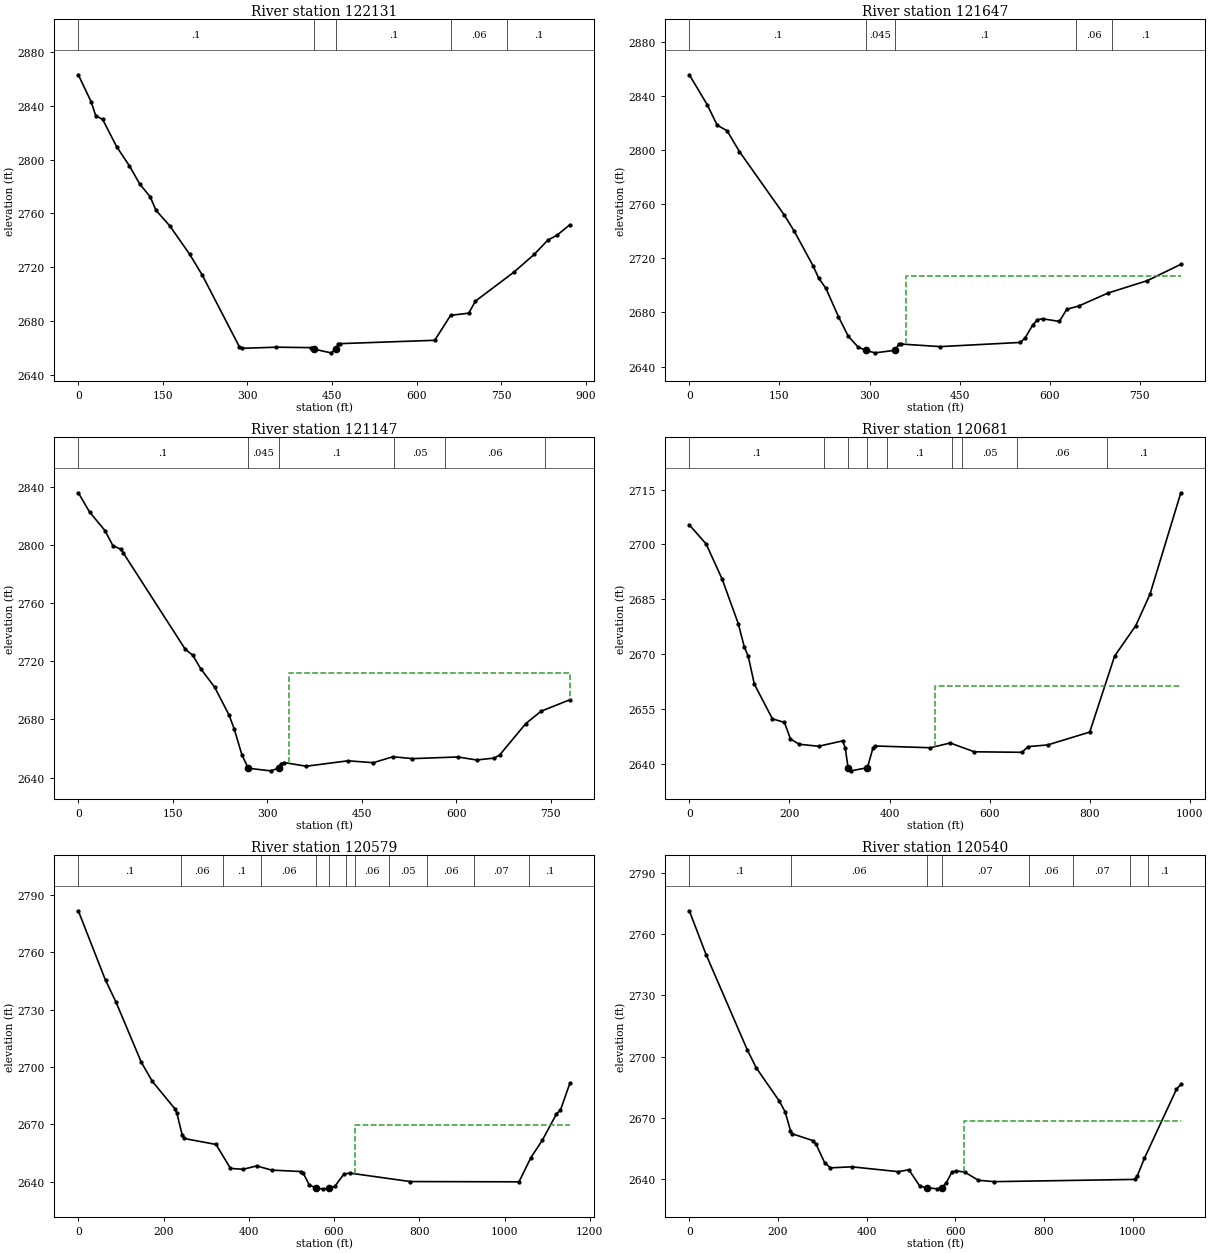
Type RM Length L Ch R = 1 ,122131  ,484.1,484.1,484.1
XS GIS Cut Line= 4
2238002.06194242545992.213133187 2238281.7820156 545926.42603762
2238512.63820048545821.9599861692238843.22974154 545805.39001802
#Sta/Elev= 30
       0 2863.03    22.7 2843.03    30.9 2832.65    43.3 2829.79    67.9 2809.63
    90.8 2795.22     109 2781.78   127.4 2772.36   137.8 2762.27   162.4 2750.61
   197.6 2729.51     220 2713.97   285.7  2660.8   290.1 2659.65   351.4 2660.48
   412.9 2660.15  418.372658.993     448 2656.28  456.732658.994   461.2 2662.58
     465 2663.13   632.2 2665.61   660.4 2684.18   692.5 2685.77   704.5 2694.79
   772.6 2716.26   808.6 2729.46   832.6 2740.02   848.7 2743.64   871.8 2751.48
#Mann= 5 ,-1,0
       0      .1       0  418.37    .045       0  456.73      .1       0
  660.74     .06       0  760.74      .1       0
Bank Sta=418.37,456.73
XS Rating Curve= 0 ,0
Exp/Cntr=0.3,0.1

Type RM Length L Ch R = 1 ,121647  ,500.7,500.7,500.7
XS GIS Cut Line= 4
2238099.05537569546394.9591824632238366.08074746 546329.80223848
2238553.95500174546316.6586269392238902.92037094546251.457388279
#Sta/Elev= 30
       0 2855.91      30 2833.57    46.4 2818.62    62.9 2814.47    83.5 2799.01
     158 2752.18   174.1 2740.58   206.1 2714.43   215.3 2705.49   227.5 2697.79
   248.2 2676.91   264.7 2662.35     281 2654.42  293.652651.946     309 2650.14
  341.582651.949   349.1 2656.52   353.1 2656.64   417.3 2654.75   550.9 2657.83
     559  2661.2   571.7 2670.76   579.4 2674.66   588.1 2675.37     616 2673.37
   628.2 2682.33   648.6 2684.87   697.4 2694.46   762.5 2703.58   818.2 2715.64
#Mann= 5 ,-1,0
       0      .1       0  293.65    .045       0  341.58      .1       0
  643.19     .06       0  703.19      .1       0
#XS Ineff= 2 , 0
                          360.74         2707.27
Permanent Ineff=
       F       F
Bank Sta=293.65,341.58
XS Rating Curve= 0 ,0
Exp/Cntr=0.3,0.1

Type RM Length L Ch R = 1 ,121147  ,465.4,465.4,465.4
XS GIS Cut Line= 4
2238266.73693147546874.5087494482238522.88783124546816.513747307
2238720.06175018546721.8830557792238965.72299007546552.078871693
#Sta/Elev= 30
       0 2835.97    17.9 2822.72    42.5 2809.87    54.8 2799.61    67.1  2797.2
    71.2 2794.71   169.6 2728.36   181.9    2724   194.2 2714.93   216.3 2702.24
   239.3 2682.95   247.5 2673.34   259.6 2655.67  269.672646.392   305.1 2644.62
  317.792646.395   321.7 2649.56   326.2 2650.34   361.7  2647.8     428 2651.53
   468.2 2650.22   499.2 2654.33   530.1 2653.02   602.2 2654.17   632.2 2652.11
   660.2  2653.4   668.8 2655.58     710 2677.09   734.3 2685.64     780 2693.52
#Mann= 6 ,-1,0
       0      .1       0  269.67    .045       0  317.79      .1       0
  501.34     .05       0  581.34     .06       0  741.34      .1       0
#XS Ineff= 2 , 0
                          334.51         2712.02
Permanent Ineff=
       F       F
Bank Sta=269.67,317.79
XS Rating Curve= 0 ,0
Exp/Cntr=0.3,0.1

Type RM Length L Ch R = 1 ,120681  ,102.7,102.7,102.7
XS GIS Cut Line= 4
2238466.70133151547240.6612174782238771.23027192547217.342102869
2239137.13084445546878.2185109282239258.34473789546748.126893143
#Sta/Elev= 30
       0 2705.36    33.6 2700.12    65.7 2690.47    97.8 2678.33   109.8 2671.97
   117.8 2669.36   129.9 2661.78     166 2652.29     190  2651.3   202.1 2646.78
   219.4 2645.34   258.2 2644.78   306.2 2646.26   311.5  2644.4  317.172638.928
   323.1 2638.06   355.8 2638.92   366.7 2644.19   371.3 2644.86   481.7 2644.38
   521.3 2645.68   569.4 2643.27   664.6 2643.13     677 2644.69   715.7 2645.14
     800 2648.66   849.8 2669.46   892.1  2677.8   920.3 2686.32   982.1 2714.13
#Mann= 9 ,-1,0
       0      .1       0     270     .06       0  317.17    .045       0
   355.8     .06       0  395.42      .1       0  525.42     .06       0
  545.42     .05       0  655.42     .06       0  834.31      .1       0
#XS Ineff= 2 , 0
                           491.7         2661.38
Permanent Ineff=
       F       F
Bank Sta=317.17,355.8
XS Rating Curve= 0 ,0
Exp/Cntr=0.3,0.1

Type RM Length L Ch R = 1 ,120579  ,38.6,38.6,38.6
BEGIN DESCRIPTION:
structure
END DESCRIPTION:
XS GIS Cut Line= 4
2238640.14426148547687.6680369792238725.79139645547277.798308412
2239212.12041523 547231.994042862239396.64566516547069.519301045
#Sta/Elev= 30
       0 2781.73    63.8 2745.38    88.4 2733.97   147.8 2702.46   173.6 2692.47
   227.3 2677.91   231.4 2675.66   243.6  2664.5   247.7 2662.57   323.2 2659.43
     357 2646.89   386.7 2646.44   418.7 2648.19   453.3 2646.01   521.6 2645.26
     528 2644.26   541.6 2638.34558.68872636.423   573.8  2636.2  588.272636.423
   601.9 2637.54   623.4 2644.02     638 2644.41   778.7 2640.01  1033.9 2639.87
  1061.8 2652.56  1088.5 2661.59  1121.8  2675.4  1131.1 2677.41  1153.1 2691.37
#Mann= 12 ,-1,0
       0      .1       0     240     .06       0     340      .1       0
  428.72     .06       0558.6887    .045       0  588.27     .06       0
  628.72     .07       0  648.72     .06       0  728.72     .05       0
  818.72     .06       0   927.2     .07       0  1057.2      .1       0
#XS Ineff= 2 , 0
                          648.09         2669.66
Permanent Ineff=
       F       F
Bank Sta=558.6887,588.27
XS Rating Curve= 0 ,0
Exp/Cntr(USF)=0,0
Exp/Cntr=0.3,0.1

Type RM Length L Ch R = 1 ,120540  ,385,385,385
BEGIN DESCRIPTION:
structure
END DESCRIPTION:
XS GIS Cut Line= 4
2238676.62128997 547674.355923642238737.57047159547303.015002302
2239223.89949036547257.2107367492239417.22709087 547108.33962764
#Sta/Elev= 30
       0 2771.32    37.7 2749.92   130.9 2703.21   151.2 2694.41   202.6 2678.35
     216 2673.04   228.2 2663.82   232.2 2662.22   279.2 2658.87   286.2 2656.99
   305.2 2648.13   318.3 2645.56     366 2646.08   471.3 2643.71   495.4 2644.62
   519.9 2636.62   535.6 2635.85   559.7  2635.3   569.32635.851   579.8 2638.24
   591.9 2643.33   600.7  2644.1   621.1  2643.5   652.1 2639.48   688.3 2638.82
  1004.8 2639.91  1010.5 2641.59  1026.7 2650.29  1098.9 2683.99  1108.8 2686.46
#Mann= 8 ,-1,0
       0      .1       0     230     .06       0   535.6    .045       0
   569.3     .07       0  766.31     .06       0  864.79     .07       0
  994.79     .05       0 1034.79      .1       0
#XS Ineff= 2 , 0
                          619.49         2668.55
Permanent Ineff=
       F       F
Bank Sta=535.6,569.3
XS Rating Curve= 0 ,0
Exp/Cntr(USF)=0,0
Exp/Cntr=0.3,0.1

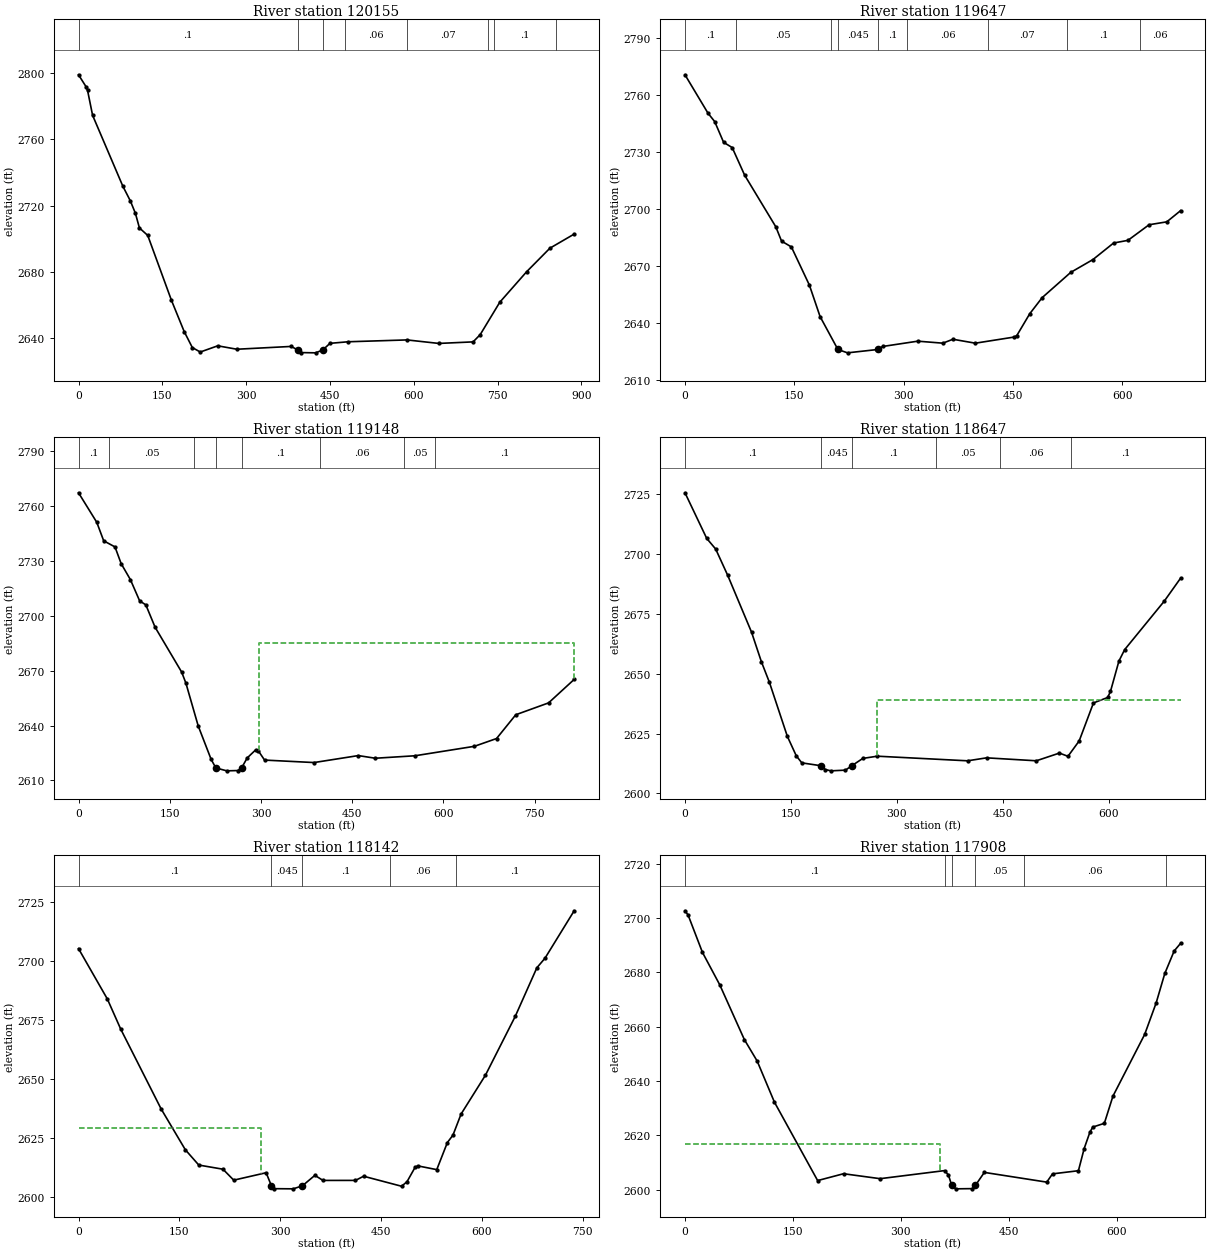
Type RM Length L Ch R = 1 ,120155  ,508.2,508.2,508.2
XS GIS Cut Line= 4
2238991.62560007547847.5684016522239082.24781292 547672.61913343
2239404.85480837547269.0161334922239505.33537213547127.750812238
#Sta/Elev= 30
       0 2798.82    14.1 2791.31    16.2  2789.4    25.2  2774.4    79.3 2731.74
    92.8 2722.82   101.8  2715.4     109 2706.57   123.9 2702.05   166.4 2662.91
   189.1 2644.17   203.7 2634.51   217.9 2631.82   249.2 2635.56   283.4  2633.5
   380.7 2635.19   392.3 2633.07   398.7 2631.48   424.3 2631.33  437.182633.046
     450 2637.05   482.6    2638   587.9 2639.11   644.8    2637   706.2 2637.93
   718.9 2642.28     754 2661.82     802 2680.18   843.7 2694.37   887.1 2702.86
#Mann= 8 ,-1,0
       0      .1       0   392.3    .045       0  437.18      .1       0
  477.03     .06       0  587.03     .07       0  733.72     .05       0
  743.72      .1       0  853.72     .08       0
Bank Sta=392.3,437.18
XS Rating Curve= 0 ,0
Exp/Cntr=0.3,0.1

Type RM Length L Ch R = 1 ,119647  ,498.7,498.7,498.7
XS GIS Cut Line= 4
2239483.74190123 548016.832567132239583.22864065547837.469209767
2239677.20561636547628.341926005     2239774.709      547402.845
#Sta/Elev= 30
       0 2770.61    31.6 2750.38    40.8 2745.96      53 2735.05    64.8 2732.29
    81.9 2717.73   124.6  2690.6   132.5 2683.06     146 2679.98   170.7 2659.89
   185.4  2643.3  209.822626.005     223 2624.23   264.82626.005   271.2 2627.58
   319.4 2630.37   353.8 2629.32   367.7 2631.38   398.4 2629.31   451.9 2632.55
   455.3 2633.32   473.1 2644.83   490.1 2653.29   529.3 2666.58   559.8 2673.34
   588.1 2682.04   607.8 2683.45   636.8 2691.66   661.1 2693.19   680.1  2699.1
#Mann= 9 ,-1,0
       0      .1       0      70     .05       0     200      .1       0
  209.82    .045       0   264.8      .1       0  305.11     .06       0
  415.11     .07       0  524.38      .1       0  624.38     .06       0
Bank Sta=209.82,264.8
XS Rating Curve= 0 ,0
Exp/Cntr=0.3,0.1

Type RM Length L Ch R = 1 ,119148  ,500.5,500.5,500.5
XS GIS Cut Line= 4
2239764.81915424548267.8962627272239936.37967641548134.406095943
2240116.54194407548029.8547212252240339.21831568547710.667219029
#Sta/Elev= 30
       0 2767.27      30 2751.15    41.4 2741.01      60 2737.67    70.1 2728.54
    85.3  2719.8   100.5 2708.19   110.7 2705.99   125.9 2693.78   169.6 2669.24
   176.6 2663.17   196.8 2639.81   218.1 2621.49  225.792616.865   243.7 2615.27
     262 2615.43  268.132616.864   277.3 2622.31   291.3 2626.74   295.8 2626.12
   305.9 2621.15   387.2  2619.8     460 2623.61     488 2622.16   553.3 2623.51
   650.9 2628.68   687.3 2632.93   718.9 2645.93   772.8 2652.41   814.9 2665.24
#Mann= 8 ,-1,0
       0      .1       0      50     .05       0     190      .1       0
  225.79    .045       0  268.13      .1       0  397.38     .06       0
  535.68     .05       0  585.68      .1       0
#XS Ineff= 2 , 0
                          296.03         2685.34
Permanent Ineff=
       F       F
Bank Sta=225.79,268.13
XS Rating Curve= 0 ,0
Exp/Cntr=0.3,0.1

Type RM Length L Ch R = 1 ,118647  ,505.5,505.5,505.5
XS GIS Cut Line= 4
2239979.08276176548629.8207076932240126.70687169548578.833722681
2240489.12494049 548498.679797272240663.23425055 548513.63115912
#Sta/Elev= 30
       0 2725.62    30.8 2706.56    43.5 2702.11    60.4 2691.22    94.3 2667.38
   108.3 2654.98   119.6 2646.44     145 2623.87   157.7 2615.71   165.5 2612.79
  193.242611.565   198.7    2610   206.8 2609.46   227.3 2609.75  236.172611.565
   251.9 2614.65   272.4 2615.58   400.3 2613.65   427.2 2614.89   497.7 2613.66
   530.4 2616.88   542.5 2615.53   558.4 2621.96   578.6 2637.82   598.7  2640.1
   602.7 2642.61   614.7 2655.33   622.8 2660.09     679 2680.38   702.1 2689.97
#Mann= 6 ,-1,0
       0      .1       0  193.24    .045       0  236.17      .1       0
  356.18     .05       0  446.18     .06       0  547.36      .1       0
#XS Ineff= 2 , 0
                          272.43         2639.18
Permanent Ineff=
       F       F
Bank Sta=193.24,236.17
XS Rating Curve= 0 ,0
Exp/Cntr=0.3,0.1

Type RM Length L Ch R = 1 ,118142  ,234.1,234.1,234.1
XS GIS Cut Line= 4
2239949.24204268549070.8249511662240202.34029168549072.018986349
2240478.46647154549039.3685167422240683.33332565549016.390239644
#Sta/Elev= 30
       0 2705.17    42.9 2683.86    62.9 2671.06   122.9 2637.37   158.9 2620.11
   178.9 2613.64   214.9 2611.88   230.9 2607.25   279.1 2610.39   286.82604.978
   291.2 2603.65   319.4 2603.58     333 2604.86   351.6 2609.28   363.7 2607.14
     412 2607.15   424.1 2608.91   480.5 2604.68   488.6 2606.57   500.6 2612.65
   504.7 2613.29   532.9  2611.7   548.7 2623.17     557 2626.29   569.1 2635.22
   605.3 2651.63   649.6 2676.49   681.8 2697.06   693.9 2701.11   737.3 2721.17
#Mann= 5 ,-1,0
       0      .1       0   286.8    .045       0     333      .1       0
   463.1     .06       0  561.15      .1       0
#XS Ineff= 2 , 0
          272.06 2629.21
Permanent Ineff=
       F       F
Bank Sta=286.8,333
XS Rating Curve= 0 ,0
Exp/Cntr=0.3,0.1

Type RM Length L Ch R = 1 ,117908  ,131.3,131.3,131.3
XS GIS Cut Line= 6
2239947.89854665549299.3982679942240123.37757894549299.398267994
2240298.85661124549304.9690309242240358.57951264549268.560895773
2240455.38456341549268.7193553862240626.21386601549268.116620797
#Sta/Elev= 30
       0 2702.67     4.3 2701.13    24.3 2687.34    48.3 2675.43    82.5 2655.26
   100.3 2647.36   124.3 2632.22   184.3 2603.37   220.3 2605.89   271.1 2604.07
   360.6 2607.04     366 2605.45  370.51 2601.65     376 2600.33   399.4 2600.41
   403.6 2601.65   415.9 2606.38   502.6  2602.8   510.6 2605.84   546.6    2607
   554.6 2615.17   562.6 2621.21   566.6 2623.07   582.6 2624.44   594.6 2634.47
   638.6 2657.14   654.6 2668.76   666.6 2679.59   679.6 2687.87   688.6 2690.71
#Mann= 6 ,-1,0
       0      .1       0  361.05     .05       0  370.51    .045       0
   403.6     .05       0  470.99     .06       0   667.8      .1       0
#XS Ineff= 2 , 0
          353.79 2616.97
Permanent Ineff=
       F       F
Bank Sta=370.51,403.6
XS Rating Curve= 0 ,0
Exp/Cntr(USF)=0,0
Exp/Cntr=0.3,0.1

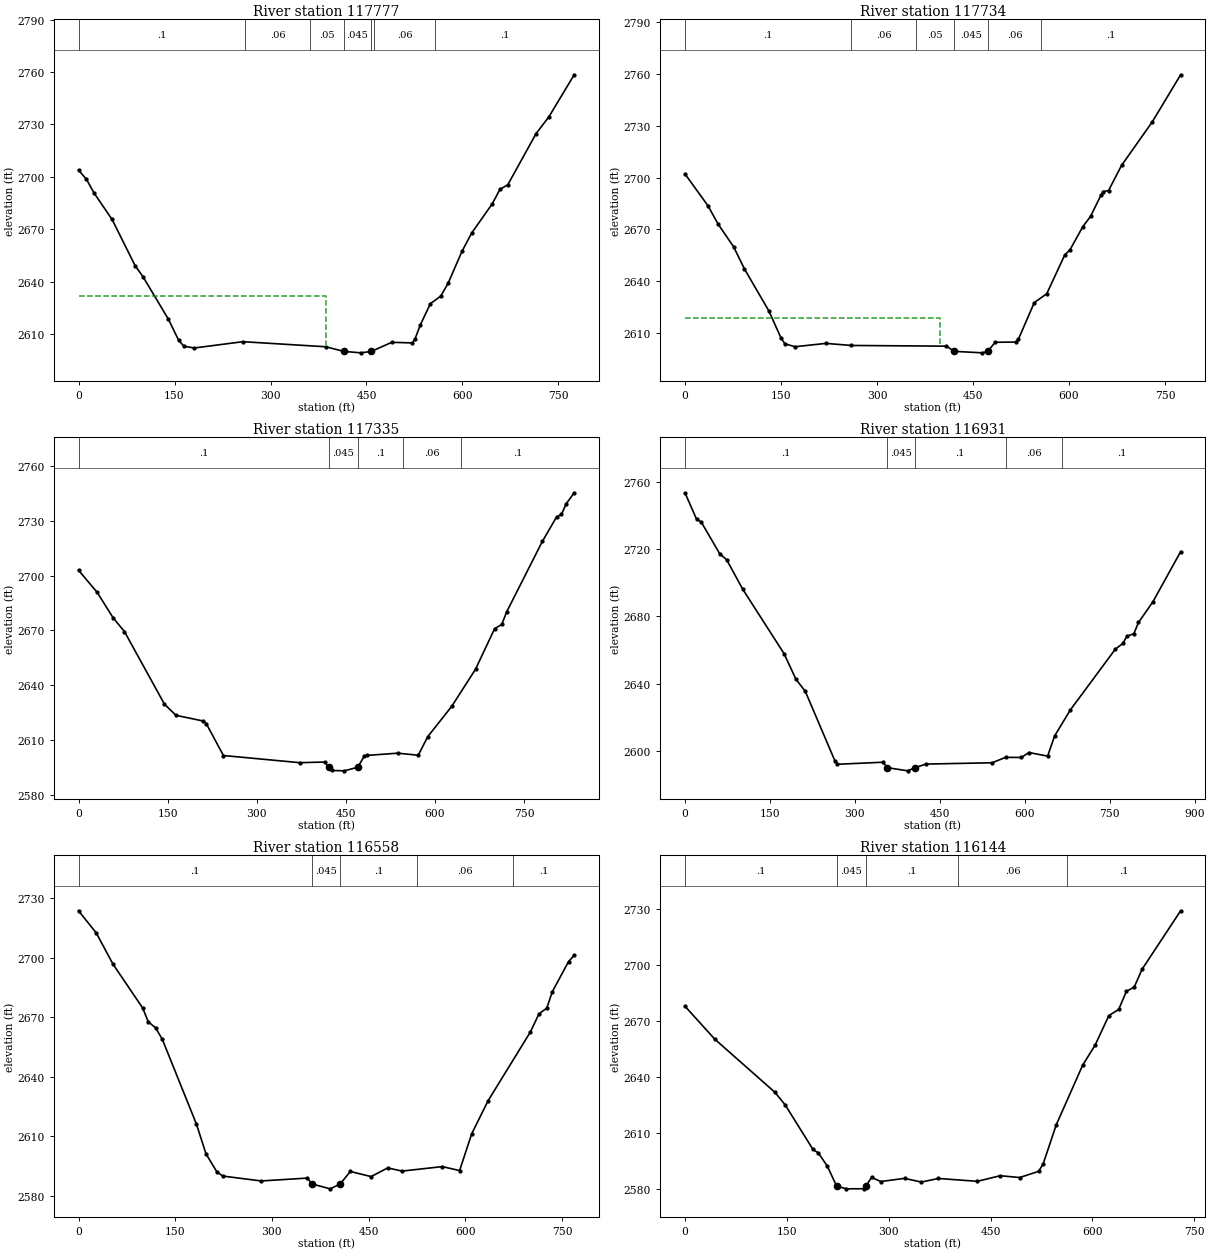
Type RM Length L Ch R = 1 ,117777  ,42.4,42.4,42.4
BEGIN DESCRIPTION:
structure
END DESCRIPTION:
XS GIS Cut Line= 4
2239951.76972527549433.0728036842240302.72778987549413.575133429
2240447.56762605549400.5766865922240723.32039108549432.144343196
#Sta/Elev= 30
       0 2703.83    12.4 2698.61    24.4 2690.68    52.5 2675.57    88.5 2649.08
   100.6  2642.9   140.5 2618.43   156.6 2606.27   164.7 2603.02   180.7 2601.97
   256.8 2605.58   386.4 2602.68   414.4 2600.03   441.3  2599.2   457.4    2600
   489.5 2605.22   521.7 2604.89   525.7 2607.07   534.1  2615.2   549.9  2627.4
     566 2631.67   577.5 2639.01   599.2 2657.32   614.3  2667.8   646.5 2684.55
   658.6 2692.86   670.7  2695.4   714.9 2724.71   735.1 2734.44   774.5 2758.45
#Mann= 7 ,-1,0
       0      .1       0     260     .06       0   361.5     .05       0
   414.4    .045       0   457.4     .05       0   461.5     .06       0
  556.92      .1       0
#XS Ineff= 2 , 0
             387 2631.52
Permanent Ineff=
       F       F
Bank Sta=414.4,457.4
XS Rating Curve= 0 ,0
Exp/Cntr(USF)=0,0
Exp/Cntr=0.3,0.1

Type RM Length L Ch R = 1 ,117734  ,399.6,399.6,399.6
BEGIN DESCRIPTION:
structure
END DESCRIPTION:
XS GIS Cut Line= 4
2239948.44021827549475.4598528632240299.39828287549455.962182608
2240444.23811905549442.9637357712240719.99088408549474.531392375
#Sta/Elev= 30
       0 2702.15    35.8 2683.82    51.8  2673.1    75.9 2660.04      93 2647.12
     131  2622.9   149.9 2607.33     156 2603.83     172 2602.13   220.1 2604.06
     260 2602.86   408.5 2602.46   420.6 2599.46   464.7 2598.59  472.942599.462
   484.8 2604.71   516.9 2604.82     521 2606.44   545.8 2627.67   565.3 2632.82
   593.5 2655.31   601.5 2658.16   621.6  2671.6   633.7 2677.58   649.9 2689.77
   653.9 2691.95   661.9 2692.55   682.1 2707.05   730.1 2732.26   774.5 2759.56
#Mann= 6 ,-1,0
       0      .1       0     260     .06       0   361.5     .05       0
   420.6    .045       0  472.94     .06       0  556.92      .1       0
#XS Ineff= 2 , 0
          398.13 2618.49
Permanent Ineff=
       F       F
Bank Sta=420.6,472.94
XS Rating Curve= 0 ,0
Exp/Cntr(USF)=0,0
Exp/Cntr=0.3,0.1

Type RM Length L Ch R = 1 ,117335  ,403.8,403.8,403.8
XS GIS Cut Line= 4
2239921.24291973549634.1793500372240109.10016914549777.962813687
2240424.63573438549865.7364721222240693.53947632 549890.57162859
#Sta/Elev= 30
       0 2703.01    31.3  2690.9    58.4 2676.84    77.3 2669.37   144.7  2629.5
     164 2623.43   210.2 2620.28   215.3 2618.69   243.9 2601.38   372.6 2597.45
   414.1 2597.81  421.042594.969   426.6 2593.19   447.4 2592.98  469.982594.967
   480.6 2600.89   485.3 2601.44   537.3 2602.67   571.7 2601.53   587.7 2611.74
   627.9 2628.28   668.1  2648.7   700.2 2670.94   712.3 2673.28   720.3 2680.03
   780.5 2718.78   804.6 2732.29   812.7  2733.6   820.7 2739.43   834.1 2745.48
#Mann= 5 ,-1,0
       0      .1       0  421.04    .045       0  469.98      .1       0
  546.57     .06       0  644.08      .1       0
Bank Sta=421.04,469.98
XS Rating Curve= 0 ,0
Exp/Cntr=0.3,0.1

Type RM Length L Ch R = 1 ,116931  ,373.3,373.3,373.3
XS GIS Cut Line= 4
2239844.11668547550266.9183113512240101.75411819550215.581336262
2240404.29007409550238.7697840972240704.55663883550166.595621489
#Sta/Elev= 30
       0 2753.59    20.5 2737.83    28.6 2736.24    61.2 2717.35    73.5 2713.74
     102 2696.14     175 2657.74   195.8 2642.61   212.4 2635.35   265.1 2593.61
   269.1 2591.94   349.4 2593.16  357.132589.924   393.5 2588.03  405.822589.926
   425.6 2592.06   542.2 2592.84     566 2596.06   593.9 2595.99   607.1 2598.94
   640.1 2596.78   652.4 2608.77   680.1 2624.25   759.7 2660.51     773  2663.9
   779.9 2668.15   792.3 2669.66   800.5 2676.36   826.1 2688.77   874.9 2718.54
#Mann= 5 ,-1,0
       0      .1       0  357.13    .045       0  405.82      .1       0
  566.13     .06       0  666.13      .1       0
Bank Sta=357.13,405.82
XS Rating Curve= 0 ,0
Exp/Cntr=0.3,0.1

Type RM Length L Ch R = 1 ,116558  ,413.7,413.7,413.7
XS GIS Cut Line= 4
 2240048.4327375 550719.588740262240226.46420289550599.771412416
 2240567.2315836550431.7738248592240732.43805354550376.200376741
#Sta/Elev= 30
       0 2723.57    27.5 2712.42    53.4 2696.71    99.5 2674.58   108.1 2667.68
   119.7 2664.49   129.9 2658.84   182.9 2616.06   197.7  2601.1   214.6 2591.99
   223.8 2589.87   283.5  2587.4   354.8 2588.85  362.032585.896   390.4 2583.43
  405.972585.896   421.6 2592.18   453.8 2589.61   479.6 2593.97   501.9 2592.38
   564.3 2594.63   591.1 2592.64   609.9 2611.19   635.2 2627.79     701 2662.55
   714.2 2671.65   726.3 2674.48   734.8 2682.72   760.1 2697.98   768.8 2701.07
#Mann= 5 ,-1,0
       0      .1       0  362.03    .045       0  405.97      .1       0
   524.6     .06       0  674.52      .1       0
Bank Sta=362.03,405.97
XS Rating Curve= 0 ,0
Exp/Cntr=0.3,0.1

Type RM Length L Ch R = 1 ,116144  ,461.6,461.6,461.6
XS GIS Cut Line= 4
2240459.33983516 551057.677130992240589.70203974550890.307682945
2240768.98613141550649.5936533292240892.00979222550470.118604308
#Sta/Elev= 30
       0 2677.96    43.7 2660.32   132.5 2631.69   147.7 2624.87   188.2 2601.16
   196.6 2599.01   209.7 2591.96  223.292581.326   237.6 2579.82   263.3 2579.88
  266.332581.325   274.8 2585.94   288.4 2583.75   323.3 2585.44   348.2 2583.47
   373.2 2585.39   430.6 2583.86   464.1 2586.87   492.9  2585.9   520.6  2589.2
   527.3 2593.05   546.7 2614.18   585.5 2646.19   604.1 2657.15   624.2 2672.92
   638.6 2676.21   650.1 2685.97   661.6 2688.28   673.1 2697.81   729.9 2729.26
#Mann= 5 ,-1,0
       0      .1       0  223.29    .045       0  266.33      .1       0
  402.15     .06       0  562.29      .1       0
Bank Sta=223.29,266.33
XS Rating Curve= 0 ,0
Exp/Cntr=0.3,0.1