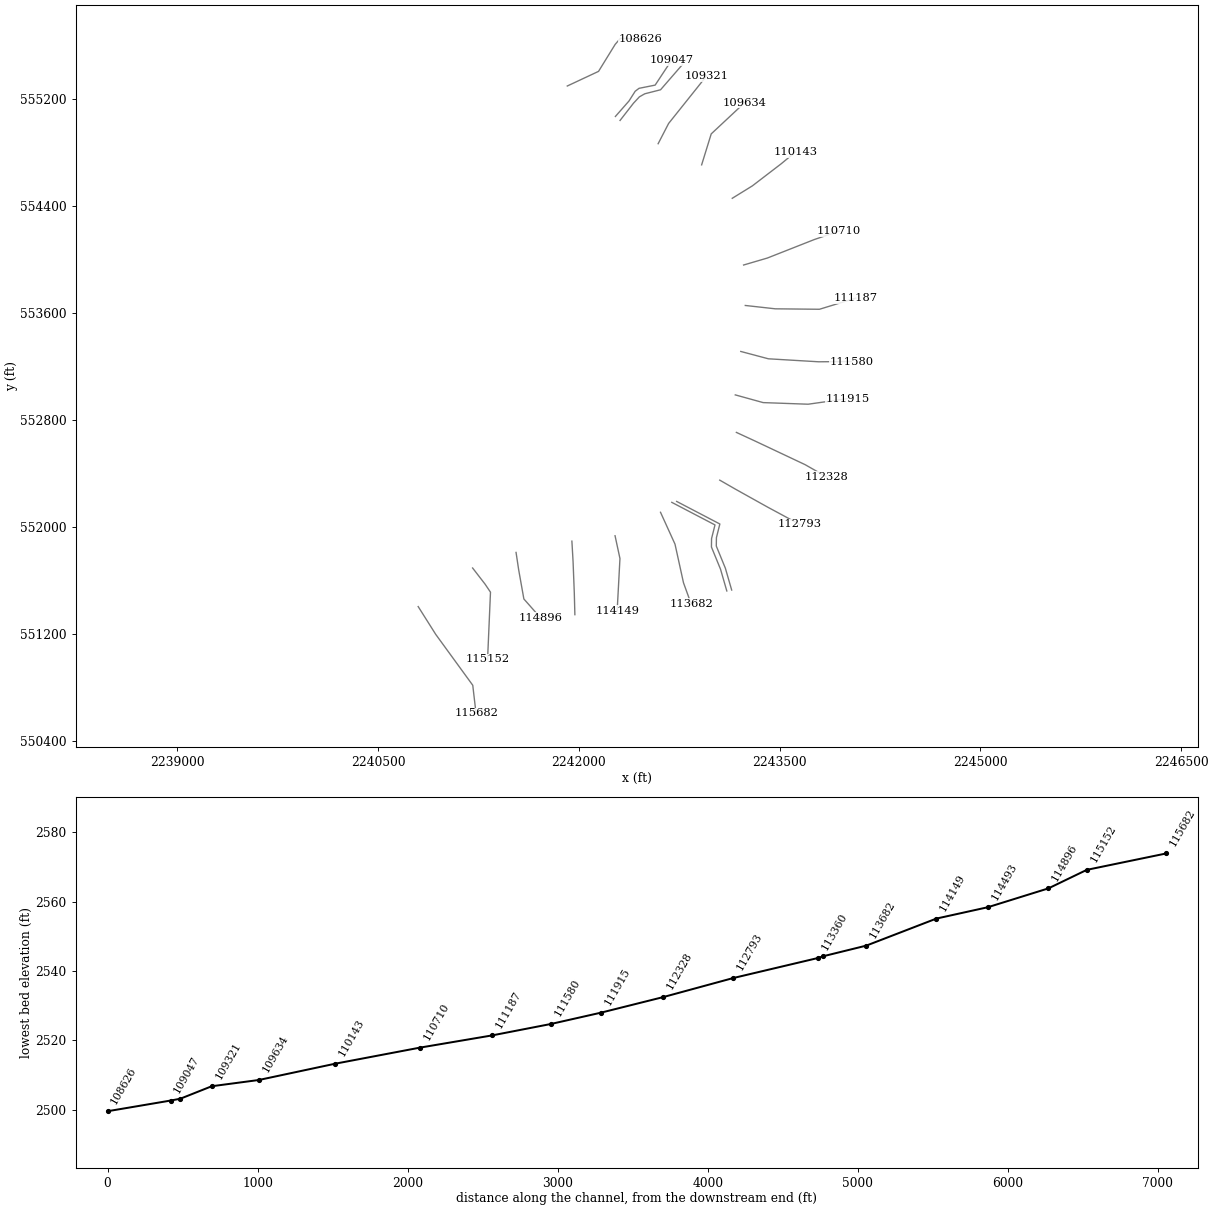
HEC-RAS study TYGVRV2.prj: TYGVRV2

--- TYGVRV2.g01 (geometry) --- (continued)

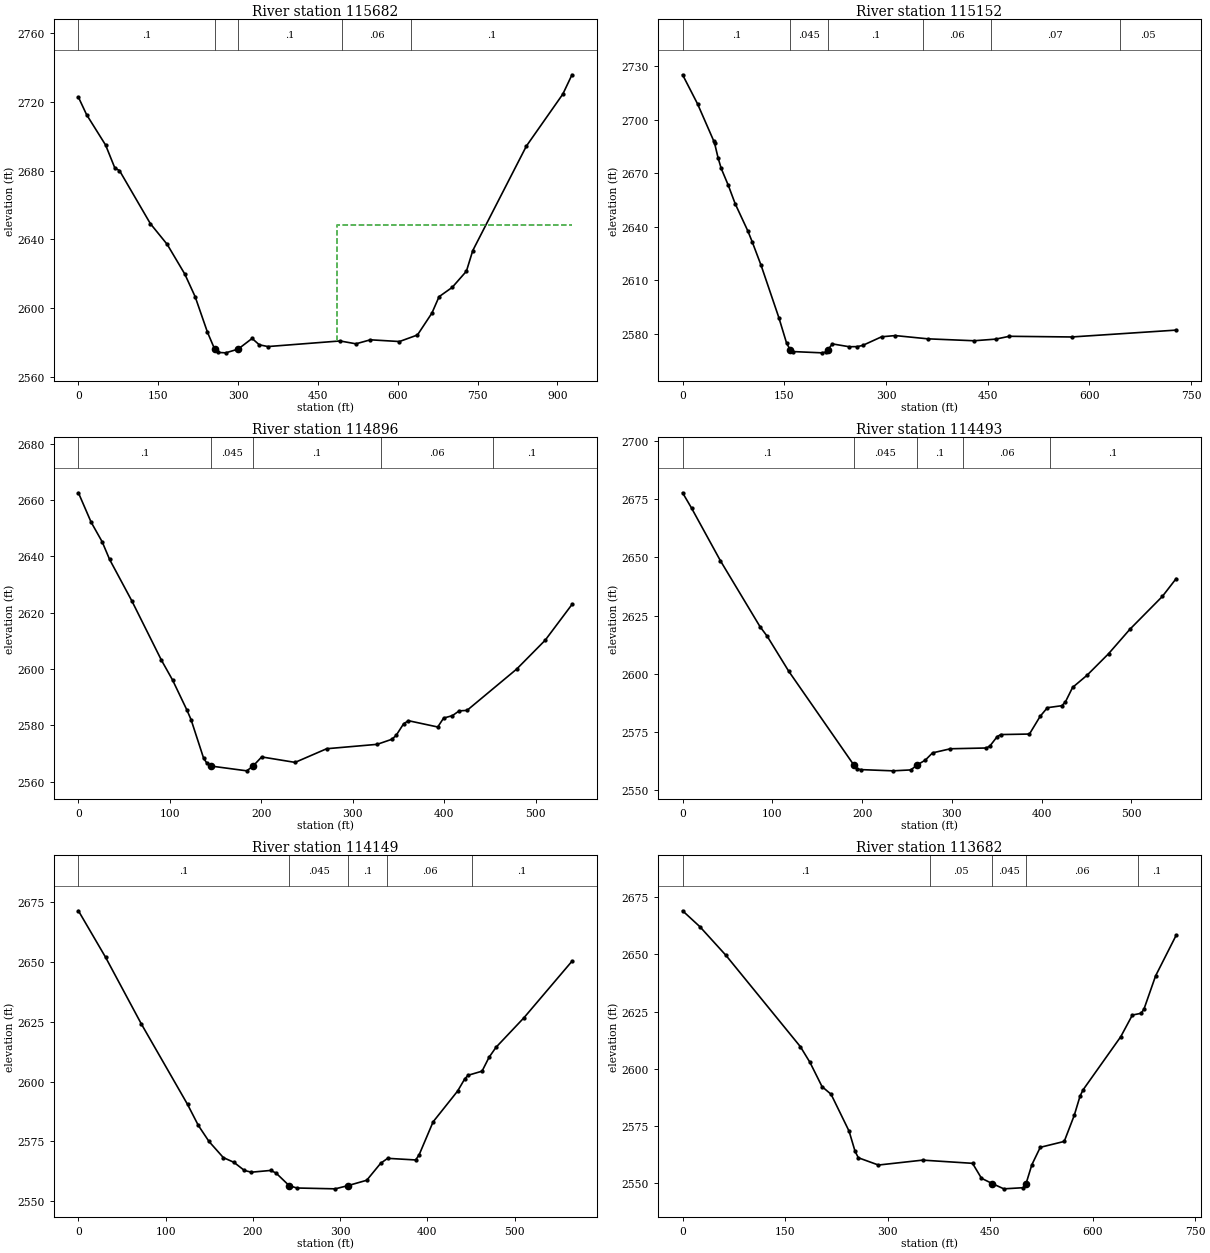
Type RM Length L Ch R = 1 ,115682  ,530.8,530.8,530.8
XS GIS Cut Line= 4
2240798.72650932551406.2013218652240929.85604885551198.499035071
2241206.60948452550818.1222064992241231.07360306550608.101638076
#Sta/Elev= 30
       0 2722.87    15.4 2712.67    51.1 2694.98    68.5 2681.59    77.2 2680.11
   135.2  2649.2   166.8 2637.14   199.9 2619.84   219.3  2606.7   242.5 2585.96
  255.982576.127   262.1 2574.18   276.9 2573.94  300.172576.125   326.4 2582.33
   339.9 2578.62   356.1  2577.6   491.6 2580.86   521.5  2579.2   548.7 2581.53
   603.3 2580.53   637.1 2584.34   664.3  2597.1   677.7 2606.64   702.4 2612.07
   729.1 2621.49   741.1 2633.55   841.8 2694.38   910.3 2724.67   927.5 2735.92
#Mann= 5 ,-1,0
       0      .1       0  255.98    .045       0  300.17      .1       0
  495.63     .06       0  625.63      .1       0
#XS Ineff= 2 , 0
                           485.2         2648.14
Permanent Ineff=
       F       F
Bank Sta=255.98,300.17
XS Rating Curve= 0 ,0
Exp/Cntr=0.3,0.1

Type RM Length L Ch R = 1 ,115152  ,255.3,255.3,255.3
XS GIS Cut Line= 4
2241205.39413592551694.5684054752241298.31131706 551574.26441556
2241339.08594412551513.8530586722241317.27354397551011.115836507
#Sta/Elev= 30
       0 2725.15      22 2708.88    45.7 2688.25    47.2 2686.76    52.3 2678.64
    56.9 2672.69    67.5 2663.08    77.6 2652.79    96.2  2637.6   102.7 2631.45
   115.8 2618.27     142 2588.95   153.3 2574.77   158.82570.835     163  2569.9
   205.4 2569.19   211.2 2569.64  214.182570.834   220.9 2574.21   245.6 2572.62
   257.6 2572.68   265.6 2573.34   293.6  2578.2   313.7 2578.87   361.7 2577.05
   429.8 2575.97   461.8 2576.88     482 2578.47   573.9 2578.09   728.1 2581.94
#Mann= 6 ,-1,0
       0      .1       0   158.8    .045       0  214.18      .1       0
  354.89     .06       0  454.89     .07       0  644.89     .05       0
Bank Sta=158.8,214.18
XS Rating Curve= 0 ,0
Exp/Cntr=0.3,0.1

Type RM Length L Ch R = 1 ,114896  ,403.3,403.3,403.3
XS GIS Cut Line= 4
2241530.14399217551810.901322118 2241549.5278221551682.164151344
2241588.50023766551463.2308756972241712.18101569551323.170153558
#Sta/Elev= 30
       0 2662.59    13.9 2652.15      26 2645.16    34.1 2638.91    58.4 2624.19
    90.7 2603.16   102.9  2596.1   118.7 2585.35   123.1 2582.04   136.8 2568.36
   140.2 2566.67  144.982565.544     184 2563.85  190.822565.546   200.3 2568.79
   236.8 2566.85   271.3  2571.7   326.5 2573.26   342.5 2575.05   347.2 2576.42
   355.3 2580.52   360.6 2581.66   392.7 2579.42   399.1 2582.58   408.7 2583.45
   416.1 2585.14   424.7 2585.32     479    2600   510.1 2610.23   539.4 2622.93
#Mann= 5 ,-1,0
       0      .1       0  144.98    .045       0  190.82      .1       0
  330.19     .06       0  452.56      .1       0
Bank Sta=144.98,190.82
XS Rating Curve= 0 ,0
Exp/Cntr(USF)=0,0
Exp/Cntr=0.3,0.1

Type RM Length L Ch R = 1 ,114493  ,343.9,343.9,343.9
XS GIS Cut Line= 4
2241947.43351281551895.2857725632241956.22339056 551743.02558908
2241965.49818002551506.0989326192241969.70032995551345.750936077
#Sta/Elev= 30
       0 2677.68      10  2671.1    42.2 2648.49    86.3 2620.24    94.3 2616.13
   118.3 2601.12  190.832560.906   194.4  2559.3   198.4 2558.94   234.4 2558.41
   254.4 2558.81  261.262560.907   270.5 2563.02   278.5 2566.11   298.5 2567.88
   338.5 2568.21   342.5 2569.09   350.5 2573.06   354.5 2573.97   386.5 2574.19
   398.5 2581.83   406.5  2585.5   422.6 2586.35   426.6 2587.99   434.6  2594.2
   450.6 2599.38   474.6 2608.62   498.4 2619.12   534.6 2633.22     550 2640.87
#Mann= 5 ,-1,0
       0      .1       0  190.83    .045       0  261.26      .1       0
  312.51     .06       0  409.62      .1       0
Bank Sta=190.83,261.26
XS Rating Curve= 0 ,0
Exp/Cntr=0.3,0.1

Type RM Length L Ch R = 1 ,114149  ,467.2,467.2,467.2
XS GIS Cut Line= 4
2242269.95018437551935.5532812382242306.62661352551765.276772626
2242295.08922005551548.7765887952242285.63542396551374.268954958
#Sta/Elev= 30
       0 2671.53    31.1 2652.09      72 2624.24   125.1 2590.47   137.5 2581.65
   149.7 2574.95   166.1 2568.21   178.3 2566.21   190.3 2562.81   198.3 2562.09
   220.3 2562.82   226.4 2561.79  241.582556.464   250.4 2555.47   294.4 2555.12
  308.932556.463   330.5 2558.71   346.5 2565.83   354.5 2567.89   386.6 2567.21
   390.6 2569.39   406.6 2583.17   434.7 2596.06   442.8 2601.11   446.7 2602.66
   462.7 2604.38   470.7 2610.17   478.7 2614.37   510.8 2626.77   565.8 2650.41
#Mann= 5 ,-1,0
       0      .1       0  241.58    .045       0  308.93      .1       0
  354.18     .06       0  450.99      .1       0
Bank Sta=241.58,308.93
XS Rating Curve= 0 ,0
Exp/Cntr=0.3,0.1

Type RM Length L Ch R = 1 ,113682  ,284.9,284.9,284.9
XS GIS Cut Line= 4
     2242609.702      552110.9672242718.03442633551872.715543032
 2242781.4176122551584.2578850342242837.76539141551428.899491125
#Sta/Elev= 30
       0 2669.15    25.3 2662.18    63.5  2649.6   172.4 2609.59   186.5 2602.67
   204.1 2592.09   217.3 2588.75   243.6 2572.61   252.4 2563.75   257.2 2560.93
   286.6 2557.74   351.3 2559.89   424.3 2558.49   437.4 2551.94  453.052549.633
   470.1 2547.31   498.2  2547.8  502.65 2549.63   511.1 2557.86   523.4  2565.5
   558.5 2568.09   573.1 2579.46   581.6  2587.9   585.9 2590.62   641.2 2613.97
   658.2 2623.46     671 2624.23   675.2 2626.08   692.2 2640.63   722.3 2658.43
#Mann= 5 ,-1,0
       0      .1       0  361.72     .05       0  453.05    .045       0
  502.65     .06       0  667.06      .1       0
Bank Sta=453.05,502.65
XS Rating Curve= 0 ,0
Exp/Cntr=0.3,0.1

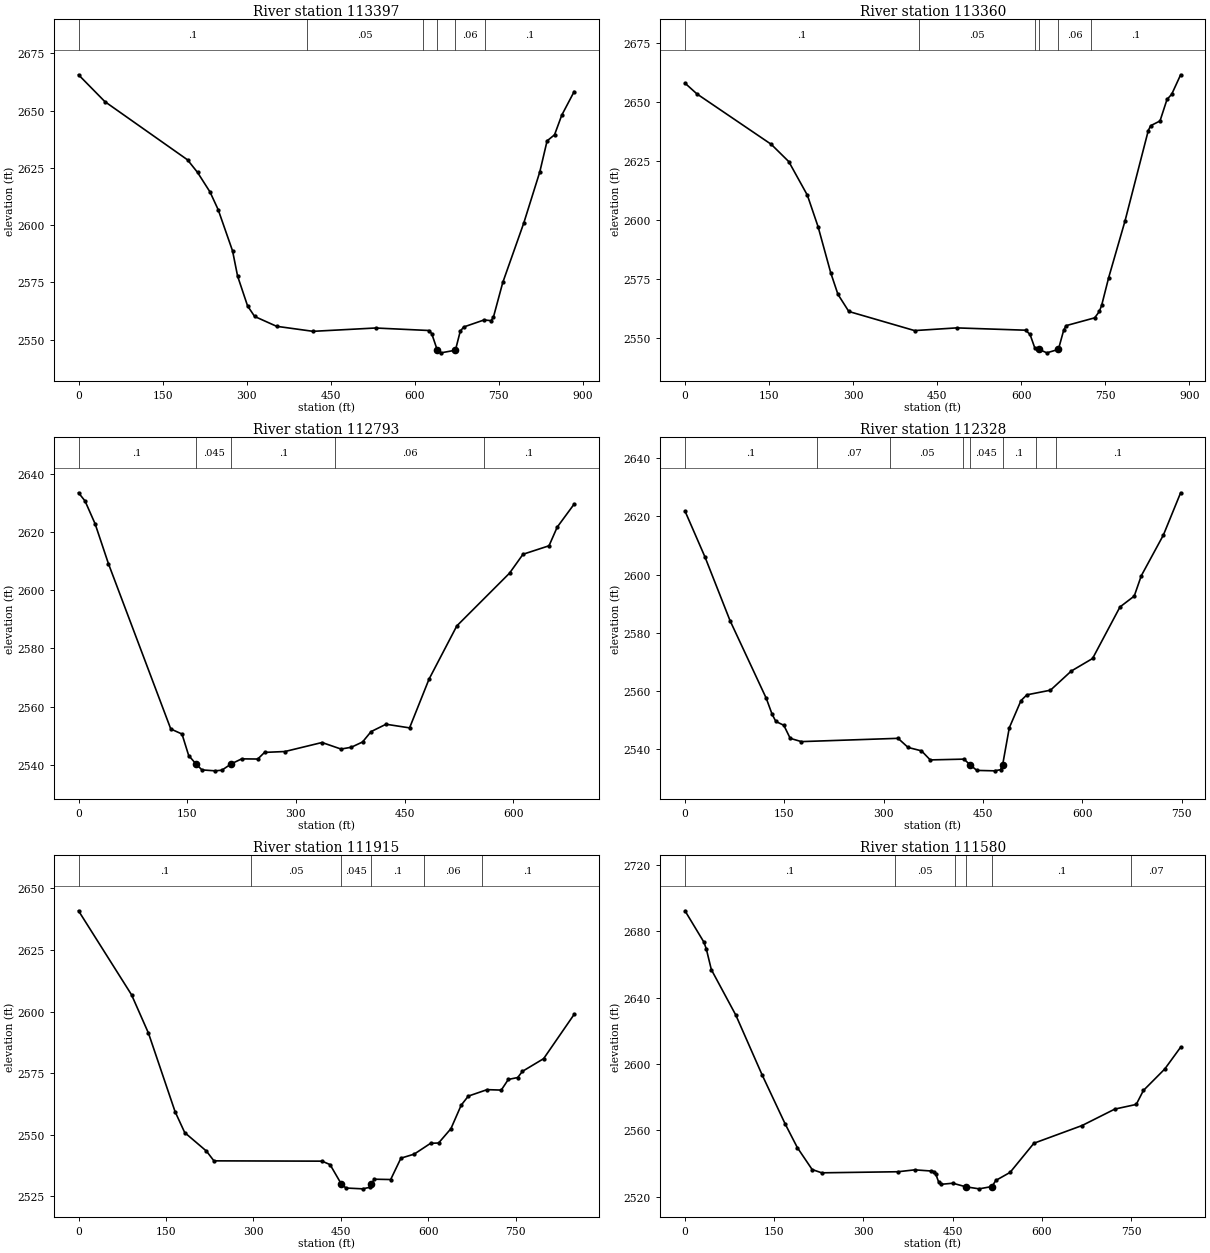
Type RM Length L Ch R = 1 ,113397  ,36.9,36.9,36.9
BEGIN DESCRIPTION:
structure
END DESCRIPTION:
XS GIS Cut Line= 6
2242693.99271278552185.1151673082243016.83703099552016.410050797
2242991.17908853551914.2717029262242990.27211367551851.456469905
2243058.15656813551685.6285801012243105.18528801551522.851509732
#Sta/Elev= 30
       0 2665.64    47.1 2653.91   194.5 2628.52   212.4 2623.03   234.7 2614.47
   249.2 2606.78   274.9 2588.76   283.9 2577.75   301.7 2564.75   314.3 2560.15
   353.5 2555.85   418.5 2553.66     530 2555.11   625.4 2554.02   630.3 2552.66
  640.292545.432   646.9 2544.27   672.6 2545.42   681.2 2553.68   687.3 2555.55
   723.8 2558.63   736.3 2558.31   740.5 2559.93   757.1 2574.99   794.6 2600.95
   823.2 2623.28   836.2  2636.8   849.5 2639.45   862.4 2648.03   884.5 2658.31
#Mann= 6 ,-1,0
       0      .1       0  407.06     .05       0   614.3     .06       0
  640.29    .045       0   672.6     .06       0  725.02      .1       0
Bank Sta=640.29,672.6
XS Rating Curve= 0 ,0
Exp/Cntr=0.3,0.1

Type RM Length L Ch R = 1 ,113360  ,566.8,566.8,566.8
BEGIN DESCRIPTION:
structure
END DESCRIPTION:
XS GIS Cut Line= 6
2242730.35312853552192.0992821312243053.19744674 552023.39416562
2243027.53950428551921.2558177492243026.63252942551858.440584728
2243094.51698388551692.6126949242243141.54570376551529.835624555
#Sta/Elev= 30
       0 2658.01    21.4 2653.43   153.9 2632.09   185.2 2624.77   218.4 2610.53
   237.5 2597.19   260.1 2577.65     273  2568.5   292.4 2561.26   409.7 2553.17
   484.7 2554.31   607.8 2553.33   615.8 2551.52   624.3 2545.78  631.622545.208
   645.8 2543.74   666.4 2545.21   675.8 2553.32   680.1 2555.26   731.1 2558.57
   739.4 2561.26   743.6  2563.9   756.1 2575.62   785.2 2599.57   826.8 2637.94
     831 2639.97   847.7 2641.99   860.2 2651.12   868.5 2653.27   884.5 2661.55
#Mann= 6 ,-1,0
       0      .1       0  417.06     .05       0   624.3     .06       0
  631.62    .045       0   666.4     .06       0  725.02      .1       0
Bank Sta=631.62,666.4
XS Rating Curve= 0 ,0
Exp/Cntr=0.3,0.1

Type RM Length L Ch R = 1 ,112793  ,464.9,464.9,464.9
XS GIS Cut Line= 4
2243052.34680455552351.2003520882243168.92017698552284.144872374
2243409.28828118552150.0339129462243650.68800815552020.049444577
#Sta/Elev= 30
       0 2633.52       9  2630.7    22.9 2622.85    41.3 2609.14   127.3 2552.32
   142.8 2550.58     152  2543.2  161.882540.361   170.3 2538.25   188.6 2537.93
   197.8 2538.15  210.952540.362   225.2 2542.05   247.3 2541.99   256.7 2544.27
   284.8 2544.57     336 2547.67   362.2 2545.42   376.4 2546.04   391.9 2547.85
   403.7 2551.42   424.3 2553.95   456.8  2552.7   483.6 2569.43     522 2587.76
   594.7 2605.88   613.3 2612.38   649.2  2615.3   660.5 2621.71   683.9 2629.64
#Mann= 5 ,-1,0
       0      .1       0  161.88    .045       0  210.95      .1       0
  354.48     .06       0  559.73      .1       0
Bank Sta=161.88,210.95
XS Rating Curve= 0 ,0
Exp/Cntr(USF)=0,0
Exp/Cntr=0.3,0.1

Type RM Length L Ch R = 1 ,112328  ,413.2,413.2,413.2
XS GIS Cut Line= 4
  2243176.672754552707.9211272952243312.81264401552644.997710646
2243690.09311569552466.9791506172243847.80167764 552377.22021996
#Sta/Elev= 30
       0 2621.88    30.3 2606.01      68 2584.18   122.8  2557.4   131.6 2551.91
   137.3 2549.44   149.3 2548.13   158.9 2543.64   175.8 2542.51   321.8 2543.64
     337  2540.5   357.2 2539.33   370.4 2536.21   421.4 2536.48  430.282534.572
   440.8  2532.6   467.7 2532.45   476.6 2532.85  479.812534.571   489.8 2547.25
   507.5 2556.63   516.4 2558.61     552 2560.21   583.4 2566.79   615.6 2571.12
     657 2588.86   678.5 2592.59   689.2 2599.61   722.5 2613.59   748.6 2628.16
#Mann= 8 ,-1,0
       0      .1       0  199.98     .07       0  309.98     .05       0
  419.98      .1       0  430.28    .045       0  479.81      .1       0
  529.98     .06       0  559.98      .1       0
Bank Sta=430.28,479.81
XS Rating Curve= 0 ,0
Exp/Cntr=0.3,0.1

Type RM Length L Ch R = 1 ,111915  ,334.8,334.8,334.8
XS GIS Cut Line= 4
2243168.45909156552988.2712619292243376.90383578552930.617548347
2243712.83164993552918.5681144332244008.12745829552960.204676655
#Sta/Elev= 30
       0 2640.94      91 2606.81   120.1 2591.19   165.7 2559.34   182.3 2550.81
   219.5 2543.31   232.4 2539.34   417.9 2539.22   431.7 2537.81  450.952529.959
     459  2528.3   487.7 2527.97   499.7 2528.59  502.44 2529.96   507.7 2531.88
   535.7 2531.75   553.3 2540.43     576 2542.07   604.3 2546.48   617.9 2546.59
   639.1 2552.41   656.7 2561.95   668.9 2565.64   701.2 2568.27   725.5 2568.09
   737.6 2572.42   753.7 2573.19   761.8  2575.7   798.2 2580.86   850.6 2598.86
#Mann= 6 ,-1,0
       0      .1       0  296.27     .05       0  450.95    .045       0
  502.44      .1       0  592.41     .06       0  692.41      .1       0
Bank Sta=450.95,502.44
XS Rating Curve= 0 ,0
Exp/Cntr=0.3,0.1

Type RM Length L Ch R = 1 ,111580  ,393.3,393.3,393.3
XS GIS Cut Line= 4
2243209.56943082553312.8258909162243416.13598091553257.934091261
2243791.78355234553235.6342682382244034.78085517553237.585263342
#Sta/Elev= 30
       0 2692.36    31.7 2673.51    35.8 2669.42    44.3 2656.88    85.5 2629.41
   129.4 2593.59   168.2 2563.95   188.9 2549.52   213.7 2536.34   229.8 2534.35
     358    2535   386.1 2536.14   414.1 2535.43   418.1 2535.13   421.7 2533.36
   426.1 2529.02   430.2 2527.41   450.2 2528.08   471.7 2525.94   494.3 2524.69
  515.992526.083   522.3 2529.74   546.4 2534.61   586.4 2552.18   667.4 2562.87
   722.4 2572.78   758.4 2575.59   770.4 2583.99   806.3 2596.94     833  2610.1
#Mann= 6 ,-1,0
       0      .1       0  353.74     .05       0  453.74      .1       0
   471.7    .045       0  515.99      .1       0  750.04     .07       0
Bank Sta=471.7,515.99
XS Rating Curve= 0 ,0
Exp/Cntr=0.3,0.1

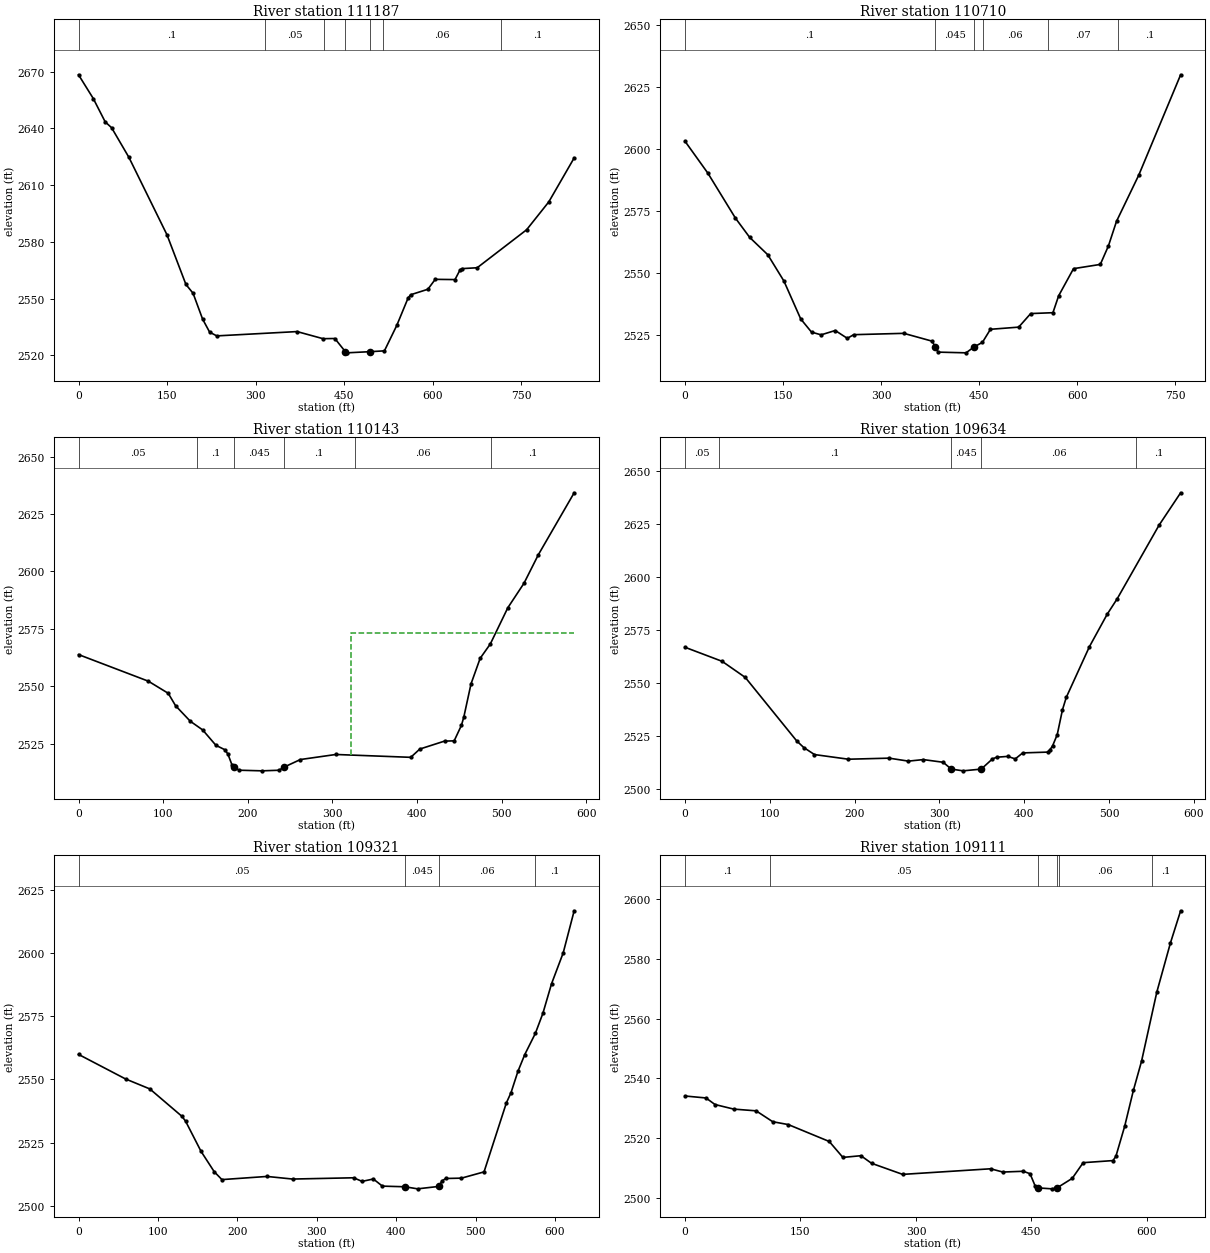
Type RM Length L Ch R = 1 ,111187  ,477.3,477.3,477.3
XS GIS Cut Line= 4
2243243.29081337553656.4990046282243467.75241319553631.505357802
2243797.45149132553628.1438478662244069.20753577553711.324233212
#Sta/Elev= 30
       0 2668.39      25 2655.84    45.2  2643.5    56.1 2640.38    85.4 2624.73
   149.8 2583.85     182 2557.53   194.1 2552.88   210.2 2539.25   222.2  2532.3
   234.3 2530.34   370.3 2532.62   414.3 2528.86   434.3 2528.96  451.962522.057
   454.3 2521.38   494.3    2522   518.3 2522.43   539.2 2535.84   558.4 2550.36
   562.6 2552.07   591.9 2554.99   604.4 2560.24   637.9 2560.11   646.3 2565.14
   650.4 2565.91   675.5 2566.37   759.2 2586.44   796.9 2601.23   839.8 2624.44
#Mann= 7 ,-1,0
       0      .1       0  315.85     .05       0  415.85      .1       0
  451.96    .045       0   494.3      .1       0  515.85     .06       0
  715.57      .1       0
Bank Sta=451.96,494.3
XS Rating Curve= 0 ,0
Exp/Cntr=0.3,0.1

Type RM Length L Ch R = 1 ,110710  ,567.2,567.2,567.2
XS GIS Cut Line= 4
2243230.63859253553958.8410079122243408.41426169 554011.04205889
2243760.00601612554149.5399387042243944.79157265 554212.68674945
#Sta/Elev= 30
       0 2603.08      35 2590.23    77.2 2572.12    99.1 2564.33   126.7 2557.37
   151.4 2546.78   177.1 2531.53   193.6 2526.22   208.3 2525.13   229.9 2526.87
   248.4 2523.72   258.1 2525.19   334.8 2525.73     378 2522.59  383.132520.272
   387.2 2518.17   430.1 2517.88  442.372520.272   455.1 2522.09   467.4 2527.36
   510.6 2528.23     529 2533.69     563 2534.04   571.8 2540.88   594.5 2551.77
   635.5 2553.48   647.9 2560.92   660.3 2570.84   694.4 2589.47   758.4 2629.83
#Mann= 6 ,-1,0
       0      .1       0  383.13    .045       0  442.37      .1       0
  455.28     .06       0  555.28     .07       0  663.17      .1       0
Bank Sta=383.13,442.37
XS Rating Curve= 0 ,0
Exp/Cntr=0.3,0.1

Type RM Length L Ch R = 1 ,110143  ,508.3,508.3,508.3
XS GIS Cut Line= 4
2243145.96361392554457.5303633712243296.03998853554550.180788761
2243511.16936064554715.0529434112243617.80261929554803.032953358
#Sta/Elev= 30
       0 2563.82    82.5 2552.24     106 2546.97   114.7 2541.56   132.1  2534.8
   146.7 2531.03   162.4 2524.32   172.8 2522.43   176.5 2520.55   181.6 2515.56
  183.572514.772     190 2513.49   216.9 2513.22     237 2513.48  242.472514.771
   262.2 2518.14   304.1 2520.34   392.6  2519.1   403.3  2522.7   432.5 2526.16
   443.9 2526.27   452.5 2533.04   455.3 2536.63   463.8 2551.05   474.6 2562.18
   486.6 2568.42   507.3 2584.19   526.4 2594.85   543.4 2607.29   585.7 2634.23
#Mann= 6 ,-1,0
       0     .05       0     140      .1       0  183.57    .045       0
  242.47      .1       0  326.37     .06       0  487.41      .1       0
#XS Ineff= 2 , 0
                          321.44         2573.14
Permanent Ineff=
       F       F
Bank Sta=183.57,242.47
XS Rating Curve= 0 ,0
Exp/Cntr=0.3,0.1

Type RM Length L Ch R = 1 ,109634  ,313.7,313.7,313.7
XS GIS Cut Line= 3
2242917.04504867554707.3188520912242988.63654993554938.769420328
2243238.75109958555172.275413406
#Sta/Elev= 30
       0 2566.77    43.8 2560.14    71.1 2552.55   131.7 2522.64   140.1 2519.49
   152.7 2516.19   192.7    2514   240.7  2514.5   263.4  2513.1     281 2513.82
   304.4 2512.56  313.98 2509.34   327.9 2508.52  349.282509.338   362.5 2514.13
   367.5 2514.94   380.6 2515.33   389.4 2514.14   398.2 2516.97   427.6 2517.35
   430.4 2518.52   433.4 2520.27   438.9 2525.58   445.1 2537.34   449.6 2543.18
   476.9 2567.08   497.8 2582.33   509.6 2589.62     559 2624.34   584.4 2639.59
#Mann= 5 ,-1,0
       0     .05       0      40      .1       0  313.98    .045       0
  349.28     .06       0  532.27      .1       0
Bank Sta=313.98,349.28
XS Rating Curve= 0 ,0
Exp/Cntr=0.3,0.1

Type RM Length L Ch R = 1 ,109321  ,209.7,209.7,209.7
XS GIS Cut Line= 4
2242592.01230181554865.3770146112242670.24155698555016.735991499
2242885.08830557555285.5466505112242953.29218379555371.529765933
#Sta/Elev= 30
       0 2559.87    59.3 2550.15    89.8 2546.22   130.4 2535.34   134.9 2533.43
   154.3 2521.54   170.9 2513.49   180.6 2510.37   237.4 2511.62   269.6 2510.59
   346.5 2511.09   357.1 2509.67   371.3 2510.61   382.7 2507.79   411.1 2507.54
     427 2506.72   453.8 2507.68   457.7 2509.83   462.4 2510.81   482.3 2510.95
   510.7 2513.42   538.8 2540.68   544.7 2544.76   553.4 2553.18     562 2559.81
   575.3 2568.16   584.8 2576.09   595.7 2587.78   610.4 2600.01   624.2 2616.64
#Mann= 4 ,-1,0
       0     .05       0   411.1    .045       0   453.8     .06       0
   574.5      .1       0
Bank Sta=411.1,453.8
XS Rating Curve= 0 ,0
Exp/Cntr(USF)=0,0
Exp/Cntr=0.3,0.1

Type RM Length L Ch R = 1 ,109111  ,63.7,63.7,63.7
BEGIN DESCRIPTION:
structure
END DESCRIPTION:
XS GIS Cut Line= 6
2242307.43427698555039.2521465532242407.36437192 555167.62887008
2242451.90162608555215.6604770532242492.18647803555238.501237334
2242609.98429672555268.4548623182242772.43795332555455.557399465
#Sta/Elev= 30
       0 2534.13    27.3 2533.47      39 2531.28    63.3 2529.75    92.4 2529.17
     114 2525.53   134.2 2524.58   187.4 2518.93   205.1 2513.61   228.5 2514.18
   242.3 2511.65   282.7 2507.94     397 2509.81   412.9 2508.72   439.4 2508.98
   448.2 2508.16   454.8  2504.1  458.722503.425   476.5 2503.11   483.2 2503.42
     503 2506.61   517.2 2511.85   555.9 2512.55   559.7 2513.96   571.1    2524
   582.4 2535.97     593 2545.72   612.9 2568.88   630.6  2585.3   643.8 2596.01
#Mann= 6 ,-1,0
       0      .1       0     110     .05       0  458.72    .045       0
   483.2     .05       0  486.04     .06       0  606.04      .1       0
Bank Sta=458.72,483.2
XS Rating Curve= 0 ,0
Exp/Cntr=0.3,0.1

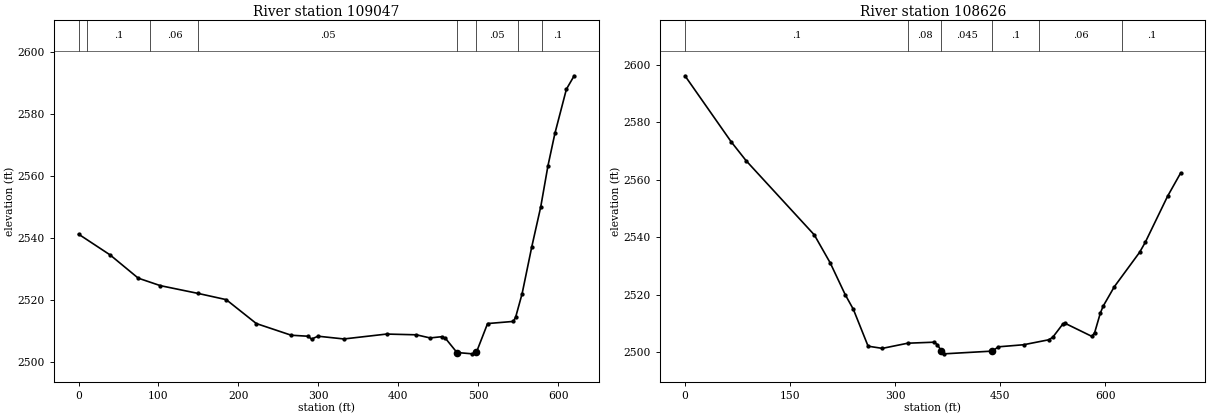
Type RM Length L Ch R = 1 ,109047  ,421,421,421
BEGIN DESCRIPTION:
structure
END DESCRIPTION:
XS GIS Cut Line= 6
 2242272.5976089555069.0585074562242374.22876929555184.677240097
2242420.35065055555257.3501537452242449.15228542555279.282730588
2242569.61916592555303.3644195752242691.23791799555487.550177827
#Sta/Elev= 30
       0 2541.22    39.5 2534.51    74.7 2527.01   102.4 2524.59     150 2522.06
   184.7 2520.08   222.4 2512.36   266.1 2508.59   287.2 2508.27   291.4 2507.34
   299.5 2508.28   331.9 2507.39   385.3 2508.97   422.6 2508.73   439.7 2507.72
   454.3 2508.12   458.9  2507.6   473.3 2503.02   492.5 2502.59   497.6 2503.06
   511.6 2512.36   543.8 2513.05   546.7 2514.41   554.8 2522.01   566.9 2537.15
   578.1 2550.03   587.1 2563.24   595.8 2573.71   610.2 2587.99   619.9 2592.31
#Mann= 8 ,-1,0
       0     .05       0      10      .1       0      90     .06       0
     150     .05       0   473.3    .045       0   497.6     .05       0
   549.2     .06       0   579.2      .1       0
Bank Sta=473.3,497.6
XS Rating Curve= 0 ,0
Exp/Cntr=0.3,0.1

Type RM Length L Ch R = 1 ,108626  ,431.2,431.2,431.2
XS GIS Cut Line= 5
2241913.01143272555296.6585943852242146.55557265555405.966766787
2242271.07422994555607.9505582882242309.81817189555652.888614677
2242462.77574705555648.441185539
#Sta/Elev= 30
       0  2596.2    65.9 2573.26    87.4 2566.63   184.6 2540.87   207.3 2531.14
   228.7 2520.09   240.4 2514.95   261.4 2502.16   281.7  2501.4     318  2503.2
   355.6 2503.55   360.2 2502.72  366.142500.449   369.7  2499.5   438.7 2500.45
   447.4 2501.94   483.3 2502.66   519.5  2504.4   525.2 2505.34   539.3 2509.85
   542.2 2510.16   580.8 2505.57   584.8  2506.9   592.8  2513.6   596.8 2516.03
   612.9 2522.86   648.9  2534.8   656.9 2538.23   688.9 2554.32   707.5 2562.38
#Mann= 6 ,-1,0
       0      .1       0  317.86     .08       0  366.14    .045       0
   438.7      .1       0  505.14     .06       0  624.47      .1       0
Bank Sta=366.14,438.7
XS Rating Curve= 0 ,0
Exp/Cntr=0.3,0.1