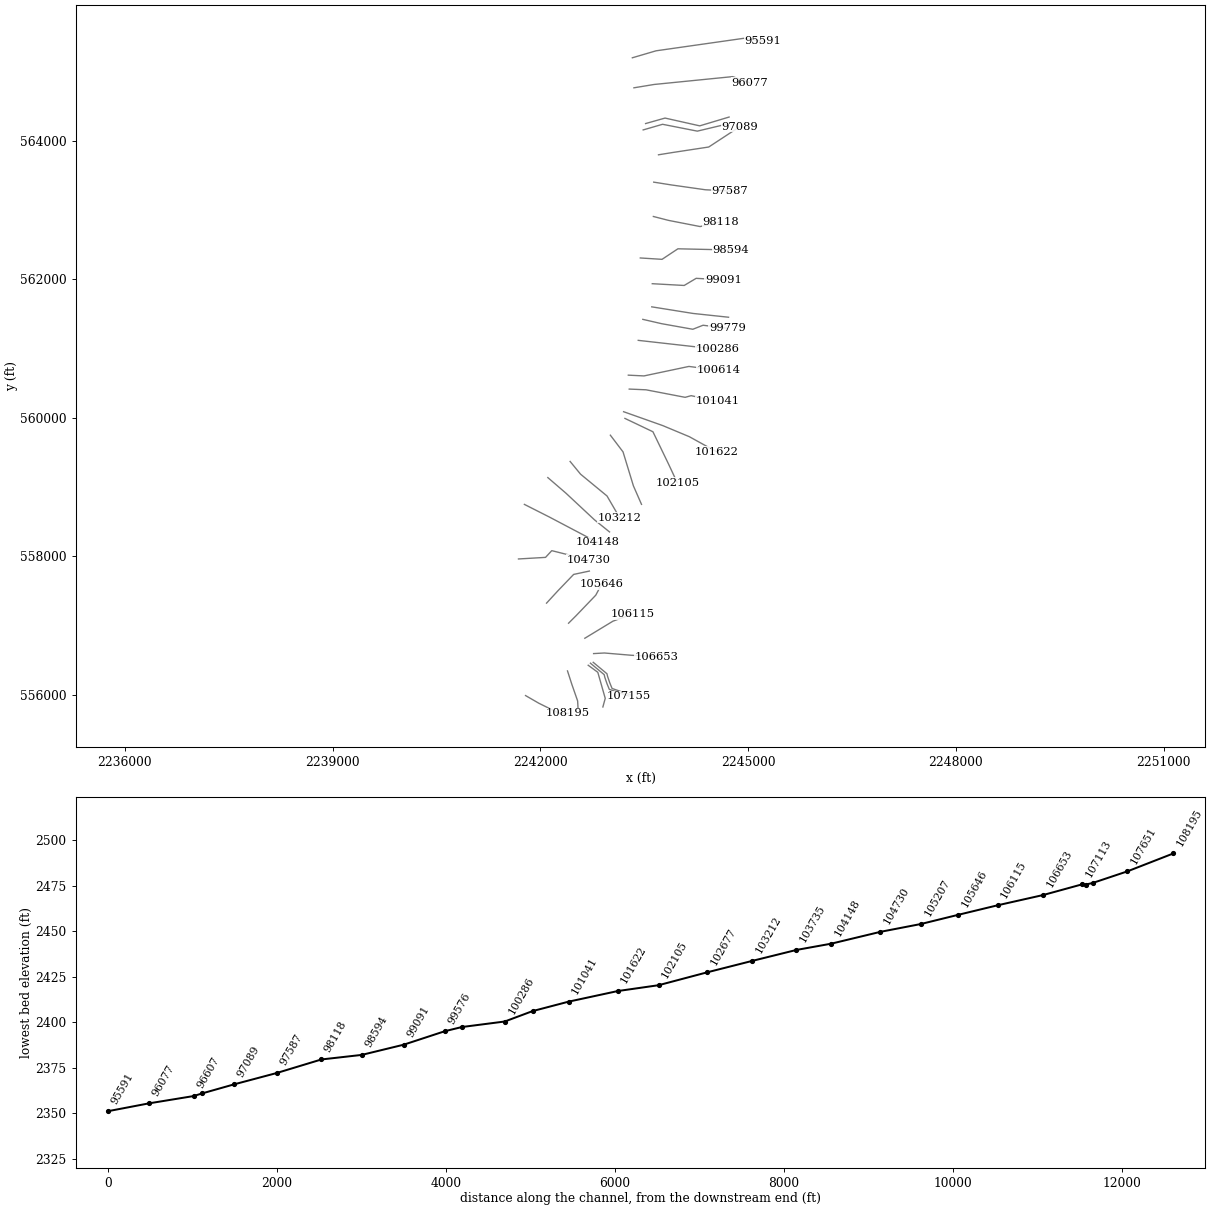
HEC-RAS study TYGVRV2.prj: TYGVRV2

--- TYGVRV2.g01 (geometry) --- (continued)

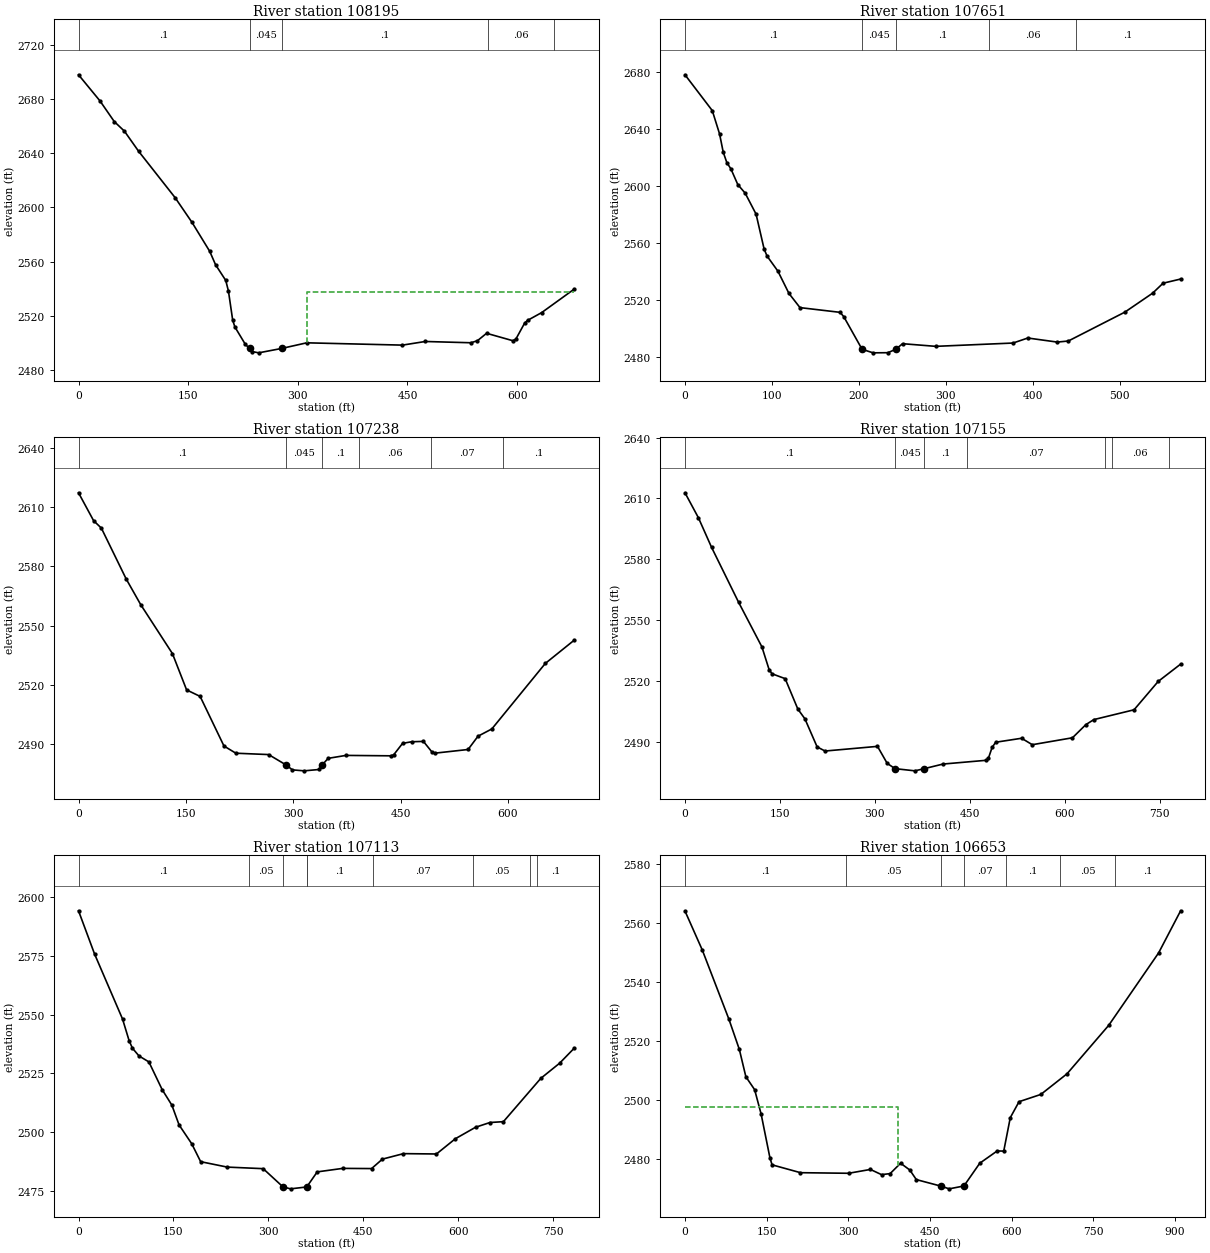
Type RM Length L Ch R = 1 ,108195  ,543.5,543.5,543.5
XS GIS Cut Line= 4
2241785.82193932555986.9857182392241976.63658076555876.706218055
2242272.54598523555730.1407401592242399.96787585555729.607970198
#Sta/Elev= 30
       0 2697.81    29.4 2678.52    48.9 2663.31    62.8 2656.24    82.1 2641.49
   132.1 2607.23   155.2 2589.01   179.5 2567.61   187.5 2557.71   201.4 2546.18
   205.1  2538.3   210.9 2516.88   213.9 2511.86   228.3 2498.95  234.022495.999
   237.7 2493.72   246.4 2492.78   277.72495.998   312.2 2500.17   443.1 2498.47
   474.3 2501.15   536.8 2500.21   545.7 2501.73   558.2 2507.19   594.2 2501.71
   598.2 2502.86   610.2 2514.66   614.2  2516.7   633.6 2522.47     678 2539.75
#Mann= 5 ,-1,0
       0      .1       0  234.02    .045       0   277.7      .1       0
  560.61     .06       0  650.61      .1       0
#XS Ineff= 2 , 0
                          312.34         2537.71
Permanent Ineff=
       F       F
Bank Sta=234.02,277.7
XS Rating Curve= 0 ,0
Exp/Cntr=0.3,0.1

Type RM Length L Ch R = 1 ,107651  ,413.4,413.4,413.4
XS GIS Cut Line= 4
2242391.52108979556343.0448886732242452.82820507556153.034430881
2242537.91385464555908.8838845582242543.86372331 555797.01156508
#Sta/Elev= 30
       0 2677.82    31.4 2652.72    39.8 2636.35      44 2623.57    48.2 2616.18
    52.8 2611.91    60.8 2600.82    69.2  2594.9    81.8 2580.14      91 2555.77
    94.4 2550.78   106.9 2540.19   119.6 2524.57   132.3 2514.63   178.5 2511.31
   182.7 2508.26  203.732485.426   216.4 2482.93   233.4 2483.03  242.56 2485.43
   250.3 2489.34   288.5 2487.48   377.4  2489.8   394.4 2493.32   428.2 2490.47
     441 2491.22     506 2511.45     538 2524.76     550 2531.73   570.2 2534.66
#Mann= 5 ,-1,0
       0      .1       0  203.73    .045       0  242.56      .1       0
  349.66     .06       0  449.66      .1       0
Bank Sta=203.73,242.56
XS Rating Curve= 0 ,0
Exp/Cntr=0.3,0.1

Type RM Length L Ch R = 1 ,107238  ,82.9,82.9,82.9
XS GIS Cut Line= 4
2242690.48807713556425.0147118652242829.15425468556323.062464059
2242936.32428384555946.5093183592242902.31401413 555822.34734955
#Sta/Elev= 30
       0  2617.2    21.1 2603.07    31.9 2599.33    66.6 2573.58    86.9 2560.59
   131.2 2535.83     151 2517.45   169.9 2514.16   203.2 2489.06   219.8 2485.42
   265.6 2484.73  290.132479.444   298.8 2476.98   315.3  2476.5   336.3 2477.19
  340.282479.444   348.7 2482.82   373.6 2484.31   436.1  2484.1   440.2 2484.58
   452.7  2490.4   465.2 2491.21   481.8  2491.4   494.3 2485.78   498.5 2485.47
   544.2  2487.3   558.1 2494.03   577.4  2497.7   652.1 2530.85   692.4  2542.6
#Mann= 6 ,-1,0
       0      .1       0  290.13    .045       0  340.28      .1       0
  392.11     .06       0  492.11     .07       0  593.62      .1       0
Bank Sta=290.13,340.28
XS Rating Curve= 0 ,0
Exp/Cntr=0.3,0.1

Type RM Length L Ch R = 1 ,107155  ,42.2,42.2,42.2
BEGIN DESCRIPTION:
structure
END DESCRIPTION:
XS GIS Cut Line= 6
2242722.49466559556454.709318034 2242921.3709022556289.257659004
2242929.76297802556251.6625297552242961.43945019556159.069764938
2242995.01009844556076.7569986232243277.75316454555979.079360319
#Sta/Elev= 30
       0  2612.8    21.2  2600.5      42  2585.9    84.6 2558.87   121.6 2536.76
   132.9 2525.61   137.5 2523.53   158.3 2521.12   178.4 2506.08   189.5 2501.31
   208.8 2487.46   221.3 2485.42   304.2 2487.72   319.5 2479.35   331.9 2476.73
   363.3 2475.65   378.32476.746   407.8    2479     476 2480.85   479.4 2481.81
   485.3 2487.21     491 2489.76   531.9 2491.72   548.8 2488.54   612.3 2491.96
   633.5 2498.46   646.1 2500.93   709.6 2505.76   747.7 2519.74   783.2 2528.29
#Mann= 7 ,-1,0
       0      .1       0   331.9    .045       0   378.3      .1       0
  445.02     .07       0   664.1     .05       0   674.1     .06       0
   764.1      .1       0
Bank Sta=331.9,378.3
XS Rating Curve= 0 ,0
Exp/Cntr(USF)=0,0
Exp/Cntr=0.3,0.1

Type RM Length L Ch R = 1 ,107113  ,460,460,460
BEGIN DESCRIPTION:
structure
END DESCRIPTION:
XS GIS Cut Line= 6
 2242762.6558302556467.4806324792242961.53206681556302.028973449
2242969.92414263  556264.4338442 2243001.6006148556171.841079383
2243035.17126305556089.5283130682243317.91432915555991.850674764
#Sta/Elev= 30
       0  2594.3    25.4 2575.85    69.6 2548.13      80 2538.88    85.2 2535.71
    95.6  2532.4   111.2 2529.87   132.1 2518.09   147.5 2511.44   158.9    2503
   178.9 2494.97     193 2487.33     235 2485.02   291.8 2484.35   323.1 2476.58
   335.1 2475.75   360.6 2476.55   377.2 2482.98   417.4 2484.47   463.1 2484.39
   480.2 2488.42   513.5 2490.76   565.6 2490.61   595.4  2497.1   627.4 2502.01
   650.2 2504.03   671.4 2504.39   730.5 2522.86   760.2 2529.31   783.2 2535.69
#Mann= 9 ,-1,0
       0      .1       0   268.7     .05       0   323.1    .045       0
   360.6     .05       0  360.84      .1       0  465.02     .07       0
   624.1     .05       0   714.1     .06       0   724.1      .1       0
Bank Sta=323.1,360.6
XS Rating Curve= 0 ,0
Exp/Cntr(USF)=0,0
Exp/Cntr=0.3,0.1

Type RM Length L Ch R = 1 ,106653  ,538.1,538.1,538.1
XS GIS Cut Line= 4
  2242768.514531556593.6189609242242923.66148775556602.155882281
2243316.20737583556569.125772351     2243676.495      556551.073
#Sta/Elev= 30
       0 2563.99    31.7 2550.82    80.7 2527.33    99.8 2517.12   111.8 2507.85
   127.9 2503.47   139.8 2495.23   155.9 2480.47   159.9 2478.01   212.1 2475.35
   300.4 2475.15   340.5 2476.45   360.9 2474.69   376.7 2475.04   395.9 2478.56
   412.8 2476.26   424.8 2473.01470.11042470.792   485.1 2469.88   512.2 2470.85
   541.3 2478.56   573.3 2482.72   585.3 2482.66   597.3 2493.99   613.4  2499.4
   653.4 2501.86   701.5 2508.85   778.1 2525.28   869.7 2549.81   910.1 2564.07
#Mann= 7 ,-1,0
       0      .1       0  295.38     .05       0470.1104    .045       0
   512.2     .07       0  589.31      .1       0  689.31     .05       0
  789.31      .1       0
#XS Ineff= 2 , 0
          391.34 2497.66
Permanent Ineff=
       F       F
Bank Sta=470.1104,512.2
XS Rating Curve= 0 ,0
Exp/Cntr=0.3,0.1

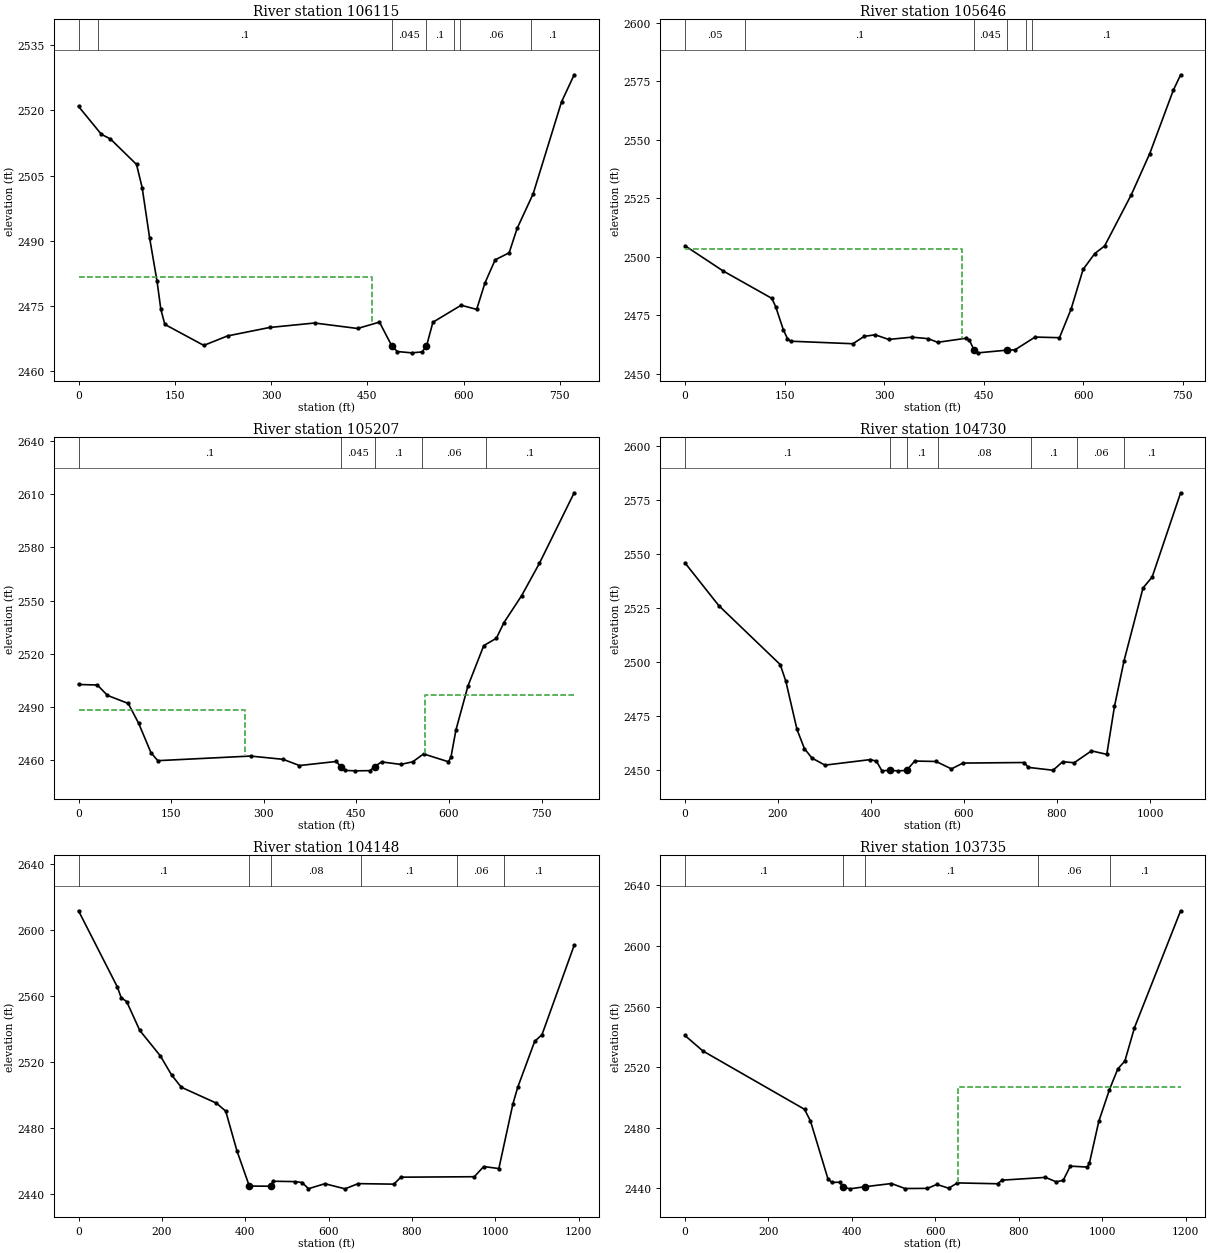
Type RM Length L Ch R = 1 ,106115  ,469.2,469.2,469.2
XS GIS Cut Line= 3
2242641.78572705556815.3342447682243047.37140881557061.841837298
2243326.65974931557164.781807818
#Sta/Elev= 30
       0 2520.93    35.6 2514.51    49.7 2513.44    90.4 2507.58    99.2 2502.23
   110.8 2490.67   122.4 2480.67   128.3 2474.25   134.5 2470.79   195.2 2465.96
   232.2 2468.14   297.7 2470.08   367.9 2471.11   434.8 2469.85   468.9 2471.32
   488.3  2465.8   496.8 2464.55     519 2464.25   535.2 2464.46   542.1 2465.74
   552.2 2471.29   596.2  2475.2   620.4 2474.24   633.2 2480.29   649.2 2485.64
     671 2487.26   683.4 2492.86   708.4 2500.83   752.6 2521.97   772.3  2528.2
#Mann= 7 ,-1,0
       0     .05       0      30      .1       0   488.3    .045       0
   542.1      .1       0  584.62     .08       0  594.62     .06       0
  704.62      .1       0
#XS Ineff= 2 , 0
          458.05 2481.72
Permanent Ineff=
       F       F
Bank Sta=488.3,542.1
XS Rating Curve= 0 ,0
Exp/Cntr=0.3,0.1

Type RM Length L Ch R = 1 ,105646  ,438.6,438.6,438.6
XS GIS Cut Line= 4
     2242406.947      557032.6412242515.36462197557140.969580212
2242799.10466067557436.9906339342242885.68760615 557598.65480703
#Sta/Elev= 30
       0 2504.73    57.4 2493.97   130.9 2482.24   136.6  2478.7   148.3 2468.74
   154.4 2465.03   159.1 2463.94     253 2462.86     270 2466.01   286.5 2466.68
   306.8  2464.7   341.9 2465.67   366.2 2465.03   380.7 2463.47   422.7 2465.17
   428.4 2464.43  435.312460.286   441.7 2458.97     485 2460.12   497.1 2460.25
   527.4 2465.71   564.2 2465.44   581.7 2477.67   599.8 2494.64   617.4 2501.41
   632.2 2504.64   672.4 2526.54   700.2 2544.12   735.6 2571.13   746.7 2577.78
#Mann= 6 ,-1,0
       0     .05       0      90      .1       0  435.31    .045       0
     485      .1       0  513.26     .06       0  523.26      .1       0
#XS Ineff= 2 , 0
          417.04 2503.24
Permanent Ineff=
       F       F
Bank Sta=435.31,485
XS Rating Curve= 0 ,0
Exp/Cntr=0.3,0.1

Type RM Length L Ch R = 1 ,105207  ,477.2,477.2,477.2
XS GIS Cut Line= 4
2242088.90735416557322.7205668142242255.85927041557503.936237113
 2242480.2408985557737.6649414842242707.33204133557786.151264728
#Sta/Elev= 30
       0 2502.67    30.5 2502.38    46.9 2496.51    80.5 2491.97    97.5 2480.69
   117.3 2464.19   128.4 2459.69   278.6 2462.29   331.3 2460.44   357.8 2456.94
   417.2 2459.23  424.542456.383   431.4 2454.19   448.4 2453.95   472.1 2454.07
  479.672456.385   490.8 2458.99   521.9 2457.57   541.4 2459.07   558.7  2463.5
     599 2459.07   603.1 2461.68   611.2 2477.07   630.6  2501.8   656.2 2524.61
   676.7 2528.77   688.9 2537.59   717.6 2552.83   746.2 2570.96   802.6 2610.84
#Mann= 5 ,-1,0
       0      .1       0  424.54    .045       0  479.67      .1       0
   556.4     .06       0   660.4      .1       0
#XS Ineff= 2 , 0
          269.51 2488.24  560.89         2496.75
Permanent Ineff=
       F       F
Bank Sta=424.54,479.67
XS Rating Curve= 0 ,0
Exp/Cntr=0.3,0.1

Type RM Length L Ch R = 1 ,104730  ,582,582,582
XS GIS Cut Line= 4
 2241683.7312116557961.0473008052242074.35912036557983.836200312
2242164.38292804 558081.017020842242690.22128212557948.993631977
#Sta/Elev= 30
       0 2545.88    72.6 2526.13   204.8 2498.83   216.8 2491.18   240.9  2468.8
   256.9 2459.92   273.1 2455.57     301  2452.3   398.6 2454.86   411.6 2454.16
   423.4 2449.74  440.75 2449.83   458.6 2449.66  476.472449.829     494 2454.19
     540 2453.99     573 2450.56   597.8 2453.25   729.8 2453.51     738 2451.27
   791.6 2449.93   812.2 2453.88     837  2453.4   874.1  2458.9   907.1 2457.29
   923.6 2479.45   944.2 2500.59     985 2534.26  1004.7 2539.35  1065.9 2578.31
#Mann= 7 ,-1,0
       0      .1       0  440.75    .045       0  476.47      .1       0
  543.76     .08       0  743.76      .1       0  843.76     .06       0
  943.76      .1       0
Bank Sta=440.75,476.47
XS Rating Curve= 0 ,0
Exp/Cntr=0.3,0.1

Type RM Length L Ch R = 1 ,104148  ,412.7,412.7,412.7
XS GIS Cut Line= 4
     2241769.008      558749.5262242124.79038828558569.444983857
2242630.31149768558302.9410811152242823.86512659558200.354216656
#Sta/Elev= 30
       0 2611.61    93.2 2565.45   102.2 2559.05   115.6 2556.56     147 2539.12
   196.1 2523.79   223.2 2512.19   246.7  2504.7   330.8 2495.06   353.2 2490.24
   380.1 2466.21  409.822444.844   460.7 2444.73   466.6 2447.76   519.4 2447.53
   536.6 2446.97   551.8 2443.22     591 2446.26   639.5 2443.15   670.9 2446.31
   756.8 2445.99   773.4 2450.21   949.7 2450.49   972.3 2456.66  1008.6 2455.43
  1042.3 2494.61  1053.8 2504.62  1094.6 2532.53    1112 2536.48  1189.3 2590.68
#Mann= 6 ,-1,0
       0      .1       0  409.82    .045       0   460.7     .08       0
  678.76      .1       0  908.76     .06       0 1020.23      .1       0
Bank Sta=409.82,460.7
XS Rating Curve= 0 ,0
Exp/Cntr=0.3,0.1

Type RM Length L Ch R = 1 ,103735  ,522.6,522.6,522.6
XS GIS Cut Line= 4
2242107.62775549559136.8119765742242368.89358303 558911.59374653
2242780.48376839558526.9511470672242998.29176899558351.484661461
#Sta/Elev= 30
       0 2540.89      43 2530.66   286.6 2492.17   300.8 2484.42   342.5 2446.45
   351.8 2443.91   371.6 2444.08   377.8 2441.01   395.3 2439.69     431 2441.07
   494.9 2443.19   527.3 2439.91     581 2439.99   603.7  2442.6     632 2440.11
   653.1  2443.6   749.1 2443.04     760 2445.41     864 2447.25   889.5 2444.35
   906.5 2445.25   923.5 2454.67   964.4 2454.06   969.5  2456.8   991.8 2484.19
  1017.4 2505.17  1037.3  2518.8  1054.4 2524.09  1077.4 2546.09    1188  2623.2
#Mann= 5 ,-1,0
       0      .1       0   377.8    .045       0     431      .1       0
  844.94     .06       0 1018.28      .1       0
#XS Ineff= 2 , 0
                          653.58         2507.18
Permanent Ineff=
       F       F
Bank Sta=377.8,431
XS Rating Curve= 0 ,0
Exp/Cntr=0.3,0.1

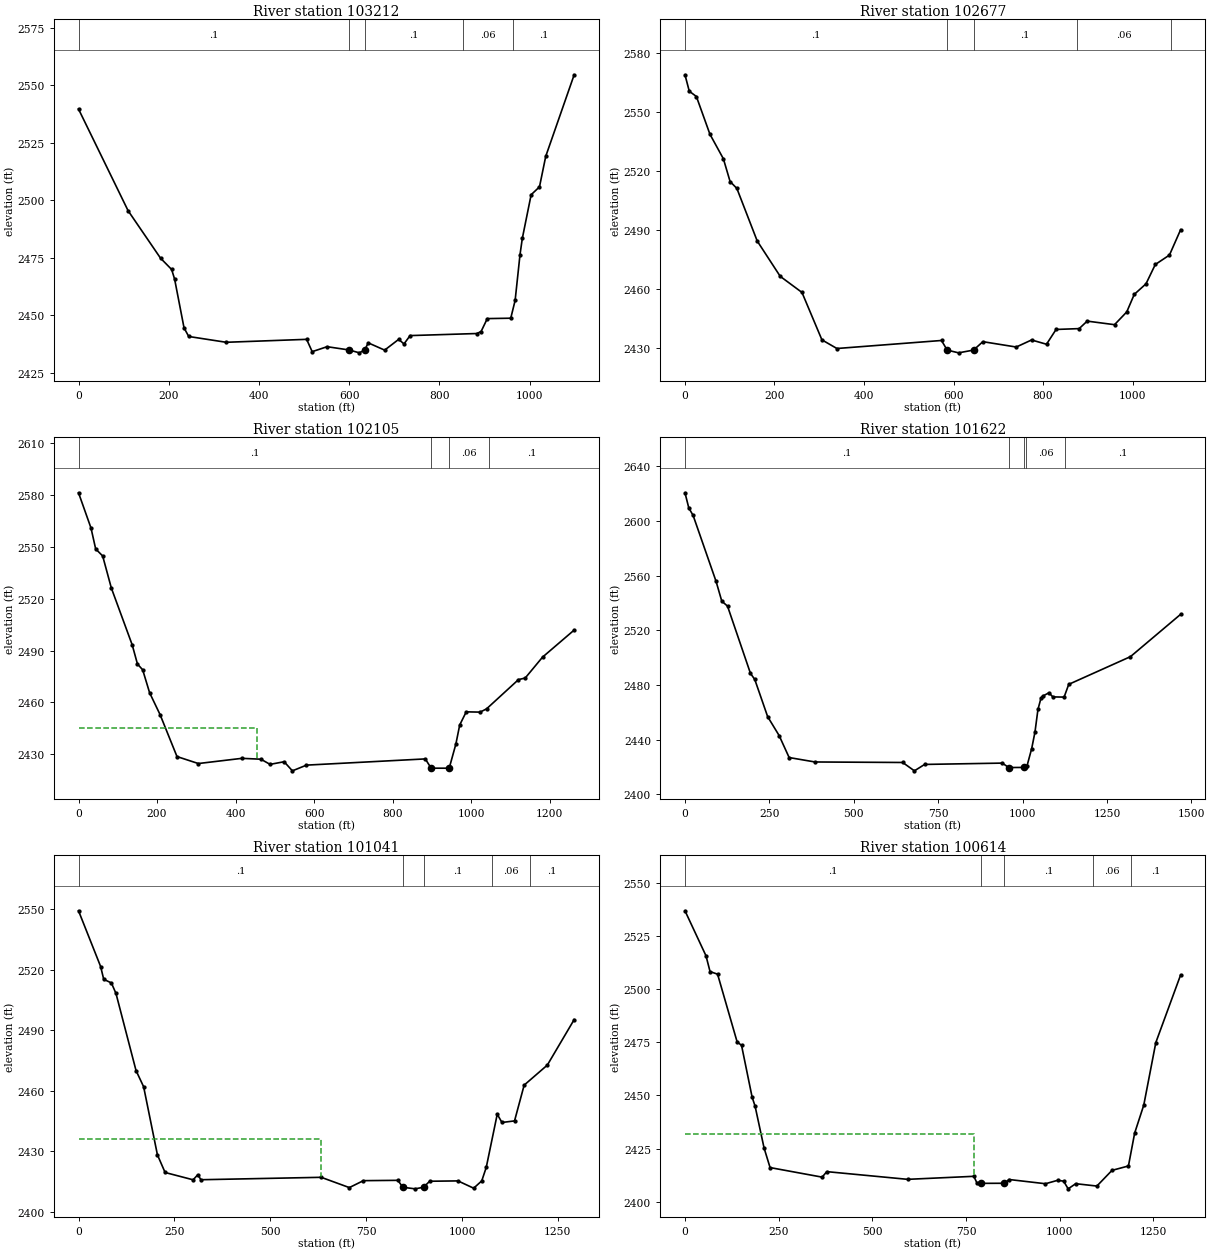
Type RM Length L Ch R = 1 ,103212  ,535.2,535.2,535.2
XS GIS Cut Line= 4
   2242429.20178559370.1319045182242580.27799477559185.935946552
2242961.91190712558871.1579819492243145.96594728558554.733684113
#Sta/Elev= 30
       0 2539.68   109.9 2495.49   181.8 2474.85   206.5 2469.92   213.1 2465.71
     234 2444.51   244.4 2440.78   327.4 2438.26   505.8 2439.54   518.1 2434.18
   551.2 2436.34   599.6 2434.93   622.9 2433.67   634.62434.991   642.5    2438
   678.8 2434.85   709.9 2439.53   721.7 2437.54   735.2 2441.17   883.3 2442.07
   892.6 2442.94   906.4 2448.56   958.4 2448.73   968.1 2456.46   978.9 2476.34
     984  2483.4  1003.6 2502.42  1022.1 2505.85    1036 2519.14    1099 2554.58
#Mann= 5 ,-1,0
       0      .1       0   599.6    .045       0   634.6      .1       0
  852.93     .06       0  962.93      .1       0
Bank Sta=599.6,634.6
XS Rating Curve= 0 ,0
Exp/Cntr=0.3,0.1

Type RM Length L Ch R = 1 ,102677  ,571.8,571.8,571.8
XS GIS Cut Line= 4
2243010.36486373 559749.537158272243193.38920608559508.029586874
2243342.96492477559017.4528261122243459.87829312558750.292142653
#Sta/Elev= 30
       0 2569.08     9.6 2560.71    25.5    2558    55.8 2538.75    85.8 2526.27
   100.8 2514.67   115.9 2511.18   161.4 2484.36   212.8 2466.35   261.4 2458.15
     306 2433.97   339.5 2429.57   573.2 2433.66  585.782428.768   611.3 2427.36
  644.762428.764   665.6 2433.05   740.2 2430.32   774.4 2433.92   807.8 2431.74
   829.2 2439.28   880.8 2439.71   898.7 2443.53   959.8 2441.71   987.1 2448.21
  1003.9 2457.16  1030.1 2462.53  1050.9 2472.39  1082.5 2477.19  1107.5 2490.12
#Mann= 5 ,-1,0
       0      .1       0  585.78    .045       0  644.76      .1       0
   875.9     .06       0  1085.9      .1       0
Bank Sta=585.78,644.76
XS Rating Curve= 0 ,0
Exp/Cntr=0.3,0.1

Type RM Length L Ch R = 1 ,102105  ,483.8,483.8,483.8
XS GIS Cut Line= 4
2243220.71117269559992.0811190272243624.93197317559799.195873222
2243845.49911285559342.5217743072243975.80925834559064.204277859
#Sta/Elev= 30
       0  2581.4    31.8 2560.98    43.7 2548.86    61.5 2544.81    83.6 2526.23
   136.8 2493.25   150.1 2482.19   163.4 2478.85   181.1 2465.52   207.7 2452.89
   250.8 2428.58   305.2 2424.54     416 2427.55   464.5 2427.05   487.8 2424.06
   523.7 2425.58   544.7 2420.31   580.6 2423.62   883.2 2427.22   898.1 2421.84
  944.052421.842   961.1 2435.89   970.8 2446.87   987.4 2454.49  1022.8 2454.33
  1039.3 2456.24  1120.5 2473.17  1137.6 2474.07  1181.8 2486.19  1262.3 2501.87
#Mann= 4 ,-1,0
       0      .1       0   898.1    .045       0  944.05     .06       0
 1045.03      .1       0
#XS Ineff= 2 , 0
          453.76 2445.18
Permanent Ineff=
       F       F
Bank Sta=898.1,944.05
XS Rating Curve= 0 ,0
Exp/Cntr=0.3,0.1

Type RM Length L Ch R = 1 ,101622  ,580.7,580.7,580.7
XS GIS Cut Line= 4
2243201.42494143560088.8754911342243766.65530526559888.227367709
2244150.04877805 559728.009678282244546.22169984 559508.88107252
#Sta/Elev= 30
       0 2620.59    11.3 2609.48    24.1 2604.01    92.1 2555.74     109 2541.29
     126 2537.63   193.9 2488.45   206.7 2483.97   244.9 2456.72   278.8 2442.94
   308.5 2426.82   384.9 2423.58   644.8 2423.21   679.5 2417.09   709.8 2421.78
   939.7 2422.75  959.022419.505 1003.192419.584  1013.3 2420.98  1026.9 2433.42
  1036.6 2445.47  1045.4 2461.99  1054.2 2470.11  1058.9  2471.7  1077.8 2474.19
  1089.6  2471.2  1122.9 2471.06  1136.6 2480.39  1319.4 2500.66    1468 2531.64
#Mann= 5 ,-1,0
       0      .1       0  959.02    .045       0 1003.19      .1       0
 1009.79     .06       0 1125.31      .1       0
Bank Sta=959.02,1003.19
XS Rating Curve= 0 ,0
Exp/Cntr=0.3,0.1

Type RM Length L Ch R = 1 ,101041  ,426.7,426.7,426.7
XS GIS Cut Line= 5
2243282.55272312560415.897198886  2243524.581673560405.510086726
2244090.32962021560296.6370524452244176.77143261560320.789042488
2244551.96746241  560237.5020316
#Sta/Elev= 30
       0 2549.24    57.7 2521.57    65.7 2515.24    85.7 2513.44    97.7 2508.21
     150 2469.95   169.8 2461.92   205.8 2428.11   225.8 2419.37   298.9 2415.74
   311.1 2418.27   319.2 2415.78   632.9 2416.98   706.2 2411.88   742.9 2415.32
   832.8 2415.48  845.722412.035   877.9 2411.26 899.6622412.061   915.7 2415.03
   989.5  2415.2  1030.4 2411.58  1051.5  2415.2  1063.2 2421.87  1091.9 2448.29
  1104.2 2444.19    1137 2444.97  1162.1 2462.73  1222.5 2472.66  1292.5 2495.24
#Mann= 5 ,-1,0
       0      .1       0  845.72    .045       0 899.662      .1       0
 1078.13     .06       0 1178.13      .1       0
#XS Ineff= 2 , 0
          633.58 2436.18
Permanent Ineff=
       F       F
Bank Sta=845.72,899.662
XS Rating Curve= 0 ,0
Exp/Cntr=0.3,0.1

Type RM Length L Ch R = 1 ,100614  ,328.2,328.2,328.2
XS GIS Cut Line= 4
2243269.32361488560617.0429164832243495.90638438560606.045832453
2244144.77657485560743.2302407822244573.80844469560686.370786323
#Sta/Elev= 30
       0 2536.83    56.1 2515.66    66.9 2508.24      87 2507.01     139 2475.27
     151 2473.49   179.1 2449.24   187.1 2444.94   211.1 2425.26   227.1 2416.06
   366.1 2411.56   378.4 2414.15   594.2 2410.53   770.9 2411.95   779.1 2408.86
     790 2408.64   852.7 2408.68   864.9 2410.45   962.1 2408.46   994.4 2410.06
  1010.5 2409.68  1022.6 2406.06  1042.8 2408.48  1099.3 2407.37  1139.6 2414.74
  1183.5 2416.82  1200.1 2432.28  1224.4 2445.43  1256.6 2474.87  1322.8 2506.67
#Mann= 5 ,-1,0
       0      .1       0     790    .045       0   852.7      .1       0
 1090.06     .06       0 1190.06      .1       0
#XS Ineff= 2 , 0
          770.13 2431.94
Permanent Ineff=
       F       F
Bank Sta=790,852.7
XS Rating Curve= 0 ,0
Exp/Cntr=0.3,0.1

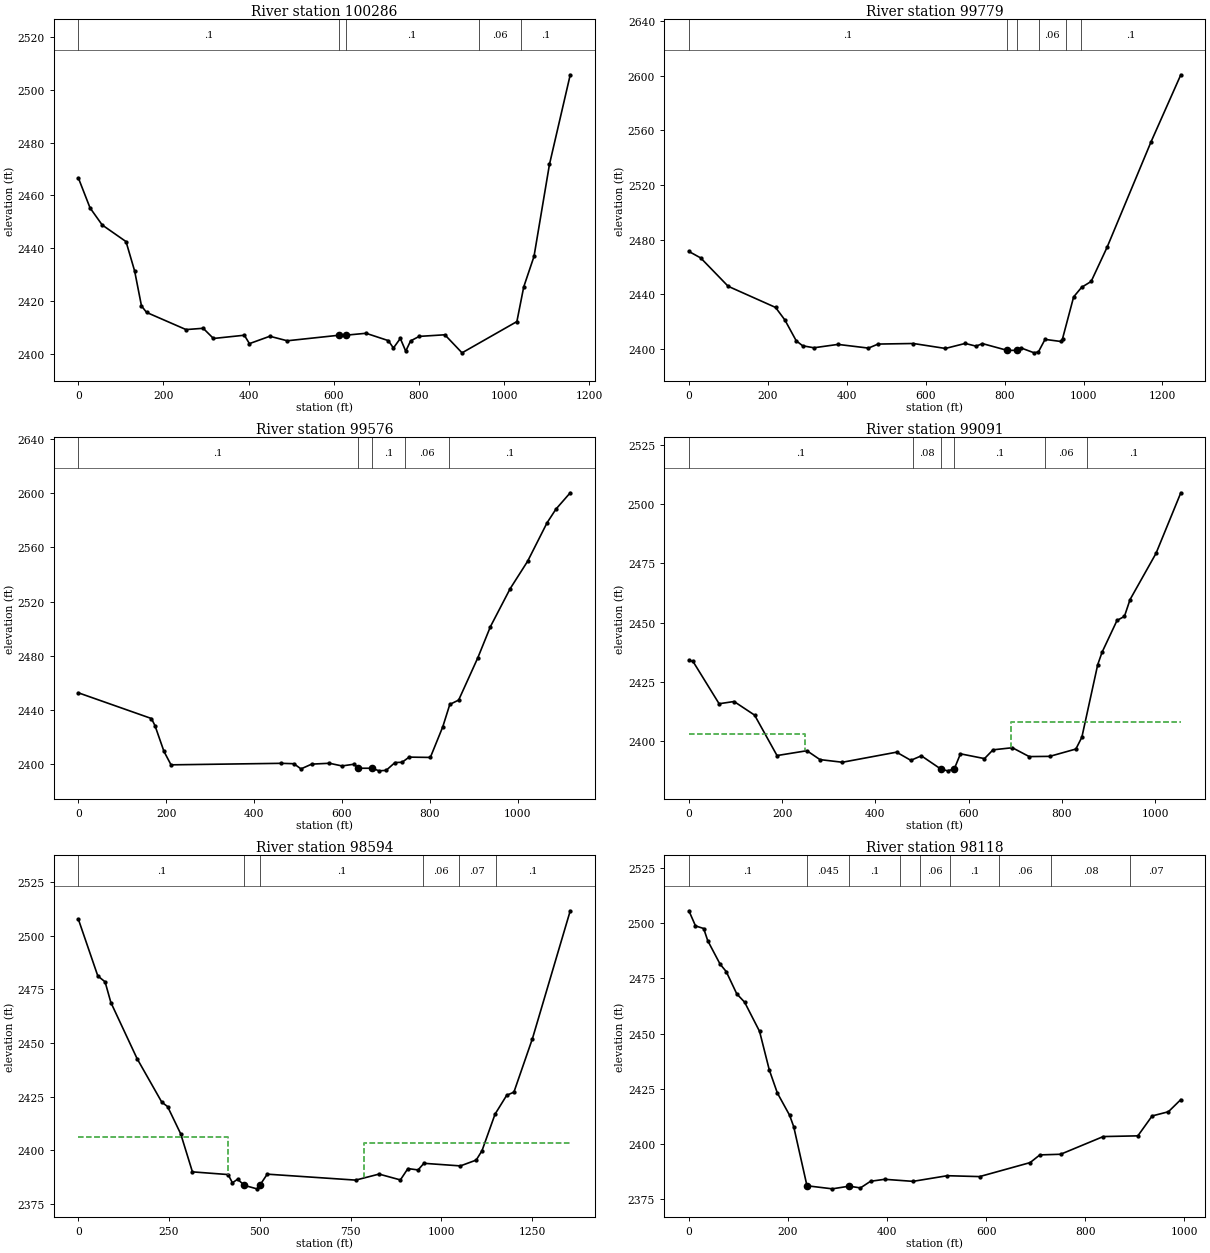
Type RM Length L Ch R = 1 ,100286  ,507.3,507.3,507.3
XS GIS Cut Line= 2
2243412.85196138 561119.92505018 2244560.6718339560990.642446578
#Sta/Elev= 30
       0 2466.64    27.5 2455.26    56.1 2448.78     112 2442.49   132.2 2431.37
   148.3 2418.12   160.3 2415.66   252.9 2409.16   293.2 2409.65   317.3 2405.79
   389.8 2407.02   401.8 2403.84   449.7 2406.63   490.6 2404.92   611.92407.016
   627.8 2407.03   675.6 2407.76   727.9 2404.98   739.9 2402.17   756.1 2405.81
   768.8 2400.98   780.2 2404.87   800.4 2406.58   860.7 2407.19     901 2400.35
  1029.8 2412.19  1045.9 2425.34    1070 2436.87  1106.3 2471.73  1155.1 2505.68
#Mann= 5 ,-1,0
       0      .1       0   611.9    .045       0   627.8      .1       0
     940     .06       0    1040      .1       0
Bank Sta=611.9,627.8
XS Rating Curve= 0 ,0
Exp/Cntr(USF)=0,0
Exp/Cntr=0.3,0.1

Type RM Length L Ch R = 1 ,99779   ,202.5,202.5,202.5
XS GIS Cut Line= 5
2243479.04889528561423.308511817 2243752.6388375561360.414272226
2244200.76029458561280.2241167492244348.56175761 561338.40128837
2244697.62478734561294.375320657
#Sta/Elev= 30
       0 2471.47    29.9 2466.73    99.5 2445.99   219.6 2430.53   243.3 2421.31
     272 2406.11   288.4 2402.45   316.8 2401.02   377.8 2403.48     455 2400.78
   479.4 2403.73   568.8 2404.14     650 2400.52   700.2 2404.19   727.7  2402.2
   743.9 2404.07   807.2 2399.08   831.9 2399.16   841.1 2400.95     875 2397.31
   885.8 2398.04   902.5 2407.15   942.8 2405.61   946.8 2407.58     975 2438.24
   995.2 2445.23  1019.4 2449.54  1059.7  2474.5  1171.2  2551.7  1246.6 2600.71
#Mann= 6 ,-1,0
       0      .1       0   807.2    .045       0   831.9      .1       0
  885.97     .06       0  954.81     .08       0  994.81      .1       0
Bank Sta=807.2,831.9
XS Rating Curve= 0 ,0
Exp/Cntr(USF)=0,0
Exp/Cntr=0.3,0.1

Type RM Length L Ch R = 1 ,99576   ,485.3,485.3,485.3
XS GIS Cut Line= 3
2243607.94850646561604.2531670342244203.80805354561508.827087316
     2244716.662      561454.153
#Sta/Elev= 30
       0 2452.64   166.3 2433.64   174.4 2428.38   194.9 2409.31   210.9 2399.43
     462 2400.55   490.4 2400.26   506.6 2396.43   530.9 2399.96   571.4 2400.59
   599.8 2398.62     628 2399.93   636.2 2396.92   668.2 2396.91   684.3    2395
   700.4 2395.37   720.5 2401.13   736.6 2401.33   752.7 2405.13   800.9  2404.9
   829.1 2427.45   845.2 2444.06   865.3 2447.26   908.8 2478.41   937.7 2501.58
   982.5 2529.54  1022.2 2549.78  1066.4 2578.16  1086.5 2588.22  1119.2 2600.36
#Mann= 5 ,-1,0
       0      .1       0   636.2    .045       0   668.2      .1       0
  743.45     .06       0  843.45      .1       0
Bank Sta=636.2,668.2
XS Rating Curve= 0 ,0
Exp/Cntr=0.3,0.1

Type RM Length L Ch R = 1 ,99091   ,496.6,496.6,496.6
XS GIS Cut Line= 4
2243615.45613783561938.5646989912244076.24584862561913.249284887
2244249.28104116562016.247928536 2244640.8451501561993.660232873
#Sta/Elev= 30
       0 2434.16     8.7 2433.74    64.8 2415.88    96.9 2416.82   140.9 2411.09
     189 2394.04   253.1 2396.08   281.1 2392.34   329.2 2391.22   445.4 2395.47
     476 2392.03   498.6 2393.93   540.2 2388.38   554.8  2387.6  569.142388.377
   582.4 2394.77     634 2392.76   652.3 2396.46   693.8 2397.34   729.9 2393.61
   773.9  2393.7     830 2396.79   842.8 2401.74   876.8 2432.31   886.1 2437.56
   918.2 2450.97   934.2 2452.73   946.2 2459.79  1001.9 2479.27  1055.1  2504.8
#Mann= 6 ,-1,0
       0      .1       0  481.48     .08       0   540.2    .045       0
  569.14      .1       0  762.85     .06       0  852.85      .1       0
#XS Ineff= 2 , 0
          249.04 2403.05  690.04         2408.36
Permanent Ineff=
       F       F
Bank Sta=540.2,569.14
XS Rating Curve= 0 ,0
Exp/Cntr=0.3,0.1

Type RM Length L Ch R = 1 ,98594   ,476.7,476.7,476.7
XS GIS Cut Line= 4
2243442.62020051562310.5475828322243756.39943272562290.758246272
2243985.61219297562443.0303758272244751.31188925562425.886073402
#Sta/Elev= 30
       0 2507.82    53.7  2481.3    73.7 2478.56    89.7 2468.91   161.9 2442.73
     230 2422.42     246 2420.35   282.1 2407.64   314.4  2389.9   412.8 2388.64
   424.6 2384.79     439 2386.48   457.4 2383.61     492 2381.98   500.7  2383.8
   520.6 2388.83   764.2 2386.05   828.7 2388.86   887.4 2386.14   908.2 2391.43
   936.2  2390.8   952.2 2393.89  1052.8 2392.68  1096.3 2395.39  1112.3 2399.76
  1148.3 2416.83  1180.3  2425.6  1200.3 2427.11  1251.4 2452.11  1355.5 2511.71
#Mann= 6 ,-1,0
       0      .1       0   457.4    .045       0   500.7      .1       0
  949.58     .06       0 1049.58     .07       0 1149.58      .1       0
#XS Ineff= 2 , 0
          411.78 2406.14  786.37          2403.3
Permanent Ineff=
       F       F
Bank Sta=457.4,500.7
XS Rating Curve= 0 ,0
Exp/Cntr=0.3,0.1

Type RM Length L Ch R = 1 ,98118   ,530.6,530.6,530.6
XS GIS Cut Line= 4
2243631.28148528562909.9030237322243850.94967384562853.451133186
2244306.23738031562764.4623544312244600.60346067562832.133981494
#Sta/Elev= 30
       0 2505.74    13.3 2498.88    29.8 2497.69    38.1 2492.11    62.9 2481.53
    75.3 2478.15    96.6 2468.02   112.4 2464.25   142.6 2450.99   162.3 2433.44
   178.5 2423.01   203.3 2412.87   211.6 2407.65  238.292380.876   289.4 2379.48
  323.432380.691   346.2  2379.9   366.6 2382.91     395 2383.81   452.2 2382.88
   521.5 2385.44   586.7 2385.04   688.6 2391.39   708.3 2394.89   750.2 2395.18
   836.3 2403.22   906.1 2403.54   934.9 2412.58   967.7 2414.48   992.8 2420.01
#Mann= 9 ,-1,0
       0      .1       0  238.29    .045       0  323.43      .1       0
  426.81     .05       0  466.81     .06       0  526.81      .1       0
  626.81     .06       0  730.71     .08       0  890.71     .07       0
Bank Sta=238.29,323.43
XS Rating Curve= 0 ,0
Exp/Cntr=0.3,0.1

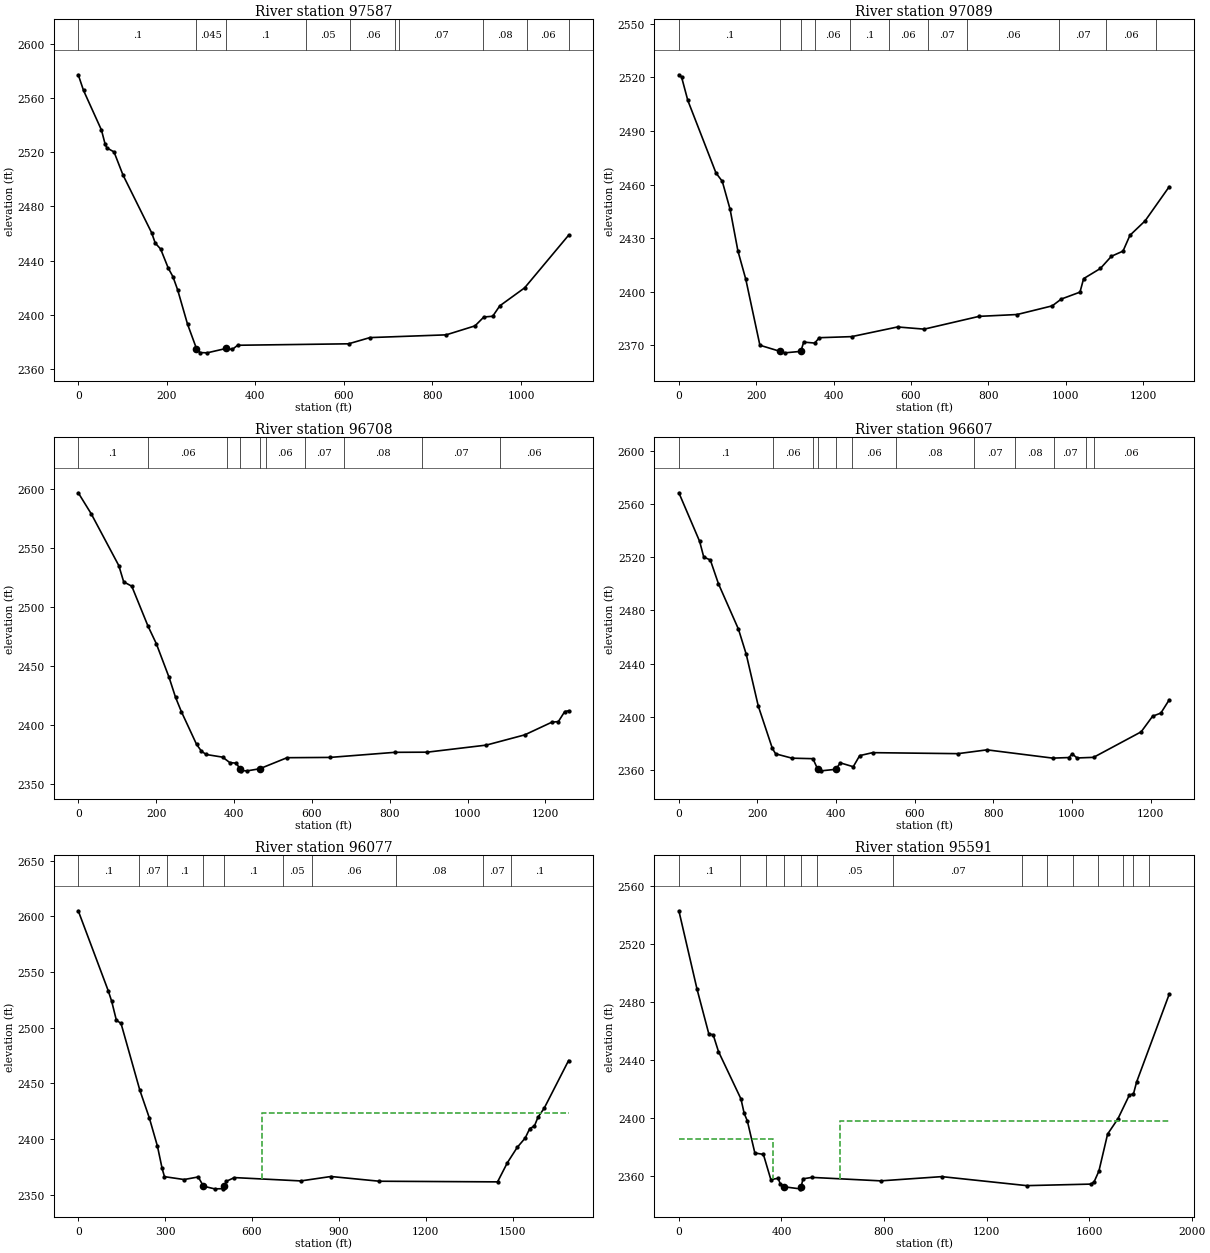
Type RM Length L Ch R = 1 ,97587   ,498.4,498.4,498.4
XS GIS Cut Line= 4
2243636.41510756 563406.290463652243887.99663136563366.244373265
2244382.30828689563296.0983607032244735.34367949563278.294172852
#Sta/Elev= 30
       0 2577.13    11.9  2565.6    52.4 2536.38    60.5 2526.24    64.6 2523.21
    80.8 2520.22     101 2503.24   165.8 2460.56   173.9 2452.96   186.1 2448.57
   203.4 2434.43   213.9 2428.16   224.4 2418.58   246.8 2393.18     267 2375.18
   275.1 2372.21   291.2    2372   333.7 2375.22   333.7 2375.23   347.9  2374.5
     360 2377.59   610.5 2378.66   658.9 2383.25     831 2385.27   896.1 2391.89
   916.1 2398.44   936.1 2398.99   952.1 2406.67  1008.2 2419.94  1107.5 2458.76
#Mann= 10 ,-1,0
       0      .1       0     267    .045       0   333.7      .1       0
  514.75     .05       0  614.75     .06       0  714.75     .08       0
  724.75     .07       0  914.01     .08       0 1014.01     .06       0
  1107.5      .1       0
Bank Sta=267,333.7
XS Rating Curve= 0 ,0
Exp/Cntr=0.3,0.1

Type RM Length L Ch R = 1 ,97089   ,380.7,380.7,380.7
XS GIS Cut Line= 4
2243705.38431991563801.5066221082243905.85164061563833.892508072
2244430.59653449563913.9544066732244877.07078363564206.691537137
#Sta/Elev= 30
       0 2521.42     6.9 2520.21    23.1 2507.09      96 2466.46   112.2 2461.83
   132.5 2446.08   152.7 2422.82   173.1 2406.94   209.5  2370.1   262.1 2366.63
   274.2 2365.84  315.232366.664   322.8 2371.84   351.1 2371.31   363.2 2374.31
   446.7 2374.91   565.5 2380.32   634.3  2379.1   776.2 2386.25   874.5 2387.28
   965.4 2392.13   988.7 2395.93  1037.1 2399.81  1046.5 2407.36  1089.8 2413.04
  1118.4 2419.88  1148.3 2422.75  1166.3 2431.61  1205.4 2439.67  1267.8  2458.8
#Mann= 11 ,-1,0
       0      .1       0   262.1    .045       0  315.23      .1       0
  353.07     .06       0  443.07      .1       0  543.07     .06       0
  643.07     .07       0  743.88     .06       0  983.88     .07       0
 1103.88     .06       0 1233.88      .1       0
Bank Sta=262.1,315.23
XS Rating Curve= 0 ,0
Exp/Cntr=0.3,0.1

Type RM Length L Ch R = 1 ,96708   ,101.4,101.4,101.4
BEGIN DESCRIPTION:
structure
END DESCRIPTION:
XS GIS Cut Line= 4
2243484.13512464564160.9751354442243764.23763927564242.178400152
2244265.72675302564143.3245811352244709.72207727564249.332547747
#Sta/Elev= 30
       0 2596.87    33.4 2578.98   104.2 2535.03   116.7 2521.26   137.5 2517.55
   179.1 2483.73   200.4 2468.86   233.3 2440.13   249.9 2423.21   264.9 2411.04
   303.8 2383.34     316 2377.68   328.3 2374.72   370.8 2372.45   389.4 2367.78
   405.7 2367.38  415.242362.613     418 2360.96   434.3 2360.83   466.1 2362.61
   536.2 2371.98   646.3 2372.22   813.5 2376.55     896 2376.67  1047.9 2382.67
  1146.6 2391.36  1216.5 2402.15    1233 2402.62  1249.4 2411.16  1259.3 2411.82
#Mann= 10 ,-1,0
       0      .1       0     180     .06       0  381.64     .07       0
  415.24    .045       0   466.1     .07       0  481.64     .06       0
  581.64     .07       0  681.64     .08       0  882.78     .07       0
 1082.78     .06       0
Bank Sta=415.24,466.1
XS Rating Curve= 0 ,0
Exp/Cntr=0.3,0.1

Type RM Length L Ch R = 1 ,96607   ,529.9,529.9,529.9
BEGIN DESCRIPTION:
structure
END DESCRIPTION:
XS GIS Cut Line= 4
2243519.22100262564252.8997758742243799.97169034564332.158521319
 2244300.6605904564219.7010695962244724.60007884564346.996476624
#Sta/Elev= 30
       0  2568.4    52.9 2531.81    63.3 2520.06      80 2517.89   100.7    2500
   151.6 2465.86   171.4 2446.99     202 2408.09   237.9 2376.18   246.2 2372.14
   287.8 2368.88   341.1  2368.5   353.4 2360.48   362.1 2359.36   399.1 2360.51
   410.8 2365.36   443.6 2362.45     460 2370.79   492.8 2373.03   710.1 2372.28
   783.9 2375.14   951.2 2368.92     992 2369.35  1000.7 2372.05  1013.2 2369.04
    1055  2369.5  1176.1 2388.68  1205.3 2400.43  1226.2 2402.78  1247.5 2412.73
#Mann= 12 ,-1,0
       0      .1       0     240     .06       0  341.72     .05       0
   353.4    .045       0   399.1     .05       0  441.72     .06       0
  551.72     .08       0  751.72     .07       0  854.89     .08       0
  954.89     .07       0 1034.89     .08       0 1054.89     .06       0
Bank Sta=353.4,399.1
XS Rating Curve= 0 ,0
Exp/Cntr=0.3,0.1

Type RM Length L Ch R = 1 ,96077   ,485.9,485.9,485.9
XS GIS Cut Line= 4
2243350.30744132564769.4585327452243642.89855336564817.835562199
2244775.81034063564931.1315265832245019.71340705564845.778853561
#Sta/Elev= 30
       0 2605.09   103.3 2533.45   115.4 2523.84   131.6 2506.88   147.8 2503.85
   212.7 2443.93   245.2 2419.27   273.5 2393.66   289.7 2373.61   297.8 2366.26
   365.7 2363.69   414.4 2366.01  432.31 2357.72   470.7 2355.33   498.8 2355.45
  504.822357.719   510.9    2362     539 2365.44   768.6 2362.44   872.7 2366.41
  1040.2 2362.16  1448.2 2361.59  1482.1 2378.79    1516 2392.54  1543.7 2400.98
  1559.4  2409.5  1575.4 2411.71  1587.6 2419.56  1609.3 2427.79  1693.5 2470.59
#Mann= 10 ,-1,0
       0      .1       0     210     .07       0  306.56      .1       0
  432.31    .045       0  504.82      .1       0  706.56     .05       0
  806.56     .06       0 1096.56     .08       0 1396.56     .07       0
 1495.13      .1       0
#XS Ineff= 2 , 0
                          634.22         2423.45
Permanent Ineff=
       F       F
Bank Sta=432.31,504.82
XS Rating Curve= 0 ,0
Exp/Cntr=0.3,0.1

Type RM Length L Ch R = 1 ,95591   ,505.4,505.4,505.4
XS GIS Cut Line= 4
2243327.93968432565203.4723249342243670.26282106565304.103076329
2244933.32047377565484.3470394192245210.15404924565445.685114032
#Sta/Elev= 30
       0  2542.7    71.1 2488.48     117 2457.71   133.7 2457.25   154.5 2445.64
   242.1 2413.01   254.6 2403.12   267.1 2397.76   296.3 2375.73   329.6 2374.75
   358.7 2357.38     387 2358.29   395.1 2354.59   411.3  2352.4   471.9 2351.01
  476.652352.222     484  2357.9   518.6  2358.9     787 2356.51  1025.4 2359.43
  1356.6 2353.22  1607.3 2354.28  1619.4 2355.87    1638 2363.25  1671.9 2388.75
  1712.3 2399.34  1756.7 2415.63  1772.9 2416.52    1785 2424.64  1912.2 2485.19
#Mann= 14 ,-1,0
       0      .1       0     240     .06       0     340      .1       0
   411.3    .045       0  476.65      .1       0  536.81     .05       0
  836.81     .07       0 1336.81     .05       0 1436.81     .07       0
 1536.81      .1       0 1632.66     .12       0 1732.66      .1       0
 1772.66     .12       0 1832.66      .1       0
#XS Ineff= 2 , 0
          366.65 2385.06   629.6         2397.93
Permanent Ineff=
       F       F
Bank Sta=411.3,476.65
XS Rating Curve= 0 ,0
Exp/Cntr=0.3,0.1