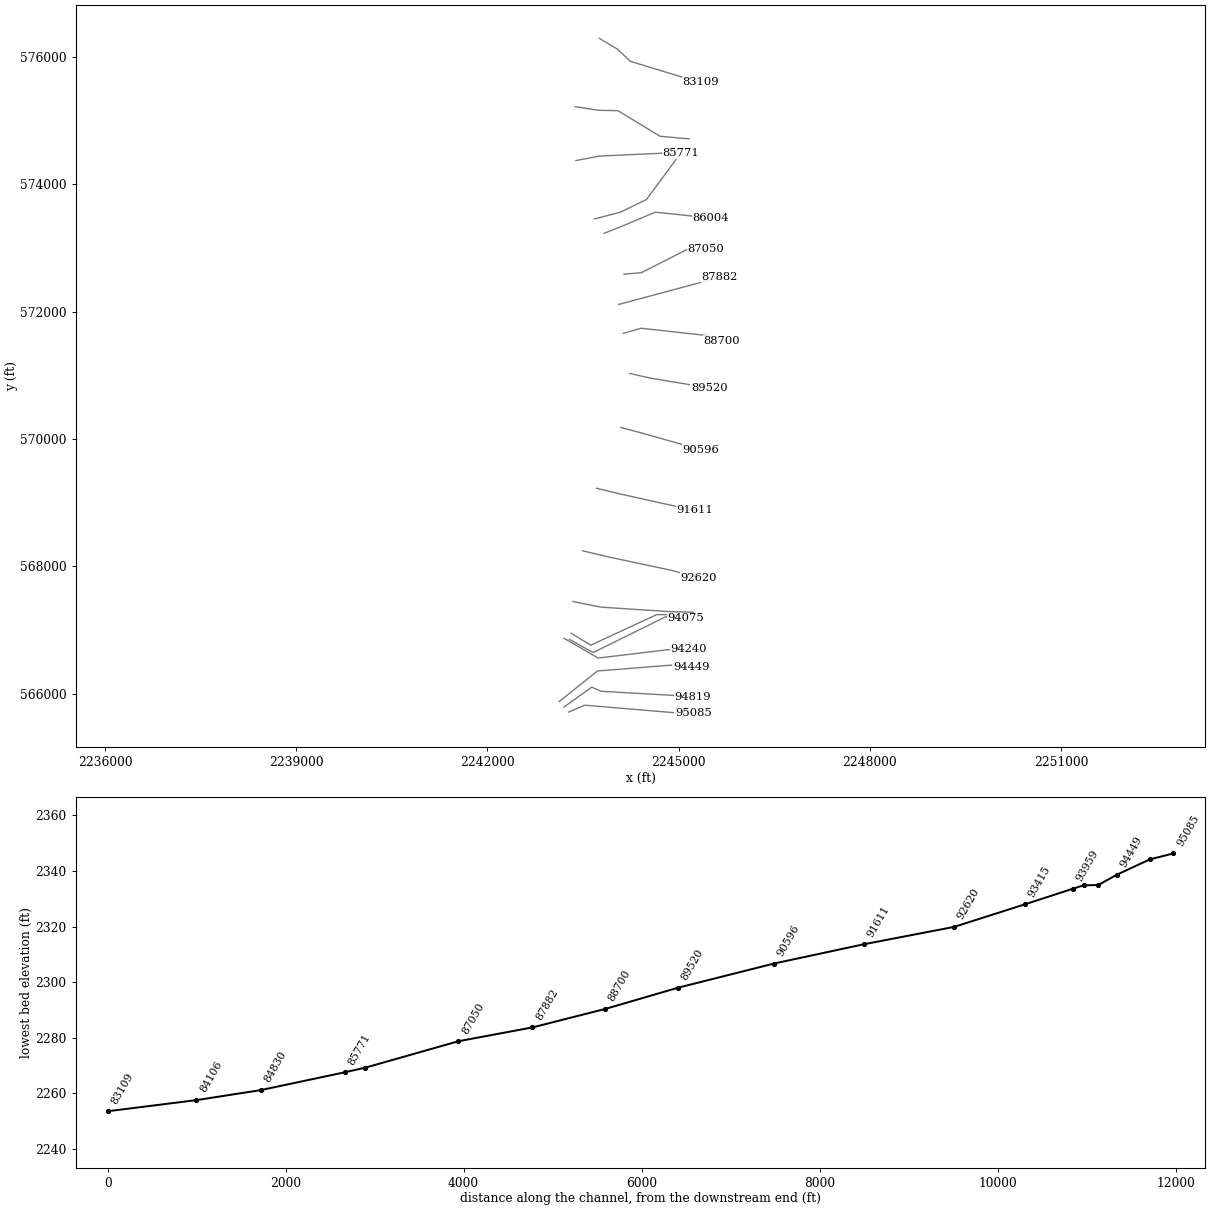
HEC-RAS study TYGVRV2.prj: TYGVRV2

--- TYGVRV2.g01 (geometry) --- (continued)

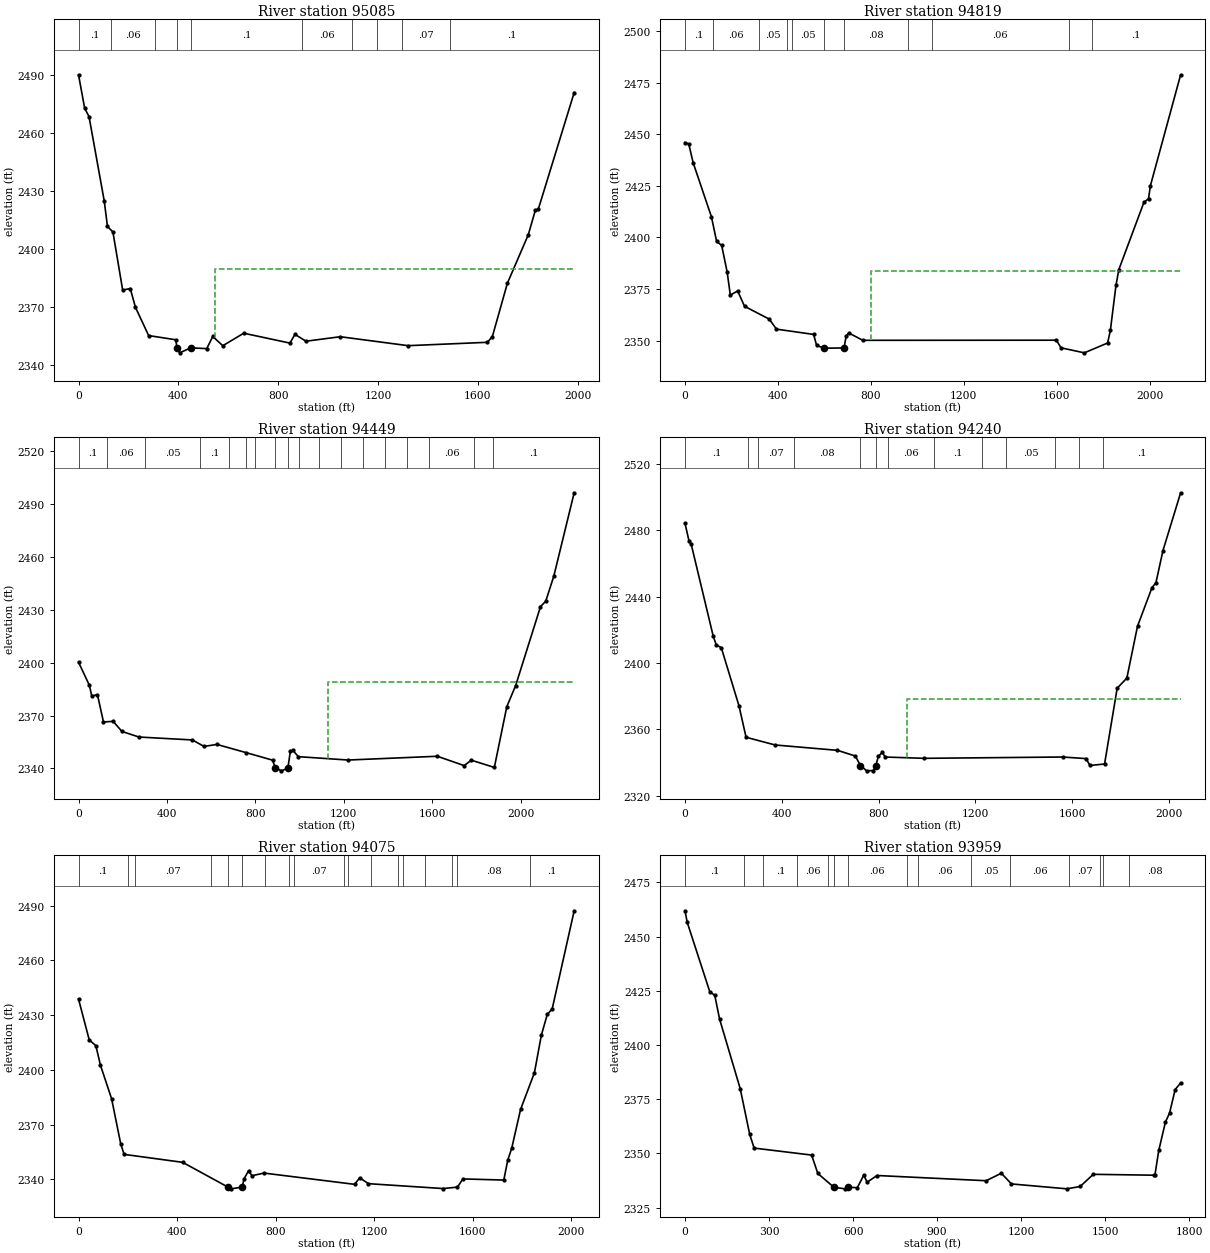
Type RM Length L Ch R = 1 ,95085   ,266.3,266.3,266.3
XS GIS Cut Line= 4
2243273.40611517565712.843387144 2243527.8610132565821.178054931
2244892.89329757565706.0027700392245231.58097724565692.427437213
#Sta/Elev= 30
       0 2489.86    24.7 2472.55    42.1 2468.27     103 2424.75     116 2411.56
   137.8 2408.71   176.9  2378.7   207.3 2379.53     228 2369.83   280.9 2355.24
   389.3 2353.07  394.772348.748   405.3 2346.32   449.5 2348.89   513.7  2348.5
   537.8 2354.78   577.9 2349.99   661.8 2356.45   846.8 2351.35     867 2355.86
   911.1 2352.32  1048.5 2354.64  1320.3 2350.02  1637.7 2351.76  1657.7 2354.68
  1717.8 2382.22  1801.8 2407.34  1829.9 2419.97  1841.9 2420.54  1985.4 2480.65
#Mann= 10 ,-1,0
       0      .1       0     130     .06       0  306.56      .1       0
  394.77    .045       0   449.5      .1       0  896.56     .06       0
 1096.56     .07       0 1196.56     .06       0 1296.56     .07       0
 1486.56      .1       0
#XS Ineff= 2 , 0
                          545.85         2389.66
Permanent Ineff=
       F       F
Bank Sta=394.77,449.5
XS Rating Curve= 0 ,0
Exp/Cntr=0.3,0.1

Type RM Length L Ch R = 1 ,94819   ,370.3,370.3,370.3
XS GIS Cut Line= 4
2243199.56792407565791.7375188012243636.36363144566103.346183835
2243788.79446546566039.2956314112245218.11315916565957.433987063
#Sta/Elev= 30
       0 2445.95    16.3  2445.3    35.1 2436.22   113.8 2410.04   136.3 2398.09
     158 2396.15   181.6 2383.24   195.3 2372.09   226.8 2374.13   256.3 2366.69
   362.8 2360.48   393.8 2355.63   553.7 2353.08   566.7 2347.73  600.092346.409
   684.7 2346.53   693.9 2352.32   705.3 2353.78   765.4 2350.22  1598.7 2350.28
  1618.8 2346.59    1719 2344.16  1819.1 2348.91  1831.1    2355  1855.3 2376.82
  1867.7  2384.5  1975.4 2416.96  1995.4 2418.81  2003.4 2425.03  2133.6 2478.76
#Mann= 11 ,-1,0
       0      .1       0     120     .06       0     320     .05       0
     440      .1       0     460     .05       0  600.09    .045       0
   684.7     .08       0   961.9     .07       0  1061.9     .06       0
  1651.9     .07       0  1751.9      .1       0
#XS Ineff= 2 , 0
                             800         2383.93
Permanent Ineff=
       F       F
Bank Sta=600.09,684.7
XS Rating Curve= 0 ,0
Exp/Cntr=0.3,0.1

Type RM Length L Ch R = 1 ,94449   ,208.4,208.4,208.4
XS GIS Cut Line= 4
2243126.48799508565878.5807402862243725.61769702566357.884501836
2244861.56761189 566448.95221653 2245196.1236099566421.965902548
#Sta/Elev= 30
       0 2400.31      49 2387.21      60 2381.08    85.6 2381.89     113 2366.35
   156.7 2366.72   196.6 2360.98   273.4 2357.82   515.3 2356.16   567.6  2352.5
   626.3 2353.62     760 2348.91   878.2 2344.69  889.892340.366   918.3 2338.64
  947.162340.165   958.4 2349.69   969.6  2350.3   994.5 2346.69  1219.3 2344.77
  1623.4 2346.91  1744.9 2341.61    1777 2344.68  1881.4 2340.57  1937.6 2374.97
  1977.7    2387  2090.1 2431.77  2114.1 2434.96  2150.3 2449.03  2242.5 2496.39
#Mann= 18 ,-1,0
       0      .1       0     130     .06       0     300     .05       0
     550      .1       0     680     .06       0     760     .07       0
  797.26     .06       0  889.89    .045       0  947.16     .06       0
  997.26     .08       0 1087.26     .07       0 1187.26     .06       0
 1287.26     .07       0 1387.26     .08       0 1487.26     .07       0
 1587.26     .06       0 1787.26     .07       0 1877.26      .1       0
#XS Ineff= 2 , 0
                         1128.16          2388.9
Permanent Ineff=
       F       F
Bank Sta=889.89,947.16
XS Rating Curve= 0 ,0
Exp/Cntr(USF)=0,0
Exp/Cntr=0.3,0.1

Type RM Length L Ch R = 1 ,94240   ,165.2,165.2,165.2
XS GIS Cut Line= 4
2243201.81164898 566871.851989432243736.25627007566561.740939811
2244850.14924085566694.1802892492245158.45240574 566696.45584654
#Sta/Elev= 30
       0 2484.32    16.6 2473.63    25.9 2471.52   116.9 2416.05   129.5 2410.86
     150 2409.27   223.2 2374.12   252.4 2355.19   372.4 2350.54   629.9 2347.31
   703.7 2343.89  725.172338.136   750.7 2334.94   778.5 2335.11  788.552338.137
   799.1 2343.75   815.2 2346.04   827.3 2343.27   988.4 2342.49  1560.6 2343.28
  1657.1 2342.32  1673.2 2338.17  1733.6 2339.06  1785.7 2384.79  1825.7 2390.89
  1869.7 2422.17  1929.7 2445.53  1945.7 2448.32  1974.9 2467.84  2047.9 2502.68
#Mann= 13 ,-1,0
       0      .1       0     260     .06       0     300     .07       0
     450     .08       0  725.17    .045       0  788.55     .08       0
   837.9     .06       0  1027.9      .1       0  1227.9     .06       0
  1327.9     .05       0  1527.9      .1       0  1627.9     .06       0
  1727.9      .1       0
#XS Ineff= 2 , 0
                          918.33          2378.3
Permanent Ineff=
       F       F
Bank Sta=725.17,788.55
XS Rating Curve= 0 ,0
Exp/Cntr(USF)=0,0
Exp/Cntr=0.3,0.1

Type RM Length L Ch R = 1 ,94075   ,115.9,115.9,115.9
BEGIN DESCRIPTION:
structure
END DESCRIPTION:
XS GIS Cut Line= 4
2243286.40989717566854.2376248932243659.08693827566647.660288585
2244796.32743475567209.7765608042245112.97833981567185.476469191
#Sta/Elev= 30
       0 2438.87    43.4 2416.53    70.6 2413.24    88.9 2402.67   134.5 2384.13
   171.2 2359.61     185 2353.73   422.8 2349.37  605.682335.874   619.2 2334.84
  664.272335.782   672.7 2340.49   690.6  2344.8     704 2342.01     753 2343.48
  1120.8 2337.31  1141.7 2340.91  1176.9 2337.67  1480.3    2335  1538.3 2335.77
  1560.7 2340.28  1726.6 2339.65  1742.7 2350.59  1758.7 2357.04  1794.8 2378.39
    1851 2398.49  1879.1 2419.07  1903.1 2430.41  1923.2 2433.52  2012.3 2487.23
#Mann= 18 ,-1,0
       0      .1       0     200     .06       0     230     .07       0
   536.1     .08       0  605.68    .045       0  664.27     .08       0
   756.1     .07       0   856.1     .06       0   876.1     .07       0
  1076.1     .05       0  1096.1     .07       0  1186.1     .06       0
  1296.1     .05       0  1316.1     .07       0  1406.1     .05       0
  1516.1      .1       0  1536.1     .08       0 1834.68      .1       0
Bank Sta=605.68,664.27
XS Rating Curve= 0 ,0
Exp/Cntr=0.3,0.1

Type RM Length L Ch R = 1 ,93959   ,544.4,544.4,544.4
BEGIN DESCRIPTION:
structure
END DESCRIPTION:
XS GIS Cut Line= 4
2243313.27332481566951.7602881642243621.93327082 566763.85460459
2244658.25321754 567244.301067752244923.78407152 567242.09932171
#Sta/Elev= 30
       0 2461.94     8.1 2456.57    88.4 2424.64   106.4 2422.91   123.3 2412.08
   197.3 2379.81     231 2358.79   246.9 2352.46     452 2349.24   474.1 2340.76
  531.412334.406     571 2333.66  580.262334.405   615.1 2334.19   638.2 2339.96
   650.2 2336.73   685.7 2339.81    1075  2337.4  1129.2 2340.86  1165.3 2335.92
  1363.1 2333.67  1410.6 2334.74  1457.3 2340.36  1673.6 2339.95  1677.6 2340.18
  1691.1 2351.35  1714.9 2364.44  1729.6  2368.6  1749.6 2379.42  1769.2 2382.54
#Mann= 15 ,-1,0
       0      .1       0     210     .06       0     280      .1       0
  401.36     .06       0  511.36     .07       0  531.41    .045       0
  580.26     .06       0  791.36      .1       0  831.36     .06       0
 1021.36     .05       0 1161.36     .06       0 1371.36     .07       0
 1481.36     .08       0 1491.36     .06       0 1583.63     .08       0
Bank Sta=531.41,580.26
XS Rating Curve= 0 ,0
Exp/Cntr=0.3,0.1

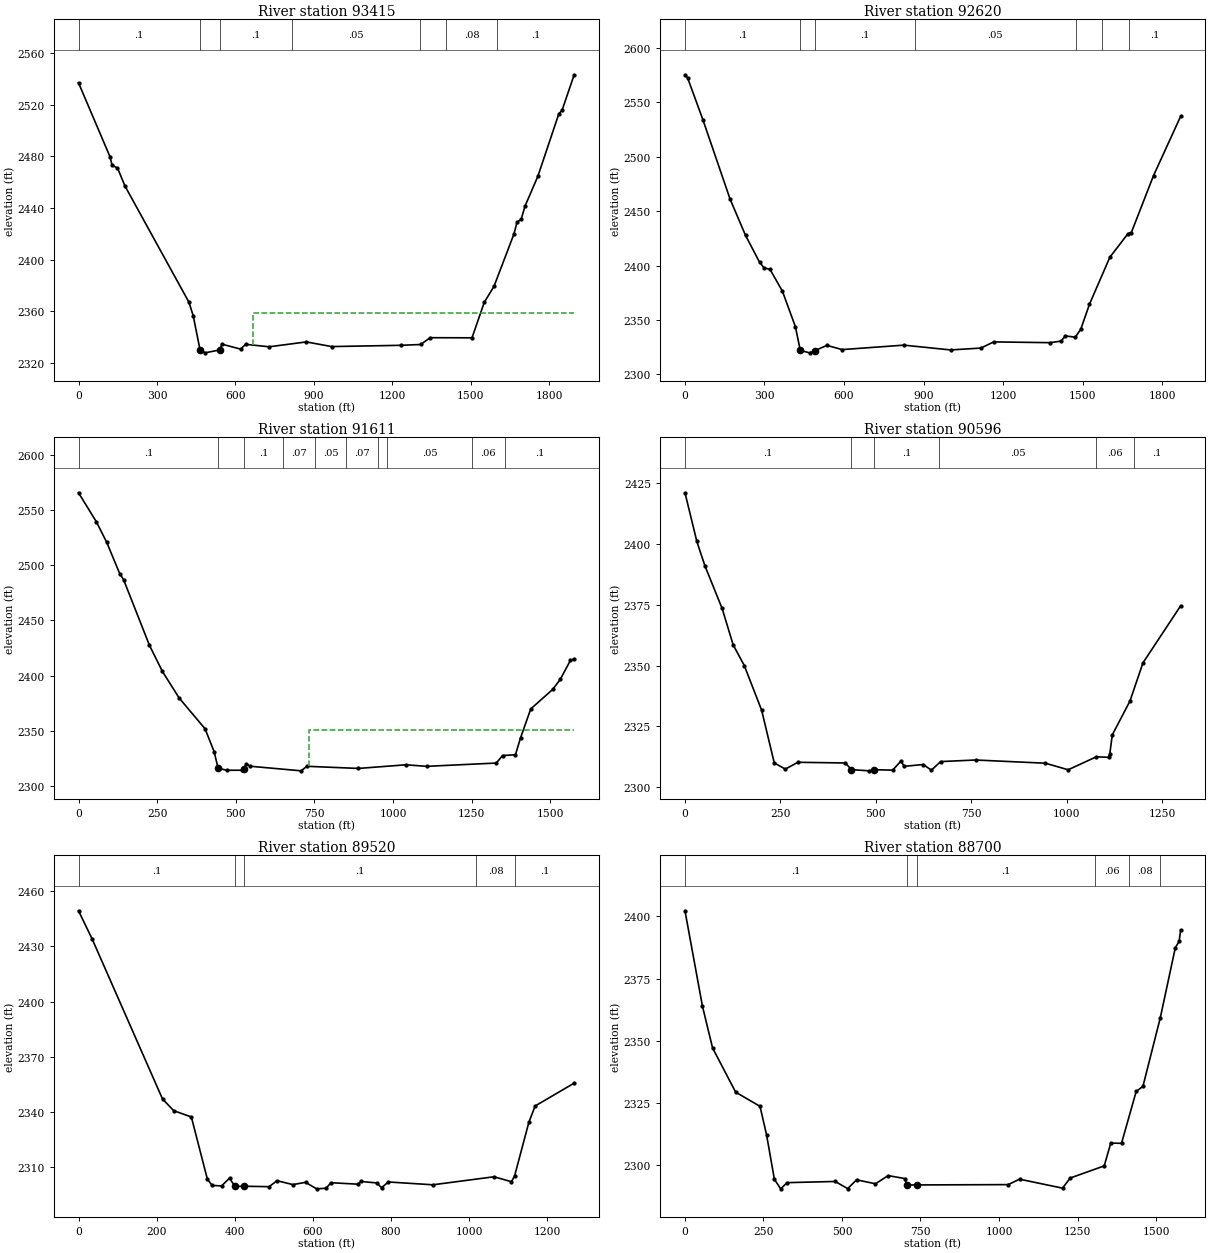
Type RM Length L Ch R = 1 ,93415   ,794.5,794.5,794.5
XS GIS Cut Line= 4
2243342.14354263567449.5461797732243780.02950291567361.158928579
2244840.32269919 567291.418449112245226.68851854 567282.06138057
#Sta/Elev= 30
       0  2536.8   120.4 2479.64   128.6 2472.91     149 2471.01   177.5 2457.06
   422.4 2367.12   438.7 2356.66  464.792330.301   484.4 2327.99  540.992330.302
   548.4 2334.69   619.9 2330.88   639.3 2334.57   728.9 2332.67   871.7 2336.44
     968 2332.83  1232.9 2333.81  1308.7 2334.44  1344.8  2339.7  1505.1 2339.61
    1552 2367.06  1589.2 2379.43  1665.2 2419.75  1677.2 2428.89  1693.2 2431.36
  1707.8 2441.44    1757 2464.56  1837.2 2512.86  1849.3 2515.44  1895.8 2543.02
#Mann= 7 ,-1,0
       0      .1       0  464.79    .045       0  540.99      .1       0
  816.72     .05       0 1306.72     .06       0 1406.72     .08       0
  1599.3      .1       0
#XS Ineff= 2 , 0
                          667.01         2358.88
Permanent Ineff=
       F       F
Bank Sta=464.79,540.99
XS Rating Curve= 0 ,0
Exp/Cntr=0.3,0.1

Type RM Length L Ch R = 1 ,92620   ,1009,1009,1009
XS GIS Cut Line= 4
2243494.48603762568246.1068871542243909.67133073568147.256962385
 2244886.3750926567939.4915690612245315.80189145567823.514307302
#Sta/Elev= 30
       0 2575.43      10 2572.54    67.5  2534.2   170.3 2461.09   228.5 2427.81
   281.3 2403.22   297.8 2398.06     321 2396.54   367.7  2376.5   416.6 2343.94
  435.042322.144   470.2 2319.88   490.7 2321.99   535.7 2326.74   592.9 2322.86
     826 2326.95  1001.9 2322.55  1116.4 2324.26    1165 2329.94  1378.2 2329.22
    1419 2330.69  1435.2 2335.42  1472.8 2334.28  1493.5  2341.6  1526.3 2364.58
    1603 2407.68  1671.7 2429.49  1684.1  2430.4    1768 2482.82  1870.2 2537.23
#Mann= 7 ,-1,0
       0      .1       0  435.04    .045       0   490.7      .1       0
  866.79     .05       0 1475.35     .06       0 1575.35     .12       0
 1675.35      .1       0
Bank Sta=435.04,490.7
XS Rating Curve= 0 ,0
Exp/Cntr=0.3,0.1

Type RM Length L Ch R = 1 ,91611   ,1016,1016,1016
XS GIS Cut Line= 4
2243712.84832281 569227.787714262244073.90110802569140.756966259
2245004.60179669568934.1177842292245251.77849339568888.257952436
#Sta/Elev= 30
       0  2565.6    56.9 2539.25    89.8 2520.65     131 2492.38   143.3 2486.91
   225.6 2427.37   266.8 2403.73   320.2 2379.59   402.4 2351.77   431.1 2331.17
     4442315.971   472.1 2314.19   521.2 2314.22  526.522315.756   533.5 2320.05
   545.8 2317.85   708.2 2313.67   726.1 2317.79     890 2315.85  1041.6 2319.15
  1107.6 2317.75  1328.4 2320.73  1348.7 2327.54  1389.4 2328.22  1405.7 2343.59
  1438.2 2369.79  1507.9 2387.43  1531.8 2396.44  1564.4 2413.76  1576.2 2415.17
#Mann= 10 ,-1,0
       0      .1       0     444    .045       0  526.52      .1       0
  651.39     .07       0  751.39     .05       0  851.39     .07       0
  951.39    .055       0  981.39     .05       0 1251.39     .06       0
 1354.76      .1       0
#XS Ineff= 2 , 0
                          734.26         2350.42
Permanent Ineff=
       F       F
Bank Sta=444,526.52
XS Rating Curve= 0 ,0
Exp/Cntr=0.3,0.1

Type RM Length L Ch R = 1 ,90596   ,1075.4,1075.4,1075.4
XS GIS Cut Line= 4
2244094.11662385570182.7644556382244467.71742914570083.272625985
2245063.59299046569913.9660709592245343.23188849 569828.26423048
#Sta/Elev= 30
       0 2421.12    31.1 2401.09      52 2391.16    97.3 2373.51   126.3 2358.52
   155.3 2350.04   200.8 2331.67   233.9 2309.95   262.9 2307.41     296 2310.21
   420.4 2309.92  436.042307.184   482.7 2306.69   495.2 2307.16   544.1 2306.97
   565.9 2310.72   574.2 2308.54   624.1 2309.29   645.6 2306.98   669.9  2310.5
   761.3 2311.15   944.3 2309.83    1004 2307.12  1077.6 2312.46  1109.7 2312.26
  1112.9 2313.58  1119.6 2321.52  1165.7 2335.36  1199.9 2351.13  1298.6 2374.59
#Mann= 6 ,-1,0
       0      .1       0  436.04    .045       0   495.2      .1       0
  666.62     .05       0 1076.08     .06       0 1176.08      .1       0
Bank Sta=436.04,495.2
XS Rating Curve= 0 ,0
Exp/Cntr=0.3,0.1

Type RM Length L Ch R = 1 ,89520   ,820.6,820.6,820.6
XS GIS Cut Line= 3
 2244234.2781164571030.6019876612244554.55231691 570958.70740719
2245482.63343877 570804.22469767
#Sta/Elev= 30
       0 2449.41    34.7 2434.14   215.1 2346.94   243.8 2340.56   288.9 2337.15
   329.9 2303.32   342.1 2299.87   366.4 2299.62   386.6 2303.84   400.5 2299.36
   424.8 2299.43     488  2299.2   508.4 2302.44   548.9 2300.33   581.3 2301.56
   609.7 2298.02     634 2298.33   646.2 2301.36   715.1 2300.56   723.2 2302.02
   763.8 2301.24   775.9 2298.59   793.3 2301.76   907.3 2300.22  1063.9 2304.59
  1108.5 2301.89  1116.5 2304.99  1153.1 2334.25  1169.3 2343.15  1269.1 2355.57
#Mann= 5 ,-1,0
       0      .1       0   400.5    .045       0   424.8      .1       0
 1018.24     .08       0 1118.24      .1       0
Bank Sta=400.5,424.8
XS Rating Curve= 0 ,0
Exp/Cntr=0.3,0.1

Type RM Length L Ch R = 1 ,88700   ,817.5,817.5,817.5
XS GIS Cut Line= 4
2244134.71496486571661.7609300122244409.88227997 571741.61866146
2245460.94252634571625.5815616972245680.76704295571544.073262241
#Sta/Elev= 30
       0 2402.26    55.6 2363.87    87.9 2347.04   161.4 2329.27   238.9 2323.57
   259.8 2312.11   284.7 2294.19   304.9 2290.36     325 2292.85     478 2293.33
   518.2 2290.45   546.4 2293.99   606.7  2292.4     647 2295.69   699.3 2294.51
  706.652291.916   738.4 2291.93  1029.3 2292.06  1065.5 2294.25  1202.4 2290.63
  1226.5  2294.7  1335.1  2299.6  1355.9 2308.77  1390.1 2308.68    1437  2329.6
  1458.3 2331.58  1513.8 2359.29  1561.5 2387.42  1573.5  2389.9  1578.4 2394.41
#Mann= 6 ,-1,0
       0      .1       0  706.65    .045       0   738.4      .1       0
 1306.52     .06       0 1413.97     .08       0 1513.97      .1       0
Bank Sta=706.65,738.4
XS Rating Curve= 0 ,0
Exp/Cntr=0.3,0.1

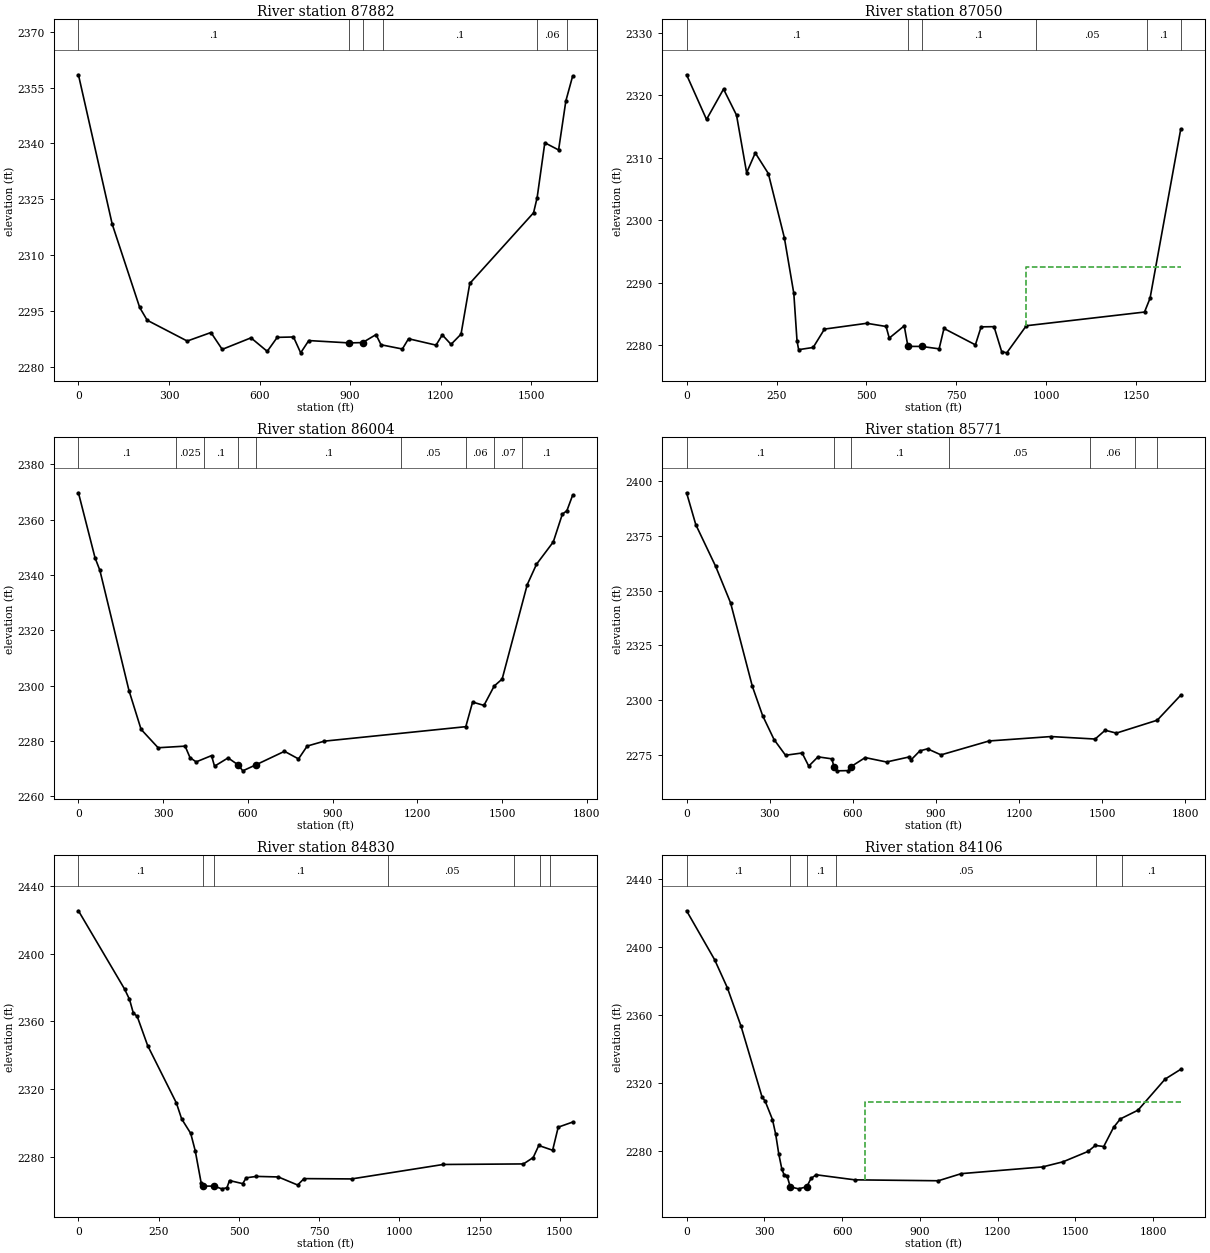
Type RM Length L Ch R = 1 ,87882   ,831.6,831.6,831.6
XS GIS Cut Line= 3
2244060.22700808572115.484156026 2245285.3071536572444.154991376
2245640.94866459572539.591563418
#Sta/Elev= 30
       0 2358.44   111.8 2318.32   202.9 2295.91   227.7 2292.48   360.3 2286.89
   438.9 2289.18   476.2 2284.65   571.5 2287.75   625.3 2284.12   658.4 2287.88
   712.3 2287.98   736.1 2283.72   762.9 2287.02   896.1 2286.39  941.092286.471
   985.6 2288.62  1002.2 2285.89  1072.9 2284.75  1093.3 2287.51  1184.4 2285.79
  1205.1 2288.54  1234.1    2286  1267.2 2288.74  1296.2 2302.37  1507.4 2321.35
  1519.3 2325.44  1544.7 2340.17  1590.3 2338.24  1614.4 2351.42  1636.6 2358.01
#Mann= 6 ,-1,0
       0      .1       0   896.1    .045       0  941.09     .08       0
    1010      .1       0  1518.4     .06       0  1618.4      .1       0
Bank Sta=896.1,941.09
XS Rating Curve= 0 ,0
Exp/Cntr(USF)=0,0
Exp/Cntr=0.3,0.1

Type RM Length L Ch R = 1 ,87050   ,1046.5,1046.5,1046.5
XS GIS Cut Line= 4
2244141.80134619572592.0607781432244413.26297195572612.730378198
2245141.42485538572983.0978002232245425.40046644572979.172788022
#Sta/Elev= 30
       0 2323.26    55.4 2316.11   102.7 2320.97   138.8  2316.8   166.9 2307.58
   190.9 2310.75   227.2 2307.45   271.7 2297.18     298 2288.27   306.9 2280.68
   311.4 2279.26   351.8 2279.61   383.2 2282.55   500.8 2283.48   554.4 2282.97
   563.3 2281.11   604.9 2283.07  615.132279.781  653.222279.775   701.8 2279.39
   715.3 2282.65   802.6 2280.03   818.5 2282.91   854.4 2282.94   875.6 2278.95
   889.8 2278.75   944.2 2283.09  1272.6 2285.28    1288 2287.49  1373.2 2314.54
#Mann= 6 ,-1,0
       0      .1       0  615.13    .045       0  653.22      .1       0
  972.25     .05       0 1279.19      .1       0 1373.19     .06       0
#XS Ineff= 2 , 0
                          943.14         2292.55
Permanent Ineff=
       F       F
Bank Sta=615.13,653.22
XS Rating Curve= 0 ,0
Exp/Cntr=0.3,0.1

Type RM Length L Ch R = 1 ,86004   ,233.4,233.4,233.4
XS GIS Cut Line= 4
2243829.49326272573232.6497557832244076.57651817573328.909485162
2244633.99717167573564.7581030622245508.16549684573472.783900273
#Sta/Elev= 30
       0 2369.66    58.7  2346.2    75.9 2341.66   178.9 2298.25   221.8 2284.22
   282.1 2277.58   377.7 2278.16     395 2274.02   416.8 2272.47   471.2 2274.74
   481.8 2270.91   529.7 2273.91  565.832271.373   581.8 2269.24   629.6 2271.47
   729.5 2276.29   779.1 2273.55   809.9 2278.19   870.4 2279.96  1371.4 2285.19
  1395.5 2294.07  1435.7 2292.88  1471.9 2299.86  1500.1 2302.39    1589  2336.5
  1621.7 2343.84  1681.1  2351.9  1713.2 2361.94  1729.3 2363.18  1749.4 2368.71
#Mann= 9 ,-1,0
       0      .1       0  345.17    .025       0  445.17      .1       0
  565.83    .045       0   629.6      .1       0 1140.43     .05       0
 1370.43     .06       0 1470.43     .07       0 1570.43      .1       0
Bank Sta=565.83,629.6
XS Rating Curve= 0 ,0
Exp/Cntr=0.3,0.1

Type RM Length L Ch R = 1 ,85771   ,940.7,940.7,940.7
XS GIS Cut Line= 4
2243678.54862958573458.1347281842244089.91260397573565.398086106
2244496.32542763573764.750352984 2245034.0108432574493.779529413
#Sta/Elev= 30
       0 2394.79    33.3 2380.19     105 2361.11   158.8 2344.44   237.3 2306.27
   274.5 2292.83   315.8 2281.86   357.2 2274.69     417 2275.73     441 2269.72
   474.3 2273.96   524.5 2273.05  532.462269.132   543.5 2267.56   583.6 2267.67
   592.5  2269.4   644.8 2273.62   721.7 2271.61   801.9 2273.87   810.8 2272.64
     842 2276.68   869.7 2277.64   918.4 2274.86    1092 2281.23  1315.6 2283.25
  1474.8 2282.11    1511 2286.13  1551.4 2284.82    1699 2290.73  1783.7 2302.16
#Mann= 7 ,-1,0
       0      .1       0  532.46    .045       0   592.5      .1       0
  947.79     .05       0 1457.79     .06       0 1617.79     .08       0
 1697.79      .1       0
Bank Sta=532.46,592.5
XS Rating Curve= 0 ,0
Exp/Cntr=0.3,0.1

Type RM Length L Ch R = 1 ,84830   ,723.9,723.9,723.9
XS GIS Cut Line= 4
2243388.35412952574375.3780126812243757.32219107574445.793519711
2244729.05245403 574489.933048662244905.53782827574562.838491136
#Sta/Elev= 30
       0 2425.23   143.5 2379.12     159 2373.01   170.8    2365   183.1 2362.91
   215.6  2345.7   305.2 2311.79   321.5 2302.44   349.8 2293.87   363.9 2283.58
   382.5 2264.45  388.412262.799   422.5 2262.77   446.7 2261.17   462.6 2261.82
   470.6 2266.06   511.8 2264.24   522.6 2267.68   554.7 2268.51   622.7 2268.18
   682.8 2263.43   702.8  2267.2     851 2267.02  1136.1 2275.54  1386.4 2275.87
  1416.7 2279.64    1434 2286.75  1477.2 2283.94  1494.6 2297.56  1539.3 2300.54
#Mann= 7 ,-1,0
       0      .1       0  388.41    .045       0   422.5      .1       0
  965.63     .05       0 1358.36     .06       0 1438.36     .07       0
 1468.36      .1       0
Bank Sta=388.41,422.5
XS Rating Curve= 0 ,0
Exp/Cntr=0.3,0.1

Type RM Length L Ch R = 1 ,84106   ,997.1,997.1,997.1
XS GIS Cut Line= 5
2243376.84518201575222.5687372782243746.96219588575164.054124422
2244046.32112217575159.5866389072244710.89715591574756.474345289
2245164.06298056574715.964121343
#Sta/Elev= 30
       0 2421.04   108.2 2392.27   157.3 2375.77   209.9 2353.27   290.9 2311.68
     303 2309.16   331.4 2298.29   343.9 2289.58   355.7 2278.05   367.8    2269
   375.9 2265.95   387.9 2265.09   399.9 2258.75   431.9 2257.56  463.672258.755
   479.9 2263.64   499.9 2265.83   649.2 2262.85   971.3 2262.31  1059.9  2266.5
  1373.3 2270.44  1452.7 2273.47    1549 2279.57  1577.2 2283.09  1609.3 2282.43
  1647.3 2293.66  1673.5 2298.66  1741.8 2303.82  1846.2 2322.08  1906.4 2327.82
#Mann= 6 ,-1,0
       0      .1       0   399.9    .045       0  463.67      .1       0
  574.71     .05       0 1581.38     .06       0 1681.38      .1       0
#XS Ineff= 2 , 0
                          689.68         2308.46
Permanent Ineff=
       F       F
Bank Sta=399.9,463.67
XS Rating Curve= 0 ,0
Exp/Cntr=0.3,0.1

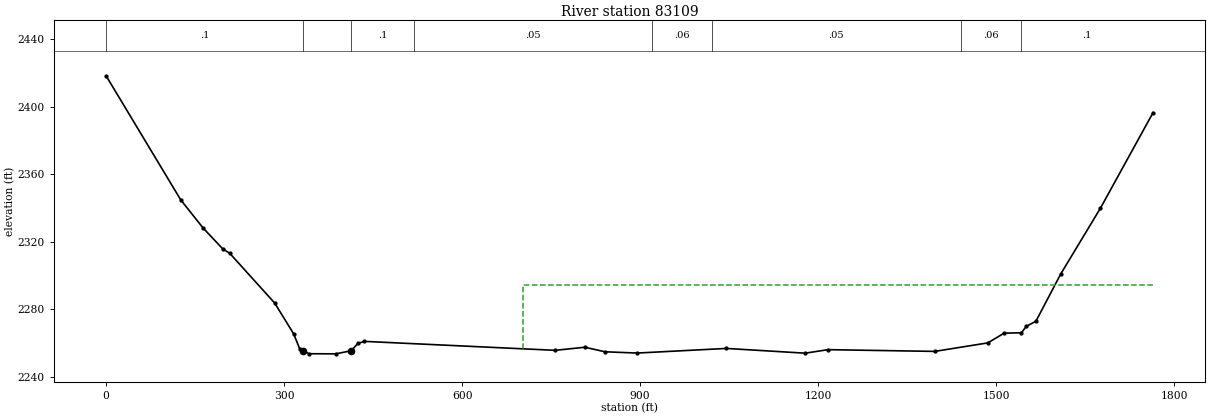
Type RM Length L Ch R = 1 ,83109   ,804.3,804.3,804.3
XS GIS Cut Line= 5
2243756.34043548 576295.147645242244038.54793982576126.215814652
2244244.05067009575933.758501972  2245068.190565575682.628981305
 2245349.5875742575602.546178133
#Sta/Elev= 30
       0 2418.26   125.7 2344.83     163 2328.31   196.7 2315.71   208.4 2313.11
   284.2 2283.64   316.3 2265.31   326.1 2256.71   331.42255.448   342.1 2253.62
   387.4 2253.56   413.3 2255.42   424.3 2259.72   435.3 2260.94   756.9 2255.64
   807.1 2257.47   840.6 2254.79   894.9 2254.02  1045.5 2256.76  1178.3 2253.95
  1216.8 2256.03  1396.7 2255.01  1486.1 2260.05  1513.6  2265.8  1542.7 2266.04
    1551 2269.85  1567.1 2272.85  1609.1 2300.93  1675.8 2339.78  1764.6 2396.44
#Mann= 8 ,-1,0
       0      .1       0   331.4    .045       0   413.3      .1       0
  518.91     .05       0  920.46     .06       0 1020.46     .05       0
 1440.46     .06       0 1542.01      .1       0
#XS Ineff= 2 , 0
                          703.25         2294.62
Permanent Ineff=
       F       F
Bank Sta=331.4,413.3
XS Rating Curve= 0 ,0
Exp/Cntr=0.3,0.1