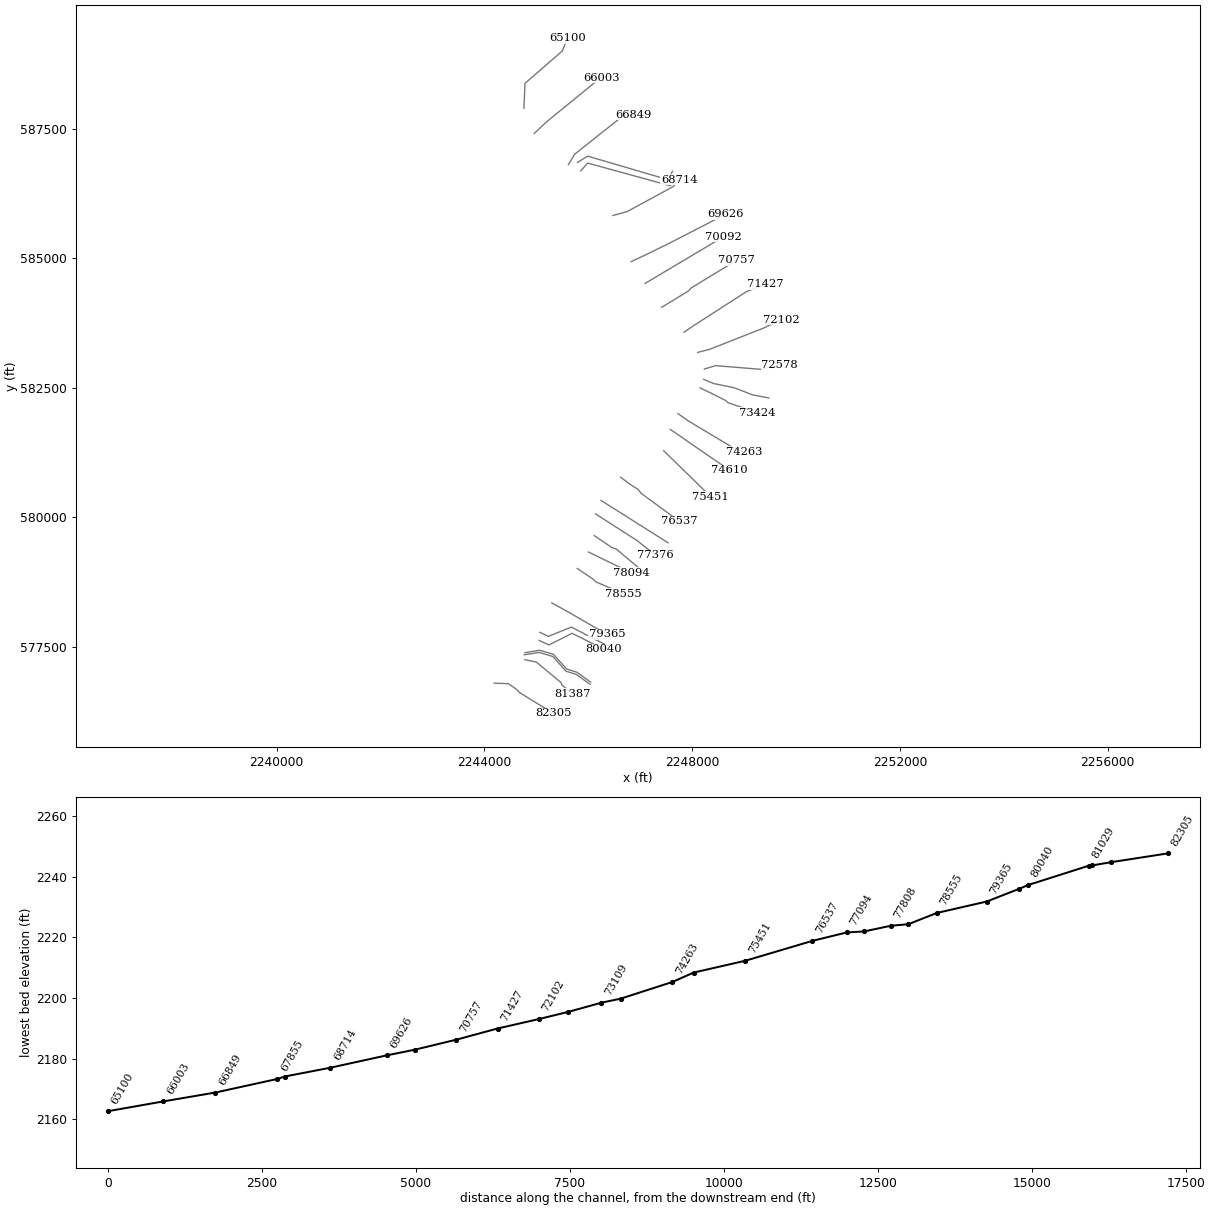
HEC-RAS study TYGVRV2.prj: TYGVRV2

--- TYGVRV2.g01 (geometry) --- (continued)

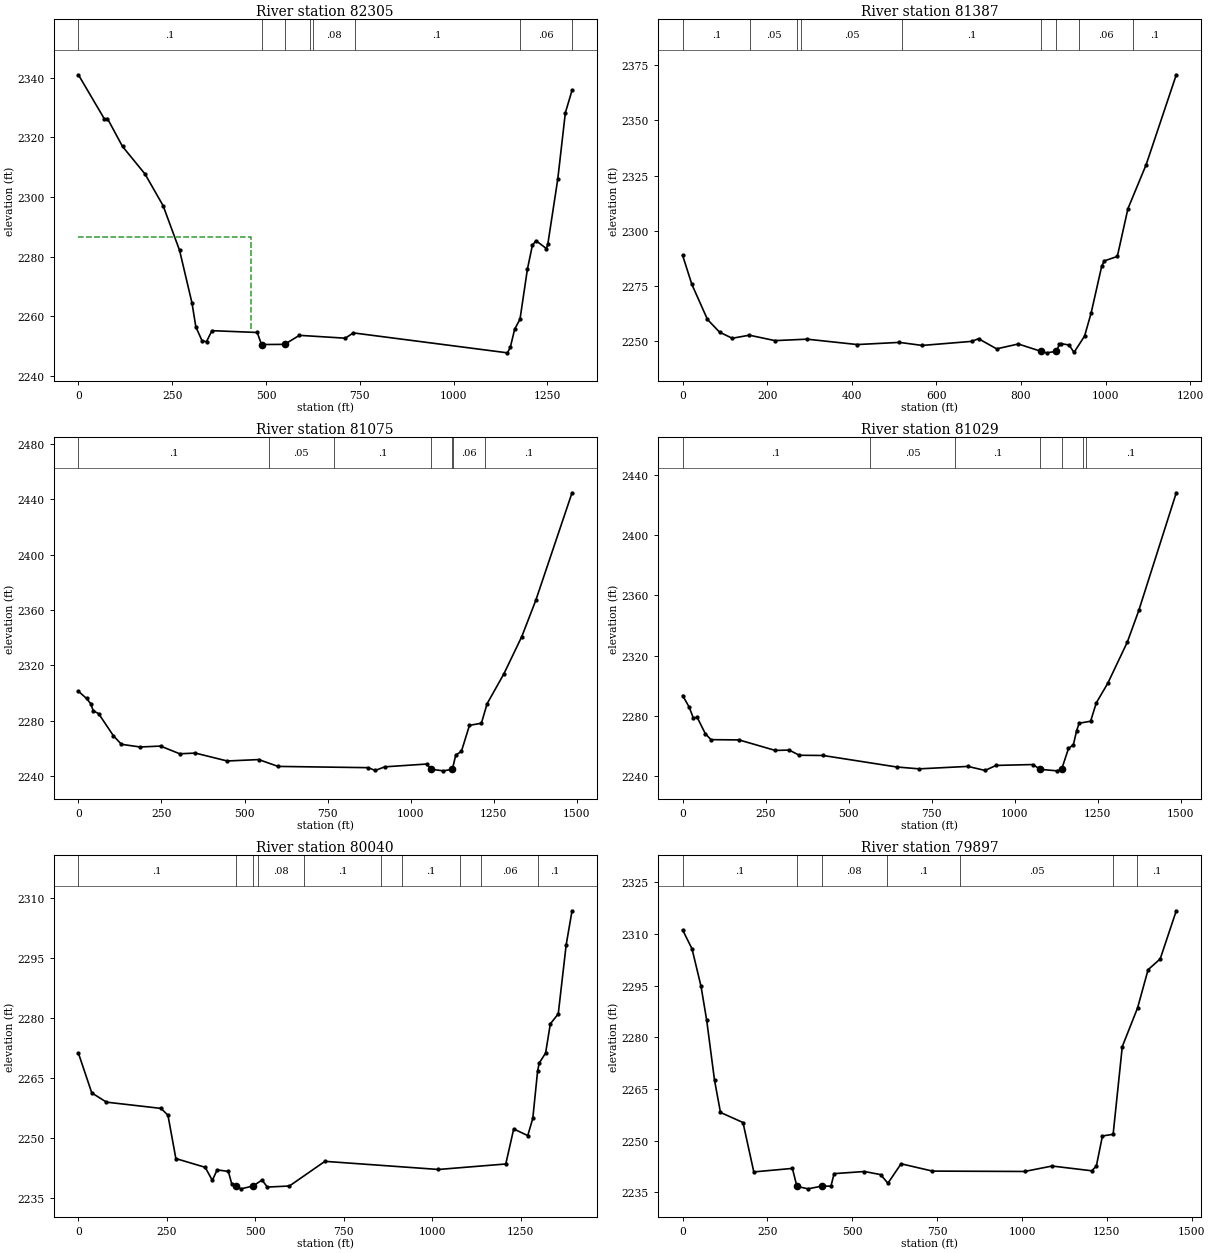
Type RM Length L Ch R = 1 ,82305   ,917.8,917.8,917.8
XS GIS Cut Line= 5
2244186.77867388576801.9040496472244460.08622543576791.634722821
2244634.92717825576670.4287509382244671.98902061576623.159647856
2245326.07262915576218.654350606
#Sta/Elev= 30
       0 2341.07    69.4 2326.19    77.5 2326.34   117.5 2316.99   177.5 2307.73
   225.8 2297.07   269.6 2282.07   302.8 2264.31   312.9 2256.39   329.9 2251.59
   341.4 2251.44   355.8 2255.11   476.5  2254.5     488 2250.45  549.382250.508
   588.9 2253.54   711.1 2252.58   732.6 2254.36  1143.3 2247.66  1150.9 2249.51
  1162.6 2255.66  1176.7 2258.93  1196.5 2275.78  1209.7 2283.75  1219.2 2285.34
  1247.3 2282.67  1251.1 2284.37  1277.3 2305.96  1297.6 2328.31  1315.4 2335.84
#Mann= 8 ,-1,0
       0      .1       0     488    .045       0  549.38     .08       0
  616.31      .1       0  626.31     .08       0  736.31      .1       0
 1176.31     .06       0 1315.37      .1       0
#XS Ineff= 2 , 0
          458.92 2286.55
Permanent Ineff=
       F       F
Bank Sta=488,549.38
XS Rating Curve= 0 ,0
Exp/Cntr=0.3,0.1

Type RM Length L Ch R = 1 ,81387   ,312,312,312
XS GIS Cut Line= 5
2244778.84829513577255.3049205382245002.86223147577206.660614307
 2245472.9631794576815.0384006812245494.03140491576764.390345974
2245704.09090731  576592.9366406
#Sta/Elev= 30
       0 2288.86    21.8 2275.75    58.7 2259.88    87.3 2254.14   117.2 2251.38
   157.6 2252.77   218.3 2250.31     294 2250.97   412.8 2248.53   512.4 2249.51
   566.4 2248.13   683.9 2249.98   699.5 2251.18   742.4 2246.59   793.6 2248.78
   847.4 2245.46   860.3 2244.78  883.822245.465   890.8 2248.68   895.1 2248.93
   913.7 2248.32   925.3 2244.96   950.3 2252.37   965.8 2262.82   990.7 2283.93
   996.8 2286.39  1027.7 2288.42  1052.8 2310.05  1095.9 2329.97  1167.1 2370.65
#Mann= 9 ,-1,0
       0      .1       0     160     .05       0  269.23      .1       0
  279.23     .05       0  519.23      .1       0   847.4    .045       0
  883.82      .1       0  935.94     .06       0 1065.94      .1       0
Bank Sta=847.4,883.82
XS Rating Curve= 0 ,0
Exp/Cntr(USF)=0,0
Exp/Cntr=0.3,0.1

Type RM Length L Ch R = 1 ,81075   ,46,46,46
BEGIN DESCRIPTION:
structure
END DESCRIPTION:
XS GIS Cut Line= 6
2244767.96349278577349.5314620392245056.50573448577394.736820598
2245316.51447237 577316.692148532245573.31409491577031.026410765
2245765.90783894576972.3417770422246035.12457733576779.365867296
#Sta/Elev= 30
       0 2301.19    24.5 2295.99    36.7 2292.29    44.8 2287.07    60.9 2285.01
   105.5 2268.99   129.4 2262.88   185.4 2260.93   247.2 2261.58   304.9 2256.03
   352.1 2256.51     448 2250.81   542.8 2251.83     601 2246.89   872.5 2245.98
   893.4 2243.98   922.6 2246.59  1048.5 2248.61  1061.8 2244.79  1098.9 2243.69
 1125.712244.781    1136 2255.16  1152.9 2257.69  1177.2 2276.58  1213.1 2278.07
  1230.3 2292.19  1280.6 2313.68  1334.7 2340.72  1376.8 2366.87    1486 2444.65
#Mann= 7 ,-1,0
       0      .1       0  574.05     .05       0  768.06      .1       0
  1061.8    .045       0 1125.71      .1       0 1128.67     .06       0
 1224.76      .1       0
Bank Sta=1061.8,1125.71
XS Rating Curve= 0 ,0
Exp/Cntr=0.3,0.1

Type RM Length L Ch R = 1 ,81029   ,989,989,989
BEGIN DESCRIPTION:
structure
END DESCRIPTION:
XS GIS Cut Line= 6
2244780.72148367577391.2075656022245069.26372537577436.412924161
2245329.27246326577358.368252093 2245586.0720858577072.702514328
2245778.66582983577014.0178806052246047.88256822576821.041970859
#Sta/Elev= 30
       0 2293.61    19.7 2285.92    31.8 2278.91      44 2279.05    68.3 2268.28
    85.3 2264.34   169.8 2264.16   278.8 2257.19   320.7 2257.42   351.3 2253.98
   422.5 2253.84   644.3 2246.21   711.9 2244.97   858.7 2246.59   910.5 2243.91
   943.6 2247.25  1054.4 2247.83  1076.4 2244.64  1126.8 2243.65  1140.8 2244.58
  1161.5 2258.49  1176.3 2260.99  1186.1  2270.4  1193.7 2275.24  1228.1 2276.57
  1245.3  2288.8  1279.8 2301.75  1338.7 2329.11  1373.2 2350.07    1486 2428.13
#Mann= 7 ,-1,0
       0      .1       0   563.6     .05       0  819.92      .1       0
  1076.4    .045       0  1140.8      .1       0 1204.76     .06       0
 1214.76      .1       0
Bank Sta=1076.4,1140.8
XS Rating Curve= 0 ,0
Exp/Cntr=0.3,0.1

Type RM Length L Ch R = 1 ,80040   ,142.9,142.9,142.9
XS GIS Cut Line= 5
2245054.62403586577624.8202725782245243.15742892577538.991376145
2245688.06579941577764.0409075822245950.08396324577632.367761799
2246302.86876797577451.282979977
#Sta/Elev= 30
       0 2271.16    37.8 2261.22    79.4 2258.91   233.4 2257.35   253.1 2255.66
   275.5 2244.81   358.4 2242.63   378.6 2239.36   392.1 2241.99   423.9  2241.6
   433.5 2238.47   444.7 2237.96   459.6 2237.25  493.932237.961   519.1 2239.46
     534 2237.69   596.5 2237.96   696.9 2244.12  1017.8 2242.09  1208.2 2243.46
  1230.6 2252.22  1270.3 2250.55  1284.6 2254.88  1298.1 2266.64  1302.6 2268.66
  1320.8 2271.19  1334.1 2278.47  1356.5 2280.96    1379 2298.26  1395.5 2306.73
#Mann= 10 ,-1,0
       0      .1       0   444.7    .045       0  493.93      .1       0
  507.15     .08       0  637.15      .1       0  855.74     .05       0
  915.74      .1       0 1078.98     .05       0 1138.98     .06       0
 1298.98      .1       0
Bank Sta=444.7,493.93
XS Rating Curve= 0 ,0
Exp/Cntr=0.3,0.1

Type RM Length L Ch R = 1 ,79897   ,531.5,531.5,531.5
XS GIS Cut Line= 4
2245067.10585616577782.2054646392245231.89936118577705.256335738
2245674.02008615577883.5773888932246381.62402802577518.720597694
#Sta/Elev= 30
       0 2311.14    27.7 2305.65    54.2 2294.77    70.8 2284.98    93.9 2267.55
   111.5 2258.19   177.8 2255.27   209.7 2240.93   323.4 2241.95  336.682236.751
   369.5 2236.02  410.152236.811   437.1  2236.8   446.3 2240.43   535.8 2241.05
   583.3 2240.15   604.9 2237.64   643.7 2243.29   736.2 2241.17  1007.6 2241.06
  1088.6 2242.64  1205.6 2241.26  1219.1 2242.61  1237.1 2251.36  1268.6 2251.85
  1295.6 2277.31  1340.6 2288.52  1371.7 2299.63  1407.3 2302.74  1454.7 2316.72
#Mann= 7 ,-1,0
       0      .1       0  336.68    .045       0  410.15     .08       0
  601.87      .1       0   818.6     .05       0  1268.6     .06       0
  1338.6      .1       0
Bank Sta=336.68,410.15
XS Rating Curve= 0 ,0
Exp/Cntr(USF)=0,0
Exp/Cntr=0.3,0.1

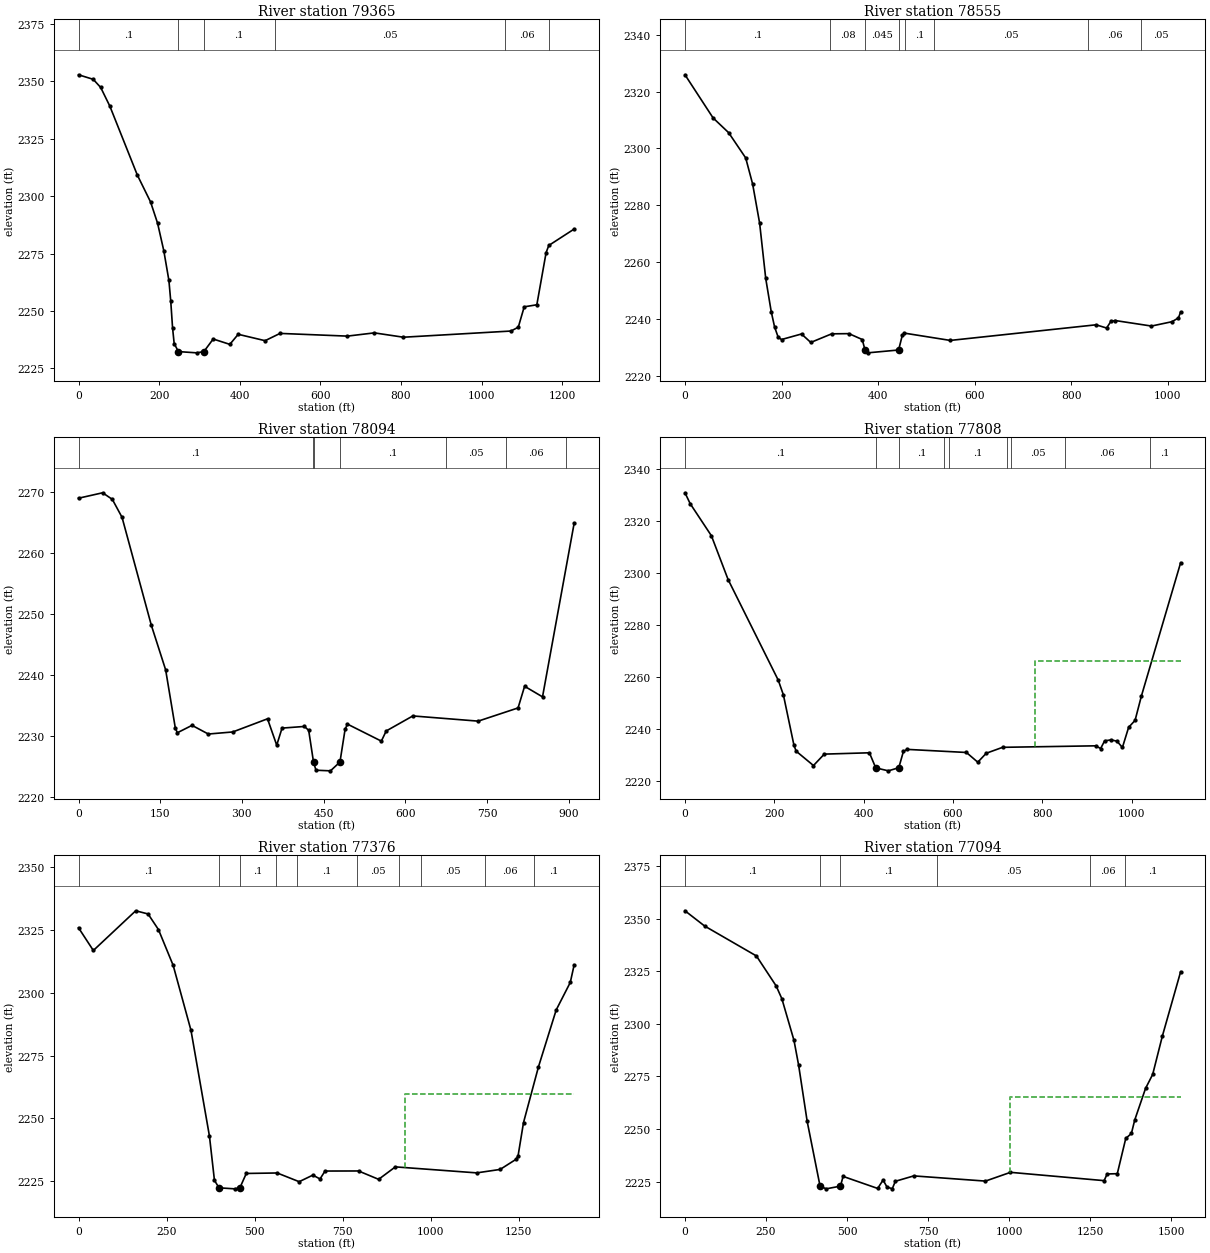
Type RM Length L Ch R = 1 ,79365   ,810.7,810.7,810.7
XS GIS Cut Line= 4
 2245296.2791658578352.0675304322245660.06671842578149.606597518
2245980.34787201577962.0754004822246364.70631952577744.056497753
#Sta/Elev= 30
       0 2352.84    36.5 2350.86      55 2347.32    77.7 2339.19   145.8 2309.22
   178.7 2297.49   196.2 2288.17   211.6 2276.19   224.2 2263.31   228.8 2254.26
   233.3 2242.63   237.3 2235.82  247.842232.343   292.9  2231.8   310.9 2232.34
   334.1 2237.82   375.3 2235.49   396.1 2239.87   462.8 2237.09   499.9 2240.26
   666.8 2239.08   733.8 2240.49   805.9  2238.6  1072.6 2241.29  1090.8 2242.97
  1105.5 2251.83  1136.8 2252.72  1159.8 2275.44  1166.5 2278.55  1229.4 2285.69
#Mann= 6 ,-1,0
       0      .1       0  247.84    .045       0   310.9      .1       0
  486.33     .05       0 1057.48     .06       0 1167.48      .1       0
Bank Sta=247.84,310.9
XS Rating Curve= 0 ,0
Exp/Cntr=0.3,0.1

Type RM Length L Ch R = 1 ,78555   ,460.1,460.1,460.1
XS GIS Cut Line= 5
2245787.81839672579014.3255914162246088.90126398578812.347215533
2246148.65845135578753.735888716  2246240.396207578716.416310175
2246680.30072918578521.701935847
#Sta/Elev= 30
       0 2325.92    58.2 2310.73    90.4 2305.54   125.7 2296.66   140.1 2287.46
   154.6 2273.67   167.2 2254.22   178.6 2242.53   185.6 2237.11   193.1 2233.49
     200 2232.72   241.3 2234.67   260.5 2231.69   303.8 2234.72   339.5 2234.79
   367.1 2232.72   372.8 2229.02   378.4 2228.03  442.382229.028   450.1 2234.25
   454.4 2234.97   549.4  2232.4   851.3  2237.9   873.1 2236.76   881.9 2239.09
   890.6 2239.41     966 2237.46  1008.5 2238.99  1021.9 2240.33  1026.4 2242.44
#Mann= 8 ,-1,0
       0      .1       0     300     .08       0   372.8    .045       0
  442.38     .08       0  456.26      .1       0  516.26     .05       0
   835.3     .06       0   945.3     .05       0
Bank Sta=372.8,442.38
XS Rating Curve= 0 ,0
Exp/Cntr=0.3,0.1

Type RM Length L Ch R = 1 ,78094   ,286.4,286.4,286.4
XS GIS Cut Line= 3
     2246004.389      579332.111     2246413.256      579132.473
     2246822.774      578934.181
#Sta/Elev= 30
       0 2268.93    44.3 2269.82    62.1 2268.74    79.9 2265.81   133.6 2248.18
     160 2240.85   177.8 2231.31   181.5 2230.57   208.4 2231.78   238.3 2230.36
   283.2  2230.7     347 2232.85   363.9 2228.54   373.7 2231.33   414.8  2231.6
   422.6 2230.96   431.5 2225.75     436 2224.44   462.6 2224.34     480 2225.78
   489.4 2231.12   493.8 2231.98     556  2229.2   564.9 2230.86   613.8 2233.32
   733.8 2232.47     807 2234.63     819 2238.17   851.9 2236.44     910 2264.85
#Mann= 7 ,-1,0
       0      .1       0     430     .08       0   431.5    .045       0
     480      .1       0     675     .05       0     785     .06       0
     895      .1       0
Bank Sta=431.5,480
XS Rating Curve= 0 ,0
Exp/Cntr=0.3,0.1

Type RM Length L Ch R = 1 ,77808   ,431.7,431.7,431.7
XS GIS Cut Line= 4
 2246114.5984075579649.7020065852246455.01546015579417.386309588
2246538.70600418579390.6962007252247005.24561052 578998.62560133
#Sta/Elev= 30
       0 2330.73    11.6 2326.56    59.1 2314.22    96.5 2297.38   208.8 2258.67
   220.3 2253.01     244  2233.6   248.9 2231.37   287.6 2225.86   311.8 2230.25
   412.8 2230.76     4272224.957   455.3 2223.82   478.6 2225.03   488.9 2231.28
   497.3 2232.07   629.9 2230.88   655.4 2227.14   674.3 2230.58   710.9 2232.86
   919.4 2233.44   930.3 2232.39   939.3 2235.35   953.5 2235.72   966.9 2235.23
   979.1  2232.8     993 2240.55  1007.4 2243.21  1021.6 2252.59  1109.4 2303.83
#Mann= 9 ,-1,0
       0      .1       0     427    .045       0   478.6      .1       0
  579.98     .08       0  589.98      .1       0  719.98     .06       0
  729.98     .05       0  849.98     .06       0 1039.98      .1       0
#XS Ineff= 2 , 0
                          784.12         2265.93
Permanent Ineff=
       F       F
Bank Sta=427,478.6
XS Rating Curve= 0 ,0
Exp/Cntr=0.3,0.1

Type RM Length L Ch R = 1 ,77376   ,281.9,281.9,281.9
XS GIS Cut Line= 3
2246139.56448678580067.9751945612246941.71458161579552.202911365
2247296.76462358579270.208433583
#Sta/Elev= 30
       0 2325.82    42.1 2316.78   162.4 2332.58   197.5 2331.31     227 2325.09
   268.8 2310.83   319.3    2285   371.7 2242.94   385.9 2225.32  398.892222.356
     443 2221.95  458.112222.351   476.3 2228.07     564 2228.26   626.4 2224.79
   665.3 2227.41   685.6 2225.88   699.8 2229.03   794.9 2229.06     852 2225.73
   899.5 2230.69  1130.5  2228.3  1196.9 2229.67  1242.9 2233.77  1247.9 2235.12
  1263.3 2248.32  1305.8 2270.51  1356.1 2293.13  1396.1 2304.08  1407.1 2311.08
#Mann= 10 ,-1,0
       0      .1       0  398.89    .045       0  458.11      .1       0
     560     .08       0     620      .1       0     790     .05       0
     910     .06       0  973.66     .05       0 1153.66     .06       0
 1293.66      .1       0
#XS Ineff= 2 , 0
                          927.65         2259.52
Permanent Ineff=
       F       F
Bank Sta=398.89,458.11
XS Rating Curve= 0 ,0
Exp/Cntr(USF)=0,0
Exp/Cntr=0.3,0.1

Type RM Length L Ch R = 1 ,77094   ,557.3,557.3,557.3
XS GIS Cut Line= 4
     2246243.396      580328.264     2246628.592      580086.088
 2246775.1456102579992.6281735512247535.69554036579511.062165587
#Sta/Elev= 30
       0 2353.69    60.8 2346.43   220.4 2332.23   281.3 2317.99   298.9 2311.91
   336.3 2292.11   350.6 2280.35     377 2253.62   416.7 2222.92   435.6 2221.62
  479.742222.915   487.7 2227.53   594.4 2221.81   611.1  2225.8   623.4 2222.42
   639.5  2221.7     649 2225.21   705.8 2227.77   926.9  2225.3  1004.1 2229.46
    1293 2225.51  1302.3 2228.68  1333.6 2228.82  1359.7 2245.55  1377.1 2247.92
  1387.5 2254.36  1420.7  2269.3  1442.8 2275.97  1472.7 2294.21    1529 2324.74
#Mann= 6 ,-1,0
       0      .1       0   416.7    .045       0  479.74      .1       0
  778.82     .05       0 1248.82     .06       0 1358.82      .1       0
#XS Ineff= 2 , 0
                         1001.59         2265.14
Permanent Ineff=
       F       F
Bank Sta=416.7,479.74
XS Rating Curve= 0 ,0
Exp/Cntr=0.3,0.1

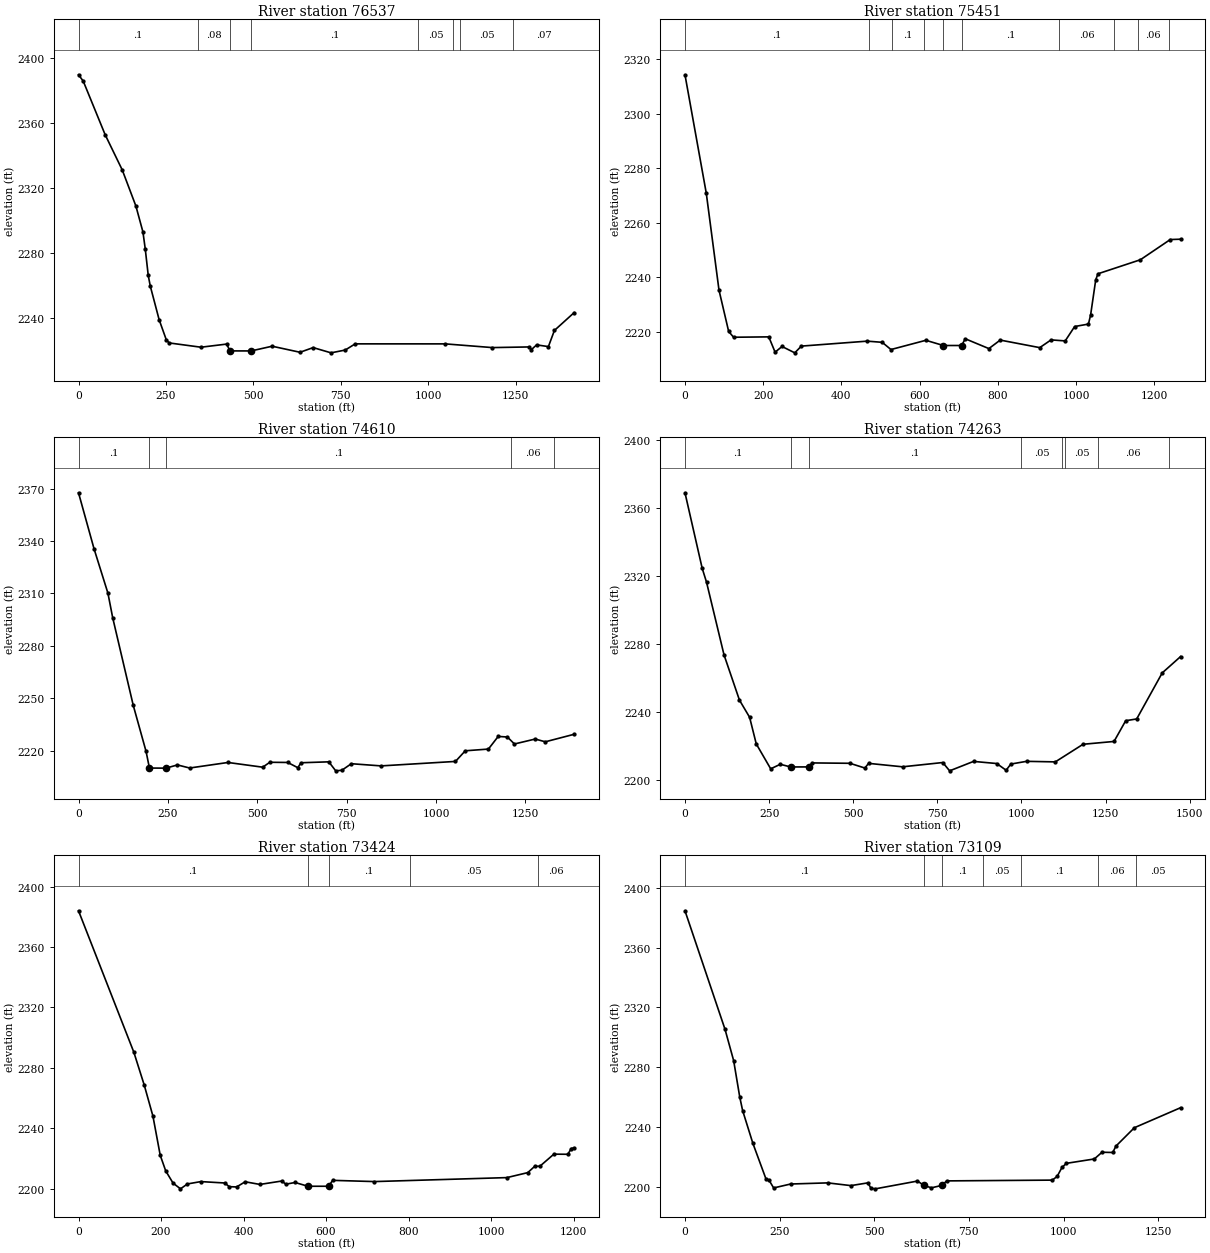
Type RM Length L Ch R = 1 ,76537   ,1086.7,1086.7,1086.7
XS GIS Cut Line= 5
2246623.07352839580774.9377260442246824.28951393580625.539293734
2246963.14021455 580537.413572132247013.96168472580467.823770479
2247751.56484925579925.662121336
#Sta/Elev= 30
       0 2389.86    13.5 2385.97    76.1 2353.02     125 2331.34     164 2309.15
   184.1 2293.24   190.7 2282.85   199.3 2266.49     205 2260.03   230.5 2239.19
   250.6 2227.05   258.8 2224.95     350 2222.31   423.6 2224.24 432.7782220.043
   493.3 2220.02   553.4 2222.92   633.1  2219.2   670.7 2222.07   721.8 2218.85
   762.4 2220.57   790.8 2224.37  1048.3 2224.36  1182.8 2222.08  1288.3 2222.48
  1294.4 2220.82  1309.4 2223.74  1343.1 2222.69  1360.2 2232.62  1416.7  2243.6
#Mann= 8 ,-1,0
       0      .1       0  340.61     .08       0 432.778    .045       0
   493.3      .1       0  971.24     .05       0 1071.24      .1       0
 1091.24     .05       0 1241.24     .07       0
Bank Sta=432.778,493.3
XS Rating Curve= 0 ,0
Exp/Cntr=0.3,0.1

Type RM Length L Ch R = 1 ,75451   ,841,841,841
XS GIS Cut Line= 4
  2247451.176767581287.2120208372247608.83621246581133.370907042
2248036.14117329580716.3216877482248357.72739078580401.219099711
#Sta/Elev= 30
       0 2314.34    54.5 2270.87      87 2235.32   111.7 2220.17   124.3 2218.03
   214.3 2218.17   230.5 2212.55   248.2 2214.64   280.8 2212.31   297.6 2214.78
     466  2216.6   504.4 2216.17   526.8 2213.52     616 2216.91   660.9    2215
  707.462214.999   716.8 2217.47   777.2 2213.87   806.2 2216.99   907.3 2214.22
   936.2 2217.06   972.4 2216.69   996.6 2221.97  1031.8 2222.86  1037.4 2226.23
  1050.5 2239.13  1056.2 2241.32  1164.6 2246.46  1241.1 2253.88  1267.6 2254.01
#Mann= 10 ,-1,0
       0      .1       0  470.28     .07       0  530.28      .1       0
  610.28     .07       0   660.9    .045       0  707.46      .1       0
  957.37     .06       0 1097.37     .07       0 1157.37     .06       0
 1237.37      .1       0
Bank Sta=660.9,707.46
XS Rating Curve= 0 ,0
Exp/Cntr=0.3,0.1

Type RM Length L Ch R = 1 ,74610   ,346.8,346.8,346.8
XS GIS Cut Line= 5
2247580.29578779581698.2087162262247725.54516187581598.653030253
2248014.40635952581397.5344607462248468.97558289581085.016970553
2248721.99211853580911.563516834
#Sta/Elev= 30
       0 2367.65    43.5 2335.53    82.3 2310.14    95.6  2296.1   153.1 2245.92
     189 2219.51  198.372209.997  244.472209.943   276.7 2211.78   310.9 2210.02
   418.1 2213.19   515.2 2210.49   535.1  2213.3   585.2  2213.2   613.4  2210.2
   622.4 2213.03   700.1 2213.56   719.5  2208.4   736.7 2208.73   763.2 2212.48
   846.4 2211.23  1054.5 2213.79  1081.9 2219.88  1146.6 2220.87    1174  2228.1
  1199.7 2227.78  1219.4 2223.78  1277.5 2226.61  1305.8 2225.03  1386.5 2229.34
#Mann= 5 ,-1,0
       0      .1       0  198.37    .045       0  244.47      .1       0
 1209.71     .06       0 1329.71      .1       0
Bank Sta=198.37,244.47
XS Rating Curve= 0 ,0
Exp/Cntr=0.3,0.1

Type RM Length L Ch R = 1 ,74263   ,839.1,839.1,839.1
XS GIS Cut Line= 4
2247728.17337789582003.0804358672247914.20550886581869.350524482
2248744.61359401581371.3666174412248998.58184981581264.596796342
#Sta/Elev= 30
       0  2368.9    51.2 2324.42      64 2316.33     116 2273.54   161.9  2246.9
   192.1 2236.79   211.8 2221.14   254.7 2206.48   283.2 2209.14  313.972207.578
  368.782207.597   377.2 2209.95   490.2 2209.73   534.6 2206.94   545.6 2209.69
   646.5 2207.66   766.1 2210.18   786.4 2205.29   857.5 2210.84   926.4 2209.59
   954.3 2205.64   968.3 2209.28    1015 2210.88  1100.5 2210.56  1182.9 2220.92
    1275 2222.58  1309.7 2234.79  1342.3 2235.82  1418.2 2262.91  1472.9 2272.56
#Mann= 8 ,-1,0
       0      .1       0  313.97    .045       0  368.78      .1       0
  999.11     .05       0 1119.11     .06       0 1129.11     .05       0
 1227.39     .06       0 1437.39      .1       0
Bank Sta=313.97,368.78
XS Rating Curve= 0 ,0
Exp/Cntr=0.3,0.1

Type RM Length L Ch R = 1 ,73424   ,314.9,314.9,314.9
XS GIS Cut Line= 5
2248153.47919128582499.120387482 2248354.0009746582403.102332231
2248640.95490824582258.229083721  2248693.863605582212.510739447
2249250.75026104582024.208385712
#Sta/Elev= 30
       0 2383.95   134.2 2290.23   159.4 2268.46   180.4 2247.98   198.1 2222.02
   211.4 2211.69   229.2  2203.6   247.2  2199.8   264.1 2203.04   296.5  2204.6
   354.7 2203.67   365.3 2201.25   383.2 2201.05     404 2204.47   439.8 2202.72
   492.9 2204.98   502.6 2202.88     525    2204  556.192201.513   606.2 2201.51
   616.1 2205.42   717.5 2204.61  1038.4 2207.24  1089.1 2210.54  1105.9  2214.7
  1118.6 2214.79  1152.4 2222.77  1186.2 2222.69  1194.6 2226.51  1201.6 2226.93
#Mann= 5 ,-1,0
       0      .1       0  556.19    .045       0   606.2      .1       0
   803.7     .05       0  1113.7     .06       0
Bank Sta=556.19,606.2
XS Rating Curve= 0 ,0
Exp/Cntr=0.3,0.1

Type RM Length L Ch R = 1 ,73109   ,530.3,530.3,530.3
XS GIS Cut Line= 5
2248222.43604967582663.3691064182248416.77038855582583.011872232
2248805.62506068 582503.381590252249164.04830081582364.571404954
2249476.25673032582305.784746386
#Sta/Elev= 30
       0  2384.6   105.8 2305.22   128.6 2284.27   144.7 2259.89   152.3 2250.85
   179.3 2228.96   213.8  2205.2   221.9  2204.3   234.2 2199.06   279.1 2201.69
   377.1 2202.45   438.3 2200.62   483.2 2202.46   491.4 2198.79   502.8 2198.46
   614.2 2203.67   631.4 2200.71   651.1 2199.14   678.6 2200.78   691.3 2203.78
   970.3  2204.3   983.1 2206.78   995.8 2212.77  1007.5 2215.53  1081.3 2218.46
  1101.6 2222.95  1130.1  2222.8  1138.2 2227.02  1187.1 2239.38  1309.3 2252.79
#Mann= 7 ,-1,0
       0      .1       0   631.4    .045       0   678.6      .1       0
  787.22     .05       0  887.22      .1       0 1091.58     .06       0
 1191.58     .05       0
Bank Sta=631.4,678.6
XS Rating Curve= 0 ,0
Exp/Cntr=0.3,0.1

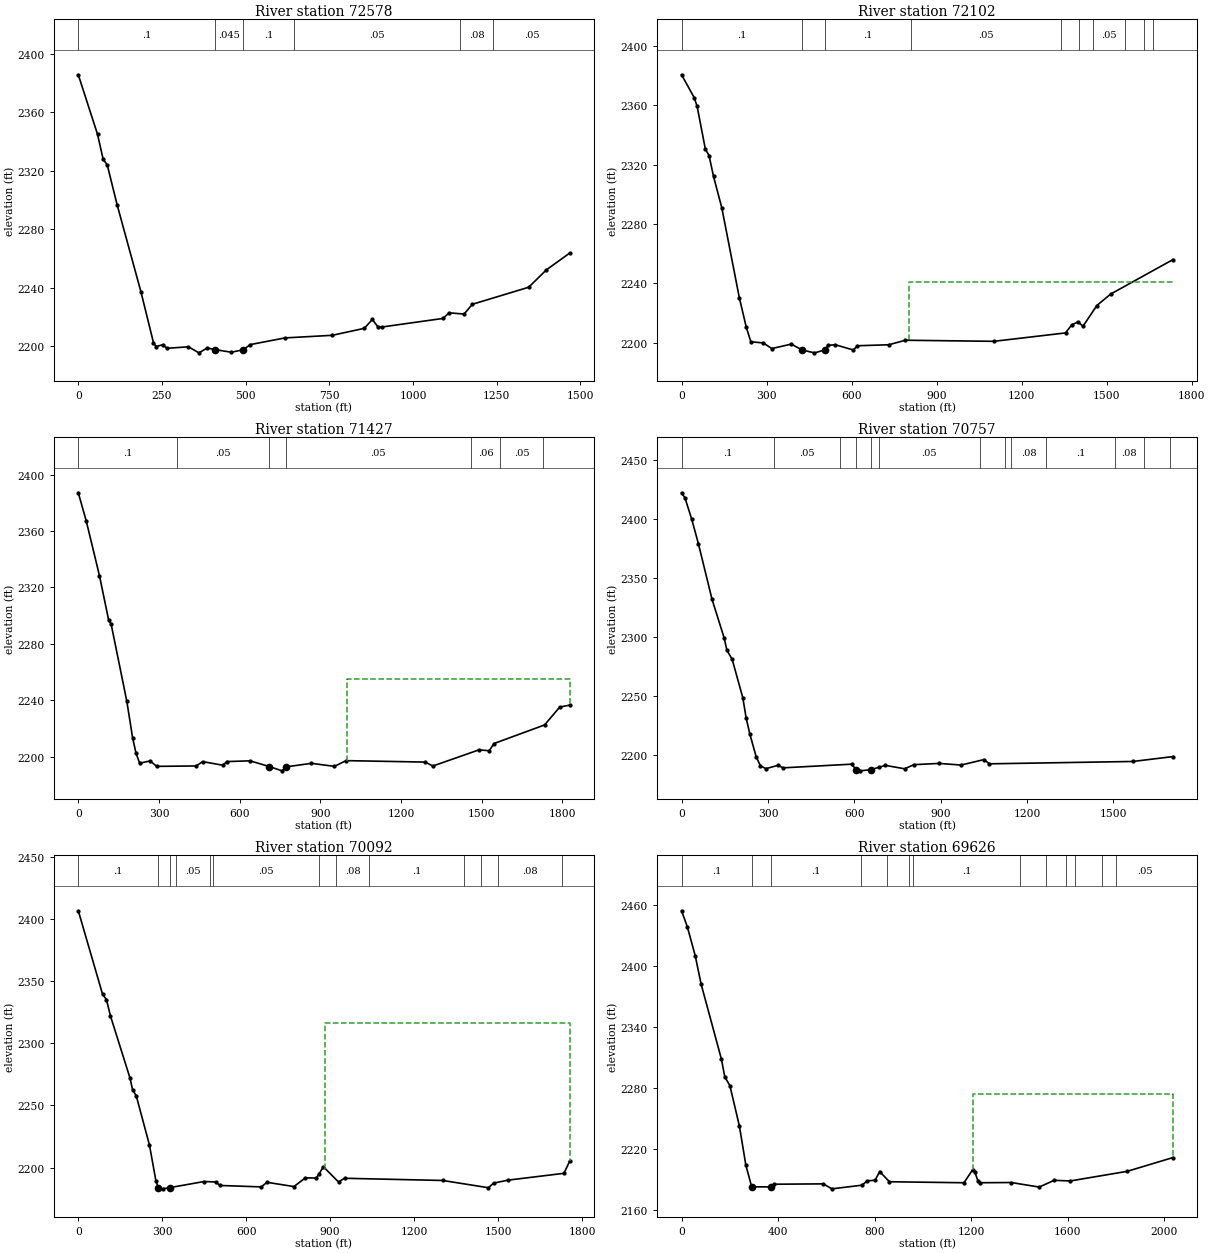
Type RM Length L Ch R = 1 ,72578   ,476.5,476.5,476.5
XS GIS Cut Line= 4
2248237.13047579582864.0761359392248451.64678354582928.680928537
2249324.98775508582857.4147276742249683.46571519582938.992241065
#Sta/Elev= 30
       0 2385.69    57.5 2344.95    74.2 2327.97    86.7 2323.85     116 2296.75
     187 2237.37   224.6 2202.46   232.6 2199.72   252.7  2201.1   264.7 2198.58
   328.9 2199.59   360.6 2195.47   385.1 2198.77   408.7 2197.69   457.3 2195.87
   493.5 2197.63   513.5  2201.1   617.9 2205.69   758.4 2207.45   854.7 2212.24
   878.7 2218.31   894.8 2213.35   906.4 2213.12  1090.4 2219.03  1107.6 2222.85
  1152.8    2222  1177.4 2228.69  1345.6 2240.33  1398.9 2252.29  1467.9 2263.65
#Mann= 6 ,-1,0
       0      .1       0   408.7    .045       0   493.5      .1       0
  644.03     .05       0 1140.28     .08       0 1240.28     .05       0
Bank Sta=408.7,493.5
XS Rating Curve= 0 ,0
Exp/Cntr=0.3,0.1

Type RM Length L Ch R = 1 ,72102   ,675.1,675.1,675.1
XS GIS Cut Line= 4
2248106.92470689583184.2465109982248339.07387774583244.310267347
2249384.06747844583657.1640184632249718.23031794583816.750367612
#Sta/Elev= 30
       0  2380.7    44.5 2365.29      55  2359.3    83.9 2330.56      97 2326.18
   112.8  2312.1   141.8 2291.08   203.7  2230.4   228.3 2210.43   244.4 2200.59
   288.3 2199.78   318.4    2196   387.2 2198.99   425.9 2194.99   468.9 2193.11
   507.6 2195.12   515.7 2198.11     542  2198.6   606.6 2195.01   619.5 2197.89
   731.3 2198.56   790.1 2201.61  1102.2 2200.88  1354.9 2206.55  1376.8 2211.94
    1399 2213.98  1416.7 2211.08  1465.4 2225.02  1514.2 2232.76  1733.7 2255.98
#Mann= 10 ,-1,0
       0      .1       0   425.9    .045       0   507.6      .1       0
  809.79     .05       0 1339.79     .06       0 1403.39     .07       0
 1453.39     .05       0 1563.39      .1       0 1633.39     .05       0
 1663.39      .1       0
#XS Ineff= 2 , 0
                          803.65         2241.13
Permanent Ineff=
       F       F
Bank Sta=425.9,507.6
XS Rating Curve= 0 ,0
Exp/Cntr=0.3,0.1

Type RM Length L Ch R = 1 ,71427   ,670.1,670.1,670.1
XS GIS Cut Line= 4
2247843.41629073583572.744540852 2248031.7357872 583702.26450875
2249049.36488701 584358.694215232249410.28208899   584499.479474
#Sta/Elev= 30
       0 2387.13    29.6 2367.12    78.6 2328.46   112.6  2297.1   122.3 2293.86
   180.5  2239.2   202.2 2213.22   214.5 2202.55   228.1 2195.39   267.2    2197
   291.7 2193.14   438.5 2193.43   462.3  2196.5   537.7 2193.94   552.2 2196.54
     639 2197.06   709.8 2193.03   757.9 2189.97  771.732192.766   866.9 2195.29
   952.6 2193.14   995.4 2197.21    1290 2196.18  1318.7  2193.4  1489.8 2204.84
  1528.4 2204.23  1545.4  2209.3    1734 2222.52  1790.3 2235.19  1826.9 2236.53
#Mann= 7 ,-1,0
       0      .1       0  368.56     .05       0   709.8    .045       0
  771.73     .05       0 1459.54     .06       0 1569.54     .05       0
 1729.54      .1       0
#XS Ineff= 2 , 0
                          999.28         2255.17
Permanent Ineff=
       F       F
Bank Sta=709.8,771.73
XS Rating Curve= 0 ,0
Exp/Cntr=0.3,0.1

Type RM Length L Ch R = 1 ,70757   ,664.9,664.9,664.9
XS GIS Cut Line= 4
2247414.08688436584054.9727378232247924.14424558584365.989430235
2247984.12653637584429.5489441652248856.05343425584961.447063519
#Sta/Elev= 30
       0 2422.22    11.8 2417.87      35 2399.97    58.4 2379.08   105.5 2332.06
   147.7 2299.21   157.4  2288.7   175.8  2280.8   212.7 2248.31   224.3 2231.09
   236.7 2217.85   259.2 2198.12   273.8  2190.6   292.9 2188.14   335.1 2190.97
   352.4 2188.83     591 2191.95  606.582187.202   618.3 2186.29   656.3 2187.21
   684.8 2189.22   707.8 2190.93   774.8 2188.02     807 2191.54   894.1 2192.58
   970.7 2191.21  1050.3 2195.82  1069.1 2192.24  1567.4 2194.24  1706.2 2198.37
#Mann= 13 ,-1,0
       0      .1       0     320     .05       0     550      .1       0
  606.58    .045       0   656.3      .1       0   684.8     .05       0
  1034.8     .07       0  1124.8     .06       0  1144.8     .08       0
  1264.8      .1       0  1504.8     .08       0  1604.8      .1       0
  1694.8     .08       0
Bank Sta=606.58,656.3
XS Rating Curve= 0 ,0
Exp/Cntr=0.3,0.1

Type RM Length L Ch R = 1 ,70092   ,465.8,465.8,465.8
XS GIS Cut Line= 2
2247093.68344457584514.9639267072248601.33828249585414.657507981
#Sta/Elev= 30
       0 2406.44    86.7 2339.41   100.7 2335.12   114.7  2322.1   184.6 2272.19
   193.9 2262.73   207.3 2257.65   254.4 2218.12   277.5 2189.32  285.972183.966
     301 2183.03  326.33 2183.97   449.3  2188.9     492 2188.54   505.2 2185.75
     654 2184.59   674.4 2188.28   770.7 2184.85   811.5 2191.86   850.7 2191.71
     860 2194.78   875.7 2200.82   929.9 2188.57   951.5 2191.52  1302.5 2189.75
  1465.5 2183.93  1484.2 2187.61  1535.4 2190.01  1735.7  2195.5  1755.7 2205.14
#Mann= 13 ,-1,0
       0      .1       0  285.97    .045       0  326.33      .1       0
     350     .05       0     470    .025       0     480     .05       0
     860     .06       0     920     .08       0    1040      .1       0
    1380     .08       0    1440     .07       0    1500     .08       0
    1730      .1       0
#XS Ineff= 2 , 0
                          882.12         2315.95
Permanent Ineff=
       F       F
Bank Sta=285.97,326.33
XS Rating Curve= 0 ,0
Exp/Cntr(USF)=0,0
Exp/Cntr=0.3,0.1

Type RM Length L Ch R = 1 ,69626   ,912.2,912.2,912.2
XS GIS Cut Line= 4
2246826.41225916584937.5183379462247081.71117923585055.339139093
2247574.72330121585297.5069004452248644.90948919585850.303166008
#Sta/Elev= 30
       0 2453.87      24 2438.01    56.5 2409.82    81.2 2381.71   164.9 2308.48
   178.9 2291.08   200.2 2282.29   239.8 2242.41   266.3 2204.23   290.4 2183.13
   371.1 2183.02     382 2185.65     587 2185.99   622.6 2181.12   747.4  2184.7
   768.5 2188.93   801.4 2189.54   820.6 2198.11     861 2188.08  1169.7 2187.09
  1205.8 2199.88  1214.8 2197.52  1228.3 2188.52    1238 2187.11  1365.6 2187.31
  1481.4 2182.86  1543.4 2189.49  1609.1 2188.82  1845.1 2198.25    2035 2211.77
#Mann= 13 ,-1,0
       0      .1       0   290.4    .045       0   371.1      .1       0
  741.17     .05       0  850.45     .07       0  940.45     .08       0
  960.45      .1       0 1400.45     .08       0 1510.45     .06       0
 1590.45     .05       0 1630.45     .06       0 1740.45     .07       0
 1800.45     .05       0
#XS Ineff= 2 , 0
                         1205.78         2273.71
Permanent Ineff=
       F       F
Bank Sta=290.4,371.1
XS Rating Curve= 0 ,0
Exp/Cntr=0.3,0.1

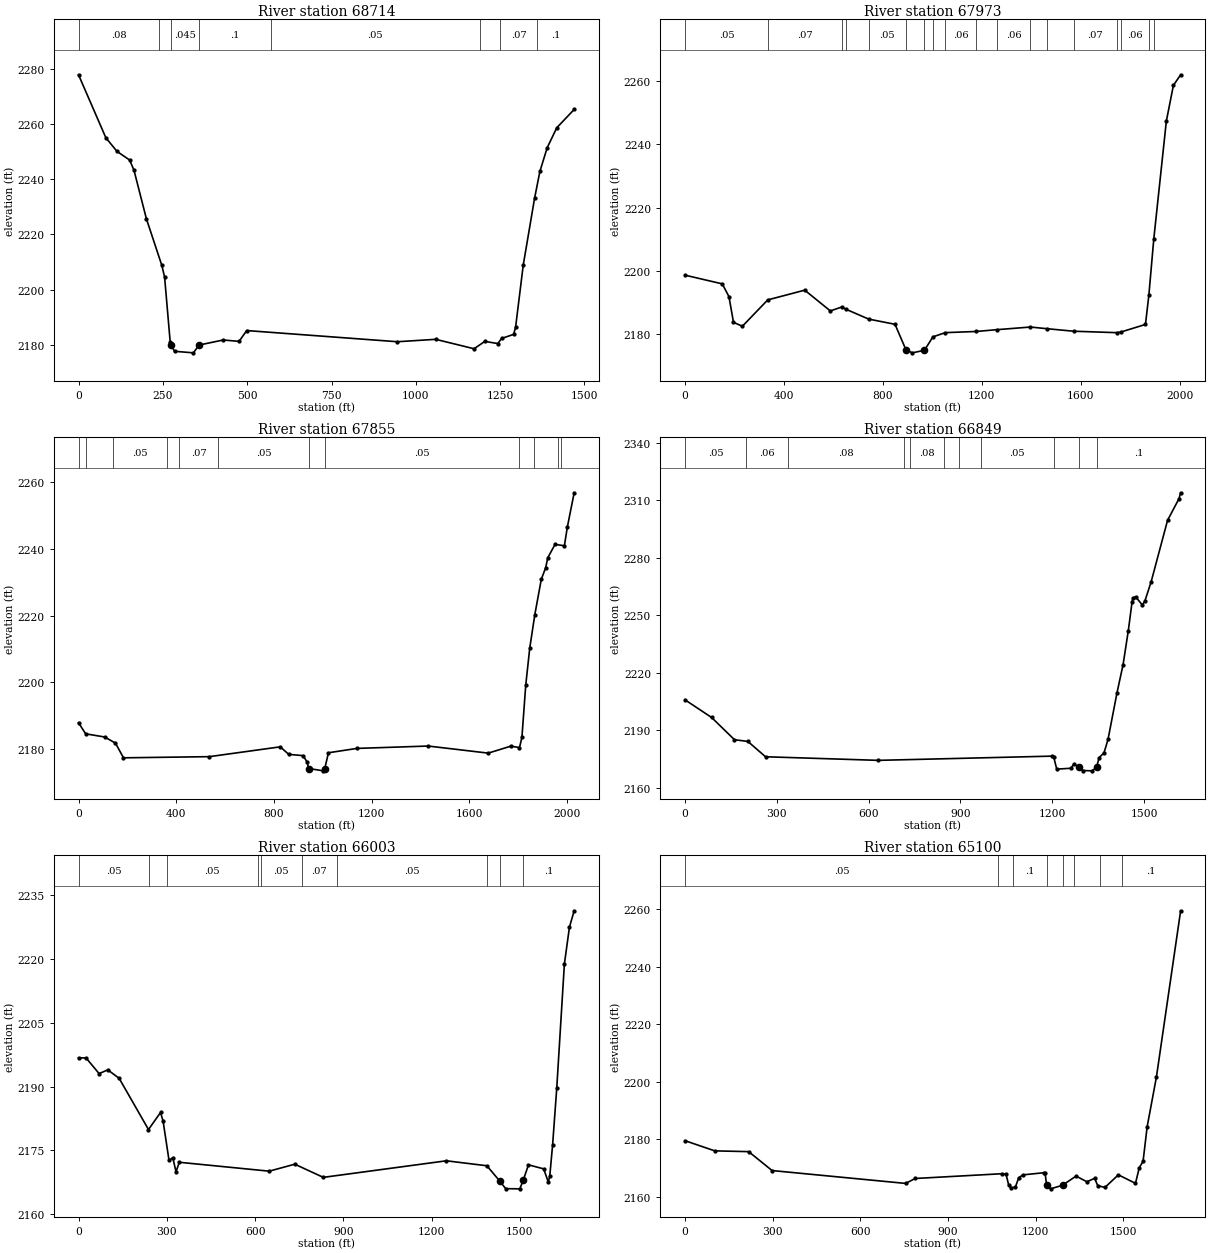
Type RM Length L Ch R = 1 ,68714   ,740.4,740.4,740.4
XS GIS Cut Line= 4
2246473.80756088585826.0703936932246743.74175697585898.866601208
2247631.04239174586381.8840174142247747.65507649586518.401579209
#Sta/Elev= 30
       0 2277.92    81.2 2255.04   114.3 2250.11   151.6 2246.99   164.4 2243.31
   201.3 2225.66   246.9 2208.81   255.2 2204.54   271.7 2181.14  273.88 2179.94
   284.6 2177.62   340.6 2177.06   357.5 2179.89     429 2181.72   475.9 2181.22
   498.7 2185.14     945 2181.09  1058.9 2181.96  1172.7 2178.54  1204.5 2181.21
    1243 2180.43  1254.4 2182.28  1290.1 2183.77  1295.8 2186.42  1318.5 2208.93
    1352  2233.1  1367.8 2242.86  1389.4 2251.46  1417.8  2258.7  1469.4 2265.34
#Mann= 8 ,-1,0
       0     .08       0     240      .1       0  273.88    .045       0
   357.5      .1       0  569.58     .05       0 1189.58     .06       0
 1249.58     .07       0 1359.83      .1       0
Bank Sta=273.88,357.5
XS Rating Curve= 0 ,0
Exp/Cntr=0.3,0.1

Type RM Length L Ch R = 1 ,67973   ,118.7,118.7,118.7
BEGIN DESCRIPTION:
structure
END DESCRIPTION:
XS GIS Cut Line= 4
 2245853.9971569586686.588909935  2245988.648236586837.907379162
2247571.90633229586401.6195875982247684.83970785586514.178103161
#Sta/Elev= 30
       0  2198.7   150.7 2195.95   177.8 2191.92   196.2 2183.79     232 2182.56
   334.8 2190.89   484.2 2193.96   587.9  2187.4   633.6 2188.63   650.2 2187.96
   742.7 2184.82   849.3 2183.18   894.12175.024   919.9 2174.16   968.3 2174.98
  1002.7 2179.21  1052.6 2180.54  1177.1 2180.91  1263.2 2181.49    1397 2182.31
  1463.4 2181.79  1571.3 2180.99  1747.2 2180.53  1764.1 2180.77  1862.1 2183.13
  1875.8 2192.36  1895.6 2210.02  1946.5 2247.35  1975.1 2258.67  2004.3    2262
#Mann= 18 ,-1,0
       0     .05       0   334.8     .07       0   633.6     .05       0
   650.2     .07       0   742.7     .05       0   894.1    .045       0
   968.3     .05       0  1002.7     .07       0  1052.6     .06       0
  1177.1     .05       0  1263.2     .06       0    1397     .07       0
  1463.4     .08       0  1571.3     .07       0  1747.2     .05       0
  1764.1     .06       0  1875.8     .07       0  1895.6      .1       0
Bank Sta=894.1,968.3
XS Rating Curve= 0 ,0
Exp/Cntr=0.3,0.1

Type RM Length L Ch R = 1 ,67855   ,1005.6,1005.6,1005.6
BEGIN DESCRIPTION:
structure
END DESCRIPTION:
XS GIS Cut Line= 4
 2245791.3417134586849.0089516682245989.57857241586971.159631944
2247536.10686039586516.8670323862247622.39312012586680.559202652
#Sta/Elev= 30
       0 2187.82    29.2 2184.48   107.1 2183.53   151.3 2181.69   184.2 2177.27
   535.7 2177.62   826.2 2180.57   860.9 2178.31   919.3 2177.93   935.9 2176.05
  942.522174.061  1002.7 2173.36 1008.362173.988  1023.5 2178.79  1140.2  2180.1
  1432.1 2180.81    1678 2178.68  1770.4 2180.78  1805.9 2180.35  1815.8  2183.4
  1831.6  2199.2    1848 2210.29  1868.7  2220.3  1895.3 2230.94  1912.9 2234.32
  1921.9 2237.41  1951.6  2241.4  1989.8 2240.98  2001.9 2246.62  2029.8  2256.9
#Mann= 12 ,-1,0
       0     .05       0      30     .07       0     140     .05       0
  362.85     .08       0  412.85     .07       0  572.85     .05       0
  942.52    .045       0 1008.36     .05       0 1802.85     .07       0
 1864.72     .05       0 1964.72      .1       0 1974.72     .05       0
Bank Sta=942.52,1008.36
XS Rating Curve= 0 ,0
Exp/Cntr=0.3,0.1

Type RM Length L Ch R = 1 ,66849   ,846,846,846
XS GIS Cut Line= 4
2245616.43858656586806.7292044342245738.58729829587008.479644403
2246615.17410148587706.815333214 2246869.4401043 587773.71028593
#Sta/Elev= 30
       0 2205.96      87 2196.73   161.8 2185.12   205.5 2184.24   263.1 2176.24
   631.7 2174.36  1199.9 2176.57  1204.5 2176.27  1214.7 2169.79  1260.7 2170.23
  1270.9 2172.47  1287.8 2170.76  1299.2 2169.06  1330.5 2168.89  1344.8 2170.82
  1353.3 2175.81  1369.2  2178.3  1382.3 2185.33  1411.7 2209.71  1431.4 2224.25
  1448.6 2242.09    1461 2257.23  1464.1 2259.18  1472.6 2259.73  1494.1 2255.46
  1502.4 2257.35  1523.1  2267.5  1576.8 2299.64  1614.1 2310.88  1619.5 2313.99
#Mann= 11 ,-1,0
       0     .05       0     200     .06       0  335.85     .08       0
  715.85     .05       0  735.85     .08       0  845.85     .05       0
  895.85     .08       0  965.85     .05       0 1205.85      .1       0
  1287.8    .045       0  1344.8      .1       0
Bank Sta=1287.8,1344.8
XS Rating Curve= 0 ,0
Exp/Cntr=0.3,0.1

Type RM Length L Ch R = 1 ,66003   ,903.3,903.3,903.3
XS GIS Cut Line= 4
2244960.19408196587408.8860771532245190.82580376587628.789370503
2246186.16399964588441.9801642812246253.60560793588485.695137943
#Sta/Elev= 30
       0  2196.8    25.7 2196.76      70 2193.08    99.5 2193.96   138.1 2191.97
   237.8 2179.92   278.7 2183.93   287.4  2181.9   307.6 2172.64   320.4 2173.29
   331.3 2169.98   342.6 2172.21     648 2170.12   734.9 2171.76   831.8 2168.66
  1250.2 2172.56  1387.7 2171.39  1430.9 2167.83  1451.6    2166  1499.6 2165.96
  1510.9 2167.93  1529.1 2171.61  1580.7 2170.66  1596.3 2167.57  1601.4 2168.96
  1611.1 2176.35  1625.1 2189.65  1651.1 2218.91  1668.3 2227.55  1684.3  2231.4
#Mann= 10 ,-1,0
       0     .05       0     240     .07       0     300     .05       0
  608.67     .07       0  618.67     .05       0  758.67     .07       0
  878.67     .05       0 1388.67      .1       0  1430.9    .045       0
  1510.9      .1       0
Bank Sta=1430.9,1510.9
XS Rating Curve= 0 ,0
Exp/Cntr=0.3,0.1

Type RM Length L Ch R = 1 ,65100   ,478,478,478
XS GIS Cut Line= 4
2244761.26459292587895.3488944172244781.17034124588376.233699961
2245500.67399434589001.2921368412245597.23170461589244.772655257
#Sta/Elev= 30
       0 2179.47   101.9 2175.93     218 2175.66   298.1 2169.08   755.5  2164.6
   787.5 2166.32  1085.2 2167.98  1098.8 2167.77  1107.9 2164.01  1115.8  2163.1
  1130.6 2163.26  1141.9 2166.52  1156.1 2167.57  1229.8 2168.34  1232.6 2168.13
 1237.262164.184  1251.2 2162.72  1292.2 2163.97  1338.4 2167.16  1375.4 2165.19
  1401.9 2166.36  1412.5 2163.86    1437 2163.19  1483.2 2167.59  1541.8 2164.63
  1554.8  2170.1  1567.7 2172.27  1581.8 2184.36  1613.4 2201.59  1696.3 2259.44
#Mann= 8 ,-1,0
       0     .05       0  1071.3     .08       0  1121.3      .1       0
 1237.26    .045       0  1292.2     .08       0  1331.3      .1       0
  1421.3     .08       0 1494.39      .1       0
Bank Sta=1237.26,1292.2
XS Rating Curve= 0 ,0
Exp/Cntr=0.3,0.1