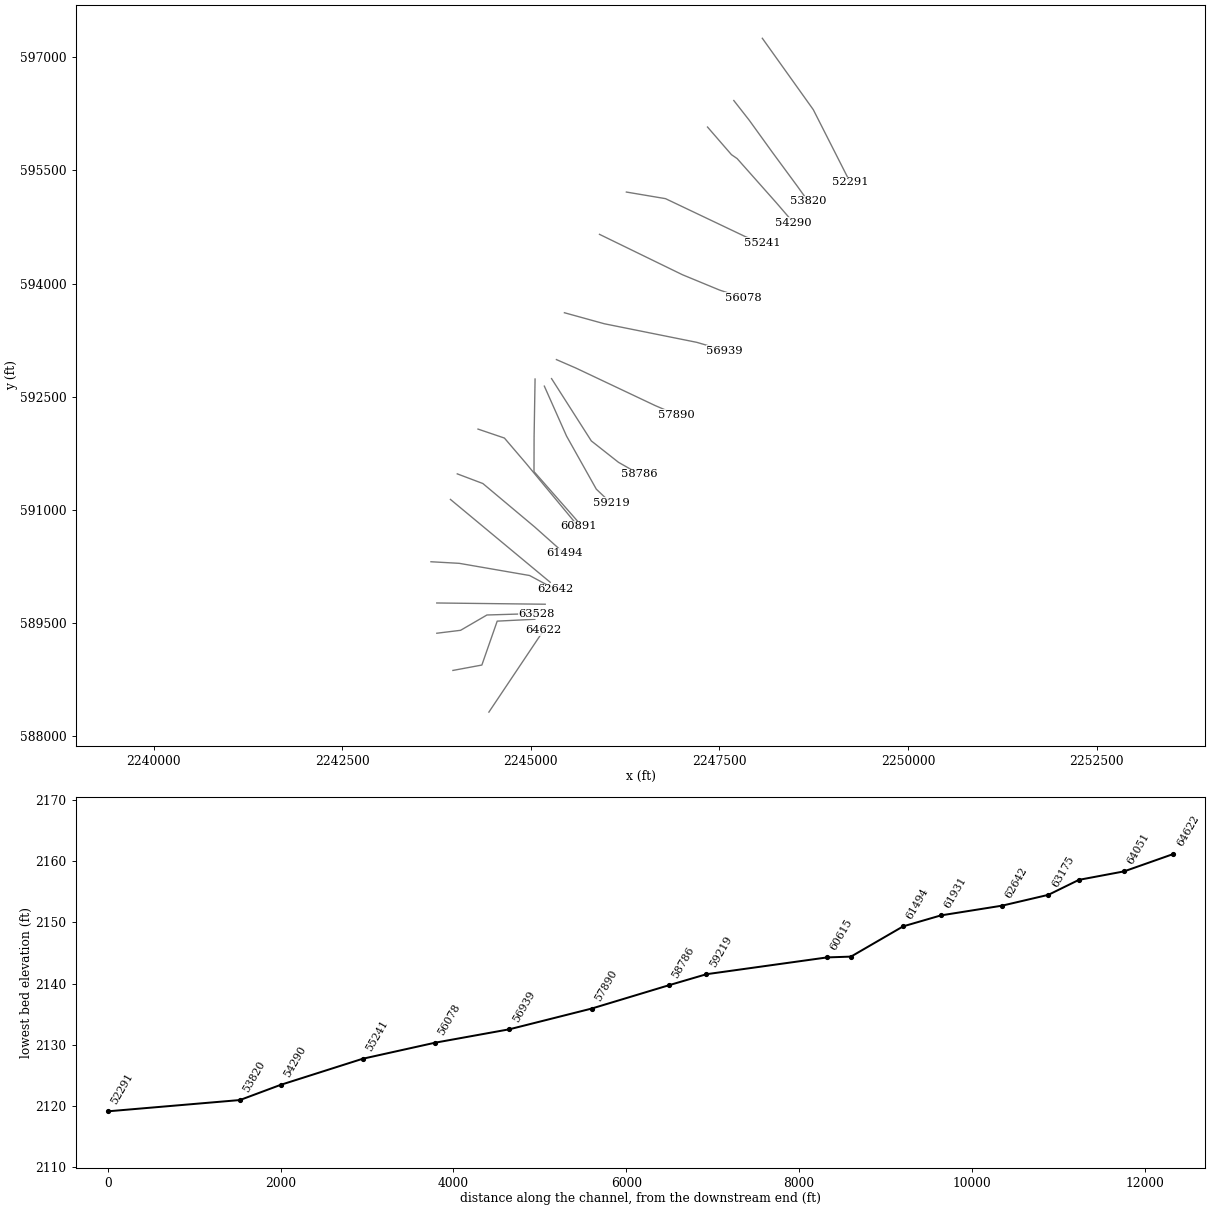
HEC-RAS study TYGVRV2.prj: TYGVRV2

--- TYGVRV2.g01 (geometry) --- (continued)

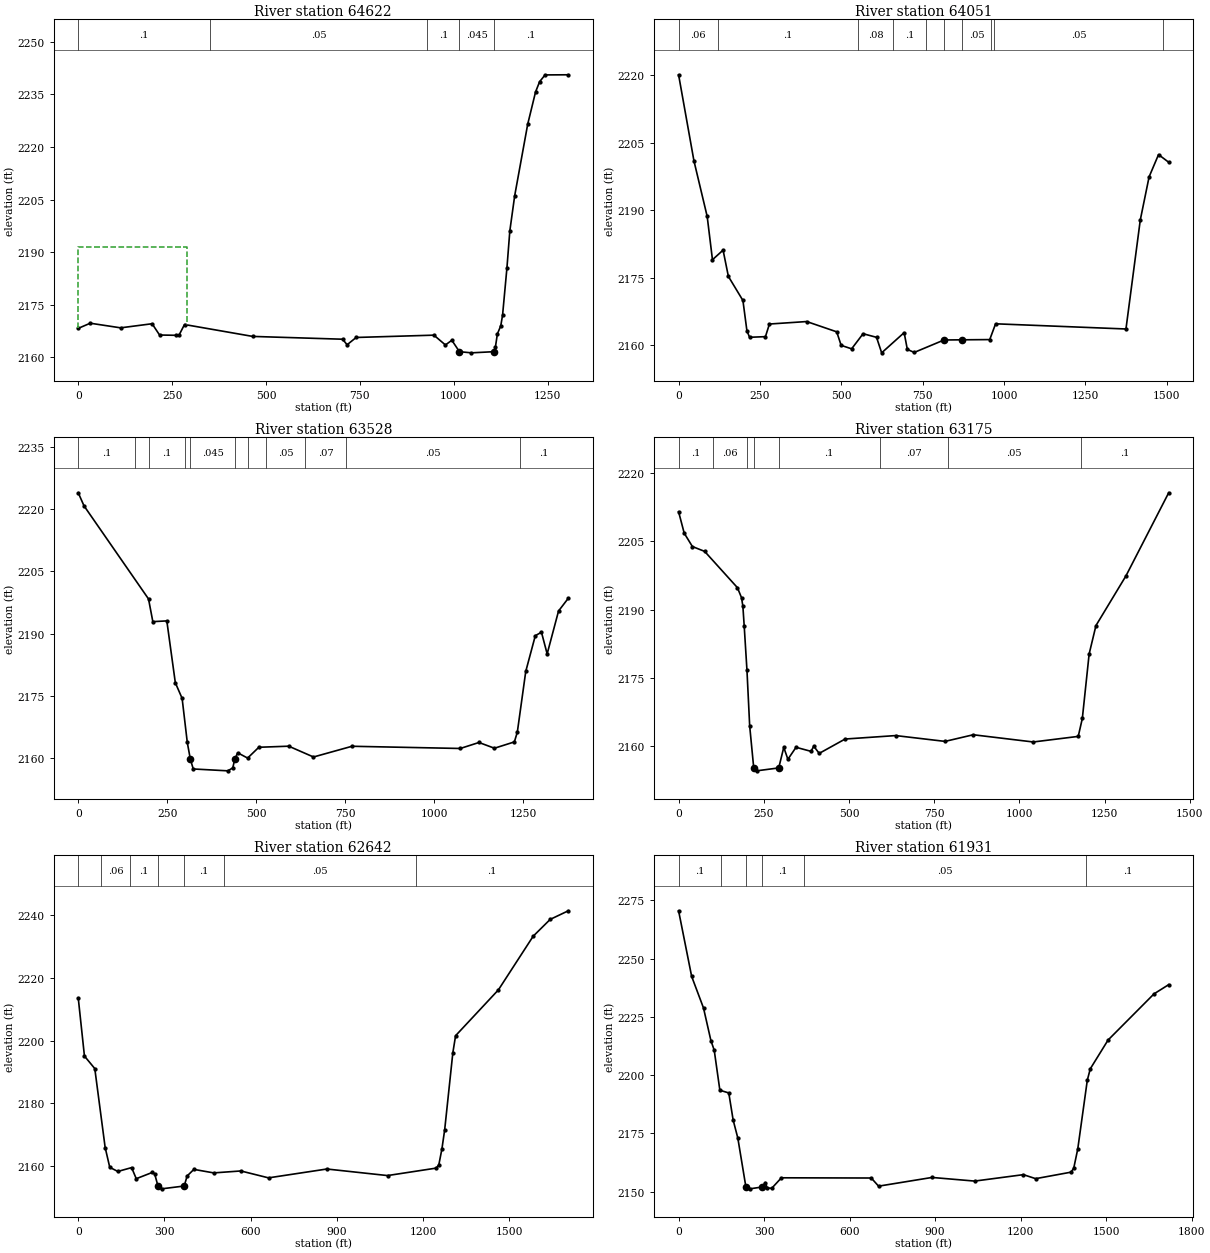
Type RM Length L Ch R = 1 ,64622   ,570.8,570.8,570.8
XS GIS Cut Line= 2
2244442.75142685588318.1432088712245168.74179193589402.674827881
#Sta/Elev= 30
       0 2168.21      32 2169.68   112.8 2168.36   196.7 2169.53   216.6 2166.31
   259.8 2166.23   268.6 2166.32     283 2169.31   464.6 2165.91   703.9 2165.11
     716 2163.53   740.1 2165.61   947.1 2166.27   977.8 2163.47   994.9 2164.81
 1015.112161.551    1047 2161.22 1107.04 2161.55  1110.8 2162.79  1116.2 2166.64
  1125.2 2168.94    1130 2172.01  1141.6 2185.48  1149.3 2196.05  1162.3 2206.12
  1196.9 2226.51  1217.8 2235.72  1228.6 2238.65  1243.1 2240.59  1305.1 2240.63
#Mann= 5 ,-1,0
       0      .1       0     350     .05       0     930      .1       0
 1015.11    .045       0 1107.04      .1       0
#XS Ineff= 2 , 0
           289.1 2191.38
Permanent Ineff=
       F       F
Bank Sta=1015.11,1107.04
XS Rating Curve= 0 ,0
Exp/Cntr(USF)=0,0
Exp/Cntr=0.3,0.1

Type RM Length L Ch R = 1 ,64051   ,523.2,523.2,523.2
XS GIS Cut Line= 4
2243965.79402271588870.6641437832244349.56633685588942.127113167
2244552.96675032589524.2695045572245051.28011924589549.137215864
#Sta/Elev= 30
       0 2220.04    47.2 2200.94    87.9 2188.61   104.1 2179.02   136.7 2181.15
     153 2175.32   197.7 2169.98   209.9 2163.29   218.1 2161.82   266.9 2161.96
   279.1 2164.76   393.6 2165.31   485.9 2163.03   499.5 2160.03   531.7 2159.26
   566.9 2162.61   608.3 2161.81     624 2158.37   693.1 2162.85   702.9 2159.13
   724.1 2158.46   815.6 2161.22   872.1 2161.26   956.1 2161.31   974.1 2164.81
  1374.7 2163.66  1418.7 2187.83  1445.8  2197.4  1474.8 2202.34    1506 2200.64
#Mann= 10 ,-1,0
       0     .06       0     120      .1       0  550.37     .08       0
  660.37      .1       0  760.37     .08       0   815.6    .045       0
   872.1     .05       0  960.37      .1       0  970.37     .05       0
 1487.02      .1       0
Bank Sta=815.6,872.1
XS Rating Curve= 0 ,0
Exp/Cntr=0.3,0.1

Type RM Length L Ch R = 1 ,63528   ,352.7,352.7,352.7
XS GIS Cut Line= 4
2243752.10755715589363.8498822552244067.58752979589402.678615869
2244416.81577883589605.7655334362245071.71863769589625.183130994
#Sta/Elev= 30
       0 2223.87    16.2 2220.73   197.5 2198.33   209.6 2192.87   248.9 2193.05
   272.8 2178.17   291.9 2174.41   306.4 2163.81  314.892159.822   323.2 2157.43
   420.3 2156.98   434.2 2157.69  439.932159.823   448.1 2161.32   475.9 2160.05
   507.4 2162.65   591.5 2162.91     661 2160.31   769.2 2162.89  1073.4 2162.36
  1125.9  2163.8  1169.4 2162.42  1225.4 2163.94  1233.7  2166.3  1257.4 2180.91
  1284.2 2189.49  1301.5 2190.33  1317.5 2185.11  1349.5 2195.43    1377 2198.51
#Mann= 11 ,-1,0
       0      .1       0     160     .06       0     200      .1       0
     300     .07       0  314.89    .045       0  439.93      .1       0
  477.86     .07       0  527.86     .05       0  637.86     .07       0
  751.85     .05       0 1241.85      .1       0
Bank Sta=314.89,439.93
XS Rating Curve= 0 ,0
Exp/Cntr=0.3,0.1

Type RM Length L Ch R = 1 ,63175   ,533.7,533.7,533.7
XS GIS Cut Line= 2
2243751.63187807589764.9509207112245189.53599434589748.454888785
#Sta/Elev= 30
       0 2211.55    16.5 2206.83    40.5 2203.89    76.5 2202.82   172.6 2194.84
   184.6 2192.64   188.6 2190.78   192.6 2186.31   200.6 2176.67   208.6 2164.39
  220.372155.238   228.6 2154.53  293.83 2155.17   308.6  2159.7   320.7 2157.07
   344.6 2159.71   388.6 2158.82   396.6 2159.95   412.6 2158.37   488.6 2161.53
     637 2162.29   781.8 2161.01   864.6 2162.47  1040.6 2160.88  1172.6 2162.11
  1184.6 2166.05  1204.6 2180.25  1224.6  2186.5  1312.6 2197.43    1438 2215.72
#Mann= 8 ,-1,0
       0      .1       0     100     .06       0     200      .1       0
  220.37    .045       0  293.83      .1       0     590     .07       0
     790     .05       0    1180      .1       0
Bank Sta=220.37,293.83
XS Rating Curve= 0 ,0
Exp/Cntr(USF)=0,0
Exp/Cntr=0.3,0.1

Type RM Length L Ch R = 1 ,62642   ,710.2,710.2,710.2
XS GIS Cut Line= 4
2243674.63608863 590311.581515172244050.12077877 590290.52307585
2244982.88474617590128.9944673792245320.15717871589947.458791199
#Sta/Elev= 30
       0 2213.65    21.6 2195.08    57.6 2191.09    93.7 2165.93   109.7 2159.62
   137.8  2158.3   185.8 2159.53   201.9 2155.99     258    2158     266 2157.54
  277.492153.661     290 2152.76  368.882153.662     379 2156.86   402.5 2158.96
   471.5 2157.84   565.9 2158.46   662.3 2156.26   865.3 2159.08  1076.4 2156.99
    1246 2159.37    1255 2160.44  1265.6 2165.41  1275.3 2171.54  1303.7  2196.1
  1313.3 2201.57  1462.3 2216.18  1583.4 2233.29  1642.5 2238.64  1705.7 2241.39
#Mann= 7 ,-1,0
       0      .1       0      80     .06       0     180      .1       0
  277.49    .045       0  368.88      .1       0  506.07     .05       0
 1176.07      .1       0
Bank Sta=277.49,368.88
XS Rating Curve= 0 ,0
Exp/Cntr=0.3,0.1

Type RM Length L Ch R = 1 ,61931   ,437.7,437.7,437.7
XS GIS Cut Line= 2
 2243932.9517996591137.9088096632245255.76859979 590039.57001193
#Sta/Elev= 30
       0 2270.56    45.8 2242.39    87.4 2228.82   113.4  2214.8     125 2210.69
   144.8  2193.5   176.1 2192.34   191.4  2180.7   207.8 2172.96  236.09 2151.99
   249.9 2151.16  293.722151.963   303.9 2153.88   310.9 2151.58   326.6 2151.38
   360.7  2155.9     676 2155.81   701.6 2152.31   889.1 2156.05  1038.8 2154.49
  1209.6 2157.25  1252.7 2155.53  1376.7 2158.32  1386.2 2159.98  1400.4 2168.29
  1433.9 2197.82  1444.3  2202.7  1506.7 2215.05  1667.9 2234.88  1719.4 2238.84
#Mann= 6 ,-1,0
       0      .1       0     150     .06       0  236.09    .045       0
  293.72      .1       0     440     .05       0    1430      .1       0
Bank Sta=236.09,293.72
XS Rating Curve= 0 ,0
Exp/Cntr(USF)=0,0
Exp/Cntr=0.3,0.1

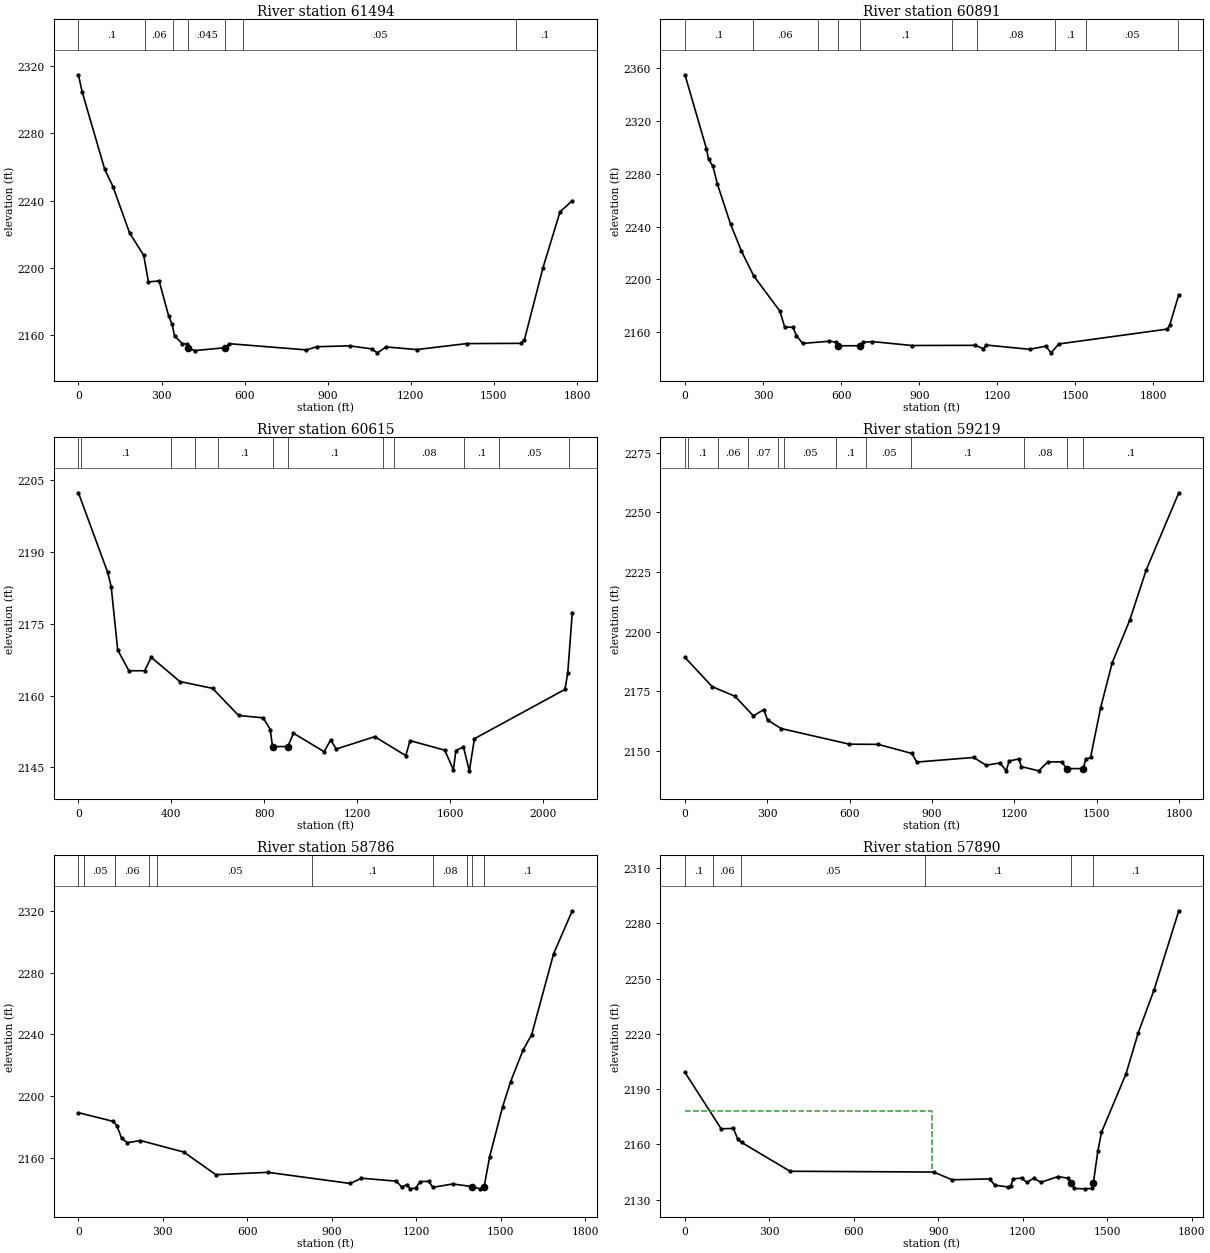
Type RM Length L Ch R = 1 ,61494   ,602.9,602.9,602.9
XS GIS Cut Line= 4
2244023.53324187591476.8080124252244362.93875851591348.648916012
2245051.49291098590771.4945971182245440.97565725 590424.51269964
#Sta/Elev= 30
       0 2314.83    13.5 2304.61    94.8 2258.67   124.7  2248.3   184.5 2220.77
   235.8 2207.33   252.9 2191.56   291.4 2192.15   325.6  2171.4   338.4 2166.24
     347 2159.37   374.8 2154.88   390.5 2154.56  397.02 2152.05   420.1 2150.71
   530.8 2152.42     545  2154.8   822.8 2151.11   860.2    2153   979.4 2153.53
  1058.9 2151.69  1079.5 2149.36  1110.8 2152.87  1221.3 2151.31  1401.4 2154.86
  1597.7 2155.01  1610.4 2157.27    1677 2199.92  1738.9 2233.36  1782.9 2239.84
#Mann= 7 ,-1,0
       0      .1       0     240     .06       0     340     .08       0
  397.02    .045       0   530.8      .1       0   592.8     .05       0
 1581.25      .1       0
Bank Sta=397.02,530.8
XS Rating Curve= 0 ,0
Exp/Cntr=0.3,0.1

Type RM Length L Ch R = 1 ,60891   ,275.4,275.4,275.4
XS GIS Cut Line= 5
2244298.25418365592070.559148088 2244648.6166775591951.533664888
2244932.88296756591618.9606551982245127.11493065591383.985972958
2245628.16749298590779.679527532
#Sta/Elev= 30
       0 2355.07    82.3  2299.2    90.7  2291.1   107.6 2285.71   124.5 2272.35
   175.2 2241.93     217 2221.51   263.9 2202.78   365.2  2175.9   382.7 2164.18
   415.2 2163.68   428.1 2157.52   452.1 2151.55     552 2153.15   581.3 2152.59
  589.192149.774  673.112149.768   683.3 2152.38   720.3 2152.93   872.1 2149.97
    1116 2150.09  1146.4 2147.48  1157.9 2150.31  1323.9 2147.08  1386.2 2149.46
    1407 2144.41  1436.1 2151.13  1853.5  2162.4  1862.3 2165.34  1897.4 2188.42
#Mann= 10 ,-1,0
       0      .1       0     260     .06       0  510.03      .1       0
  589.19    .045       0  673.11      .1       0 1027.54     .07       0
 1122.39     .08       0 1422.39      .1       0 1542.39     .05       0
 1892.39      .1       0
Bank Sta=589.19,673.11
XS Rating Curve= 0 ,0
Exp/Cntr(USF)=0,0
Exp/Cntr=0.3,0.1

Type RM Length L Ch R = 1 ,60615   ,1396.3,1396.3,1396.3
XS GIS Cut Line= 5
2245055.08503561592734.1139880022245042.10639279591966.451491143
2245040.81846099591506.9087005692245087.69361186591453.566259869
2245632.89316965590833.137100326
#Sta/Elev= 30
       0  2202.4   125.7 2185.78     141 2182.76     169 2169.54     217  2165.2
     285  2165.2     313 2168.01   436.5 2162.95     577 2161.52     689 2155.85
   794.9 2155.36     825 2152.92  834.962149.339     901 2149.36     925 2152.14
    1057 2148.28    1085 2150.74    1109 2148.84  1274.8 2151.42  1408.1 2147.46
  1426.5 2150.59  1575.7  2148.6    1613  2144.5  1623.7 2148.52  1656.1  2149.3
  1681.6 2144.28  1703.5    2151  2092.9  2161.3    2105 2164.81  2124.3 2177.33
#Mann= 12 ,-1,0
       0     .05       0      10      .1       0     400     .06       0
     500     .08       0     600      .1       0  834.96    .045       0
     901      .1       0 1308.33     .07       0 1358.33     .08       0
 1658.33      .1       0 1808.33     .05       0 2108.33      .1       0
Bank Sta=834.96,901
XS Rating Curve= 0 ,0
Exp/Cntr=0.3,0.1

Type RM Length L Ch R = 1 ,59219   ,433.1,433.1,433.1
XS GIS Cut Line= 4
 2245177.9544878592639.8242155832245472.40095708591977.685931449
2245867.13067453591273.7917004222246060.74966047591090.127980176
#Sta/Elev= 30
       0 2189.13    99.2 2176.87   182.2 2172.83   249.1 2164.61   287.4 2167.25
   300.6 2162.87     350  2159.3   598.3 2152.73   703.7 2152.63   826.1 2148.84
   844.5 2145.22  1051.3 2147.15  1096.7 2143.89  1147.2 2144.84  1170.1 2141.55
  1180.3 2145.62  1215.6 2146.54  1225.1  2143.3  1288.5 2141.53  1321.3 2145.28
  1371.9 2145.28 1390.332142.473  1450.6 2142.48    1459 2146.32  1477.1 2147.13
    1514  2168.1  1555.8 2186.84  1619.7 2204.73    1680 2225.92  1798.5 2258.25
#Mann= 12 ,-1,0
       0     .05       0      10      .1       0     120     .06       0
     230     .07       0     340     .08       0     360     .05       0
     550      .1       0     660     .05       0  824.66      .1       0
 1234.66     .08       0 1390.33    .045       0  1450.6      .1       0
Bank Sta=1390.33,1450.6
XS Rating Curve= 0 ,0
Exp/Cntr=0.3,0.1

Type RM Length L Ch R = 1 ,58786   ,896.2,896.2,896.2
XS GIS Cut Line= 4
2245273.60523971592739.5714827952245800.78625926591913.534916896
2246161.71869572591629.4006870472246435.41332651591473.982419806
#Sta/Elev= 30
       0 2189.16   123.7 2183.49   136.8 2180.62   153.5 2172.55   173.7 2169.67
   220.4 2171.06   374.4 2163.58   488.1 2148.91   672.7 2150.45   965.3 2143.21
  1005.4 2146.62  1129.2 2144.72  1147.8 2140.99    1168  2142.5  1177.7 2139.75
    1198 2140.25  1213.3 2144.44  1243.9 2144.55  1258.9 2140.72  1329.7 2142.88
  1398.5 2141.19  1426.9 2139.73  1441.2 2141.24  1460.5 2160.58  1506.5  2192.9
  1535.1 2209.32  1579.1 2229.73  1609.8 2239.82  1687.7 2292.24    1754 2320.16
#Mann= 10 ,-1,0
       0      .1       0      20     .05       0     130     .06       0
     250     .07       0     280     .05       0     830      .1       0
 1259.93     .08       0 1379.93      .1       0  1398.5    .045       0
  1441.2      .1       0
Bank Sta=1398.5,1441.2
XS Rating Curve= 0 ,0
Exp/Cntr=0.3,0.1

Type RM Length L Ch R = 1 ,57890   ,950.7,950.7,950.7
XS GIS Cut Line= 4
2245338.22946746592991.7416332212245597.83475775592878.897961346
2246646.34512112592382.7640028752246932.59242326592259.951088588
#Sta/Elev= 30
       0 2199.07   128.6 2168.49   172.2 2168.69     187 2163.05     201  2161.1
   373.2 2145.44   883.1 2145.02   949.4 2140.81  1082.2 2141.29  1100.7 2137.93
  1148.2 2136.88  1156.8 2137.36  1166.2 2141.28  1196.3  2141.8  1214.3 2139.37
  1238.3 2141.58  1265.4 2139.49    1326 2142.59  1361.5 2141.58  1371.9 2139.18
  1383.1 2136.09  1421.6  2135.9    1445 2136.12  1451.1 2139.31  1466.8 2156.27
  1479.8 2166.58  1566.9 2198.25  1610.4 2220.56    1667    2244  1754.5 2286.77
#Mann= 6 ,-1,0
       0      .1       0     100     .06       0     200     .05       0
  853.07      .1       0  1371.9    .045       0  1451.1      .1       0
#XS Ineff= 2 , 0
          879.42 2178.03
Permanent Ineff=
       F       F
Bank Sta=1371.9,1451.1
XS Rating Curve= 0 ,0
Exp/Cntr=0.3,0.1

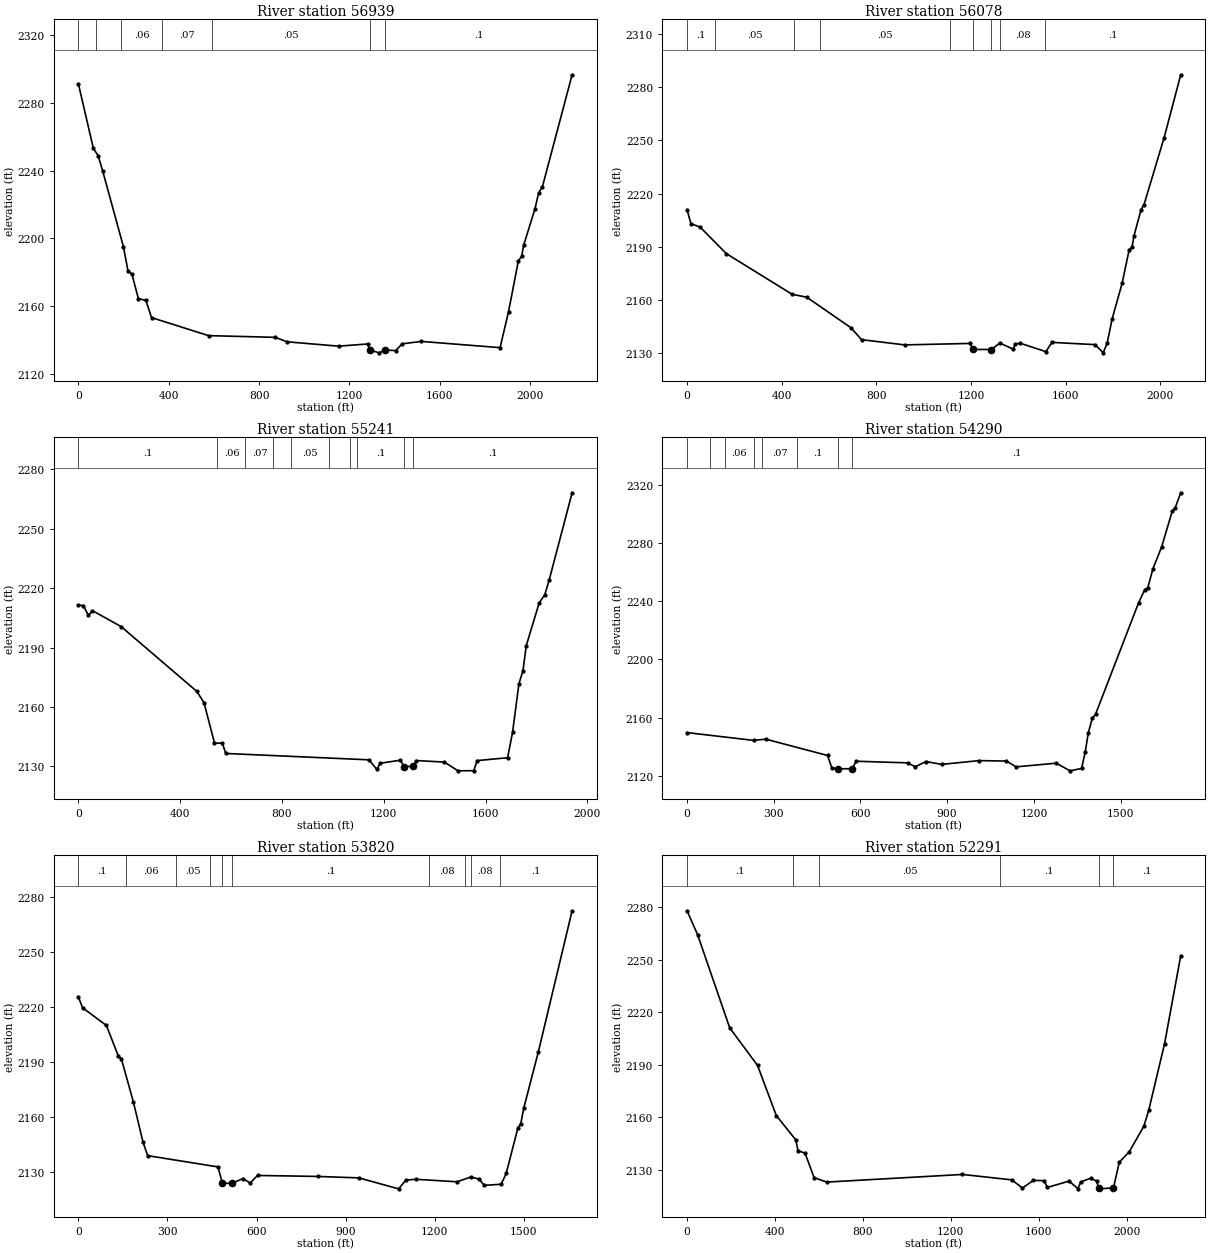
Type RM Length L Ch R = 1 ,56939   ,860.7,860.7,860.7
XS GIS Cut Line= 4
2245444.21772444593612.9689979212245974.48005229593466.636125913
2247198.99080561593220.6052001062247570.26327504593112.159212765
#Sta/Elev= 30
       0 2291.11    66.3 2253.05    87.1  2248.9   107.8 2239.62   199.1 2195.22
   219.9 2180.53   236.5 2179.11   265.5  2164.5   298.7 2163.46   323.6  2153.3
   576.3 2142.66   872.1 2141.65   923.1 2139.03  1151.6 2136.45  1282.1 2137.76
 1288.852134.204  1331.6 2132.51  1359.6 2134.23  1404.5  2133.8  1433.7 2137.85
  1518.8 2139.24    1867 2135.57  1904.5 2156.82  1947.9 2186.76  1962.8 2189.56
  1971.2 2195.92  2021.2 2217.32  2037.8 2226.92  2054.5 2230.52  2185.9 2296.52
#Mann= 7 ,-1,0
       0     .05       0      80      .1       0     190     .06       0
     370     .07       0  590.08     .05       0 1288.85    .045       0
  1359.6      .1       0
Bank Sta=1288.85,1359.6
XS Rating Curve= 0 ,0
Exp/Cntr=0.3,0.1

Type RM Length L Ch R = 1 ,56078   ,837.7,837.7,837.7
XS GIS Cut Line= 4
2245909.17929567594652.3768512832247009.07508438594116.828377586
2247503.65884947593912.6462161232247815.64500885593810.754323734
#Sta/Elev= 30
       0 2210.94    16.4 2203.06    55.5  2201.1   166.2 2186.17   443.8 2163.29
   506.1 2161.63   692.9 2144.43   737.4 2137.74   919.8 2134.78  1196.1 2135.61
 1208.142132.212  1286.7 2132.19  1321.9 2135.86  1378.2 2132.37  1386.8 2135.19
  1408.5  2135.7  1516.6    2131  1542.6  2136.2  1724.7 2134.93    1759 2130.31
  1775.8 2135.88  1796.8 2149.46  1838.9 2169.46  1868.4  2188.2    1881 2189.99
  1889.4 2196.37  1918.9 2210.97  1931.5  2213.8  2016.3 2251.44  2086.6 2286.89
#Mann= 9 ,-1,0
       0      .1       0     120     .05       0     450     .06       0
     560     .05       0    1110      .1       0 1208.14    .045       0
  1286.7      .1       0 1323.35     .08       0 1513.35      .1       0
Bank Sta=1208.14,1286.7
XS Rating Curve= 0 ,0
Exp/Cntr=0.3,0.1

Type RM Length L Ch R = 1 ,55241   ,950.4,950.4,950.4
XS GIS Cut Line= 4
2246265.62539497 595213.09335675 2246784.7497345595125.563299523
2247848.69862131594619.3639671132248069.08281098594537.234075681
#Sta/Elev= 30
       0 2211.42    19.5 2211.21    39.1  2206.2    55.3 2208.62   167.9 2200.57
     465 2167.85   493.4 2162.16   534.7  2141.7   565.7 2141.67     579 2136.46
  1141.5 2133.25  1172.5 2128.45  1185.8 2131.51  1264.7 2133.05  1279.7 2129.87
 1316.572129.906    1328 2132.88  1438.3  2132.1  1491.5 2127.68  1553.5 2127.77
  1566.8 2132.85  1686.4 2134.31    1706 2147.15  1730.9 2171.69  1746.8 2178.29
  1759.6 2190.89  1810.8 2212.65  1832.2 2216.55  1849.3 2223.87  1939.9 2268.19
#Mann= 10 ,-1,0
       0      .1       0  546.45     .06       0  656.45     .07       0
  766.45      .1       0  836.45     .05       0  986.45      .1       0
 1066.45     .05       0 1096.45      .1       0  1279.7    .045       0
 1316.57      .1       0
Bank Sta=1279.7,1316.57
XS Rating Curve= 0 ,0
Exp/Cntr=0.3,0.1

Type RM Length L Ch R = 1 ,54290   ,469.7,469.7,469.7
XS GIS Cut Line= 5
2247341.50142714596075.0044045762247659.36817345595708.403111977
2247734.27230941595656.8582670782248253.68598133595071.281347838
2248481.77235715594806.923151156
#Sta/Elev= 30
       0  2149.7     230 2144.34   272.6 2145.16   486.2 2133.96   500.8 2125.37
  521.972124.843   571.5 2124.82     585 2130.01   762.9 2128.89     790 2126.21
   826.6 2129.82   880.4 2127.84  1010.8 2130.43  1105.1 2130.12  1138.3 2126.15
  1277.1 2128.66  1325.3  2123.4    1365 2125.07  1377.5 2136.31  1388.1 2149.35
  1401.8  2159.5  1413.2 2162.27  1562.4 2239.04  1583.6 2248.05  1594.1 2249.36
  1611.7 2262.26  1641.7 2277.28  1678.6 2301.91  1689.2 2304.47    1708 2314.61
#Mann= 8 ,-1,0
       0      .1       0      80     .05       0     130     .06       0
     230     .08       0     260     .07       0     380      .1       0
  521.97    .045       0   571.5      .1       0
Bank Sta=521.97,571.5
XS Rating Curve= 0 ,0
Exp/Cntr=0.3,0.1

Type RM Length L Ch R = 1 ,53820   ,1529.2,1529.2,1529.2
XS GIS Cut Line= 5
2247690.04926556596426.5686690512247895.75223084596163.820246055
2248198.87537231595743.3584356492248535.17190877595286.707415458
2248677.03146957595088.734763474
#Sta/Elev= 30
       0 2225.54    13.9 2219.71    94.3 2210.05   133.8 2193.65     145 2191.67
   185.1 2168.35   217.6 2146.35   233.3 2139.03   470.1 2132.88   484.9 2123.94
  516.652123.943   553.9 2126.47   578.6 2124.13   603.2 2128.22   805.4 2127.69
   944.2  2126.9  1078.3 2120.92  1103.1 2125.72  1137.5 2126.12  1275.1 2124.78
  1321.7 2127.38  1349.4 2126.25  1366.6 2122.81  1423.8 2123.43  1440.7 2129.31
  1480.1  2154.2  1489.9 2156.56  1499.8 2164.86    1549 2195.65  1662.7 2272.62
#Mann= 10 ,-1,0
       0      .1       0     160     .06       0     330     .05       0
  443.69      .1       0   484.9    .045       0  516.65      .1       0
 1182.03     .08       0 1302.03      .1       0 1322.03     .08       0
 1419.15      .1       0
Bank Sta=484.9,516.65
XS Rating Curve= 0 ,0
Exp/Cntr=0.3,0.1

Type RM Length L Ch R = 1 ,52291   ,600.4,600.4,600.4
XS GIS Cut Line= 3
2248068.19146448597251.8444179892248744.24360561596304.888201766
2249234.00070331595339.792315335
#Sta/Elev= 30
       0 2277.92    47.8 2264.35     194 2211.09   320.8 2189.55   406.1 2160.91
   494.8 2147.01   504.6 2140.93   536.9 2139.42   578.2 2125.44   635.6 2122.93
  1252.9 2127.29  1477.2  2124.2  1525.8 2119.54  1575.9 2123.92  1625.2 2123.74
  1638.7 2119.85  1737.9  2123.5  1777.7 2119.19  1791.1 2123.02    1836 2125.16
  1862.9 2123.46  1871.9 2119.62  1876.4 2119.07  1939.9 2119.62  1966.1 2134.26
  2011.3 2140.17  2078.2 2154.87  2100.3 2164.02  2172.4 2202.05  2245.8 2252.27
#Mann= 6 ,-1,0
       0      .1       0     480     .06       0     600     .05       0
 1423.52      .1       0  1871.9    .045       0  1939.9      .1       0
Bank Sta=1871.9,1939.9
XS Rating Curve= 0 ,0
Exp/Cntr=0.3,0.1