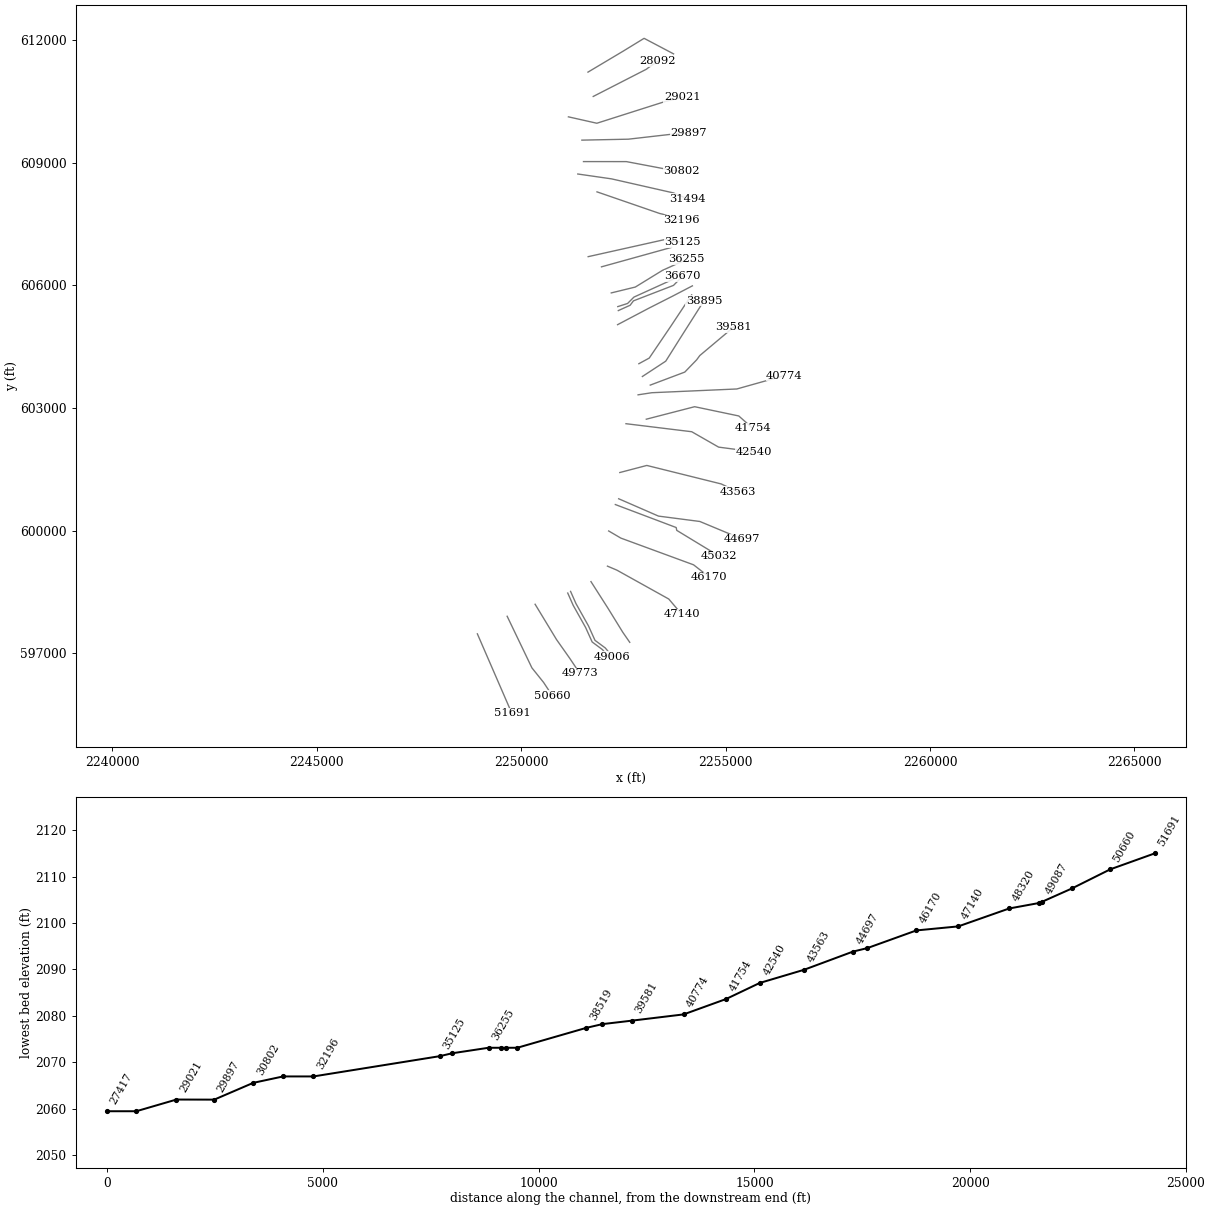
HEC-RAS study TYGVRV2.prj: TYGVRV2

--- TYGVRV2.g01 (geometry) --- (continued)

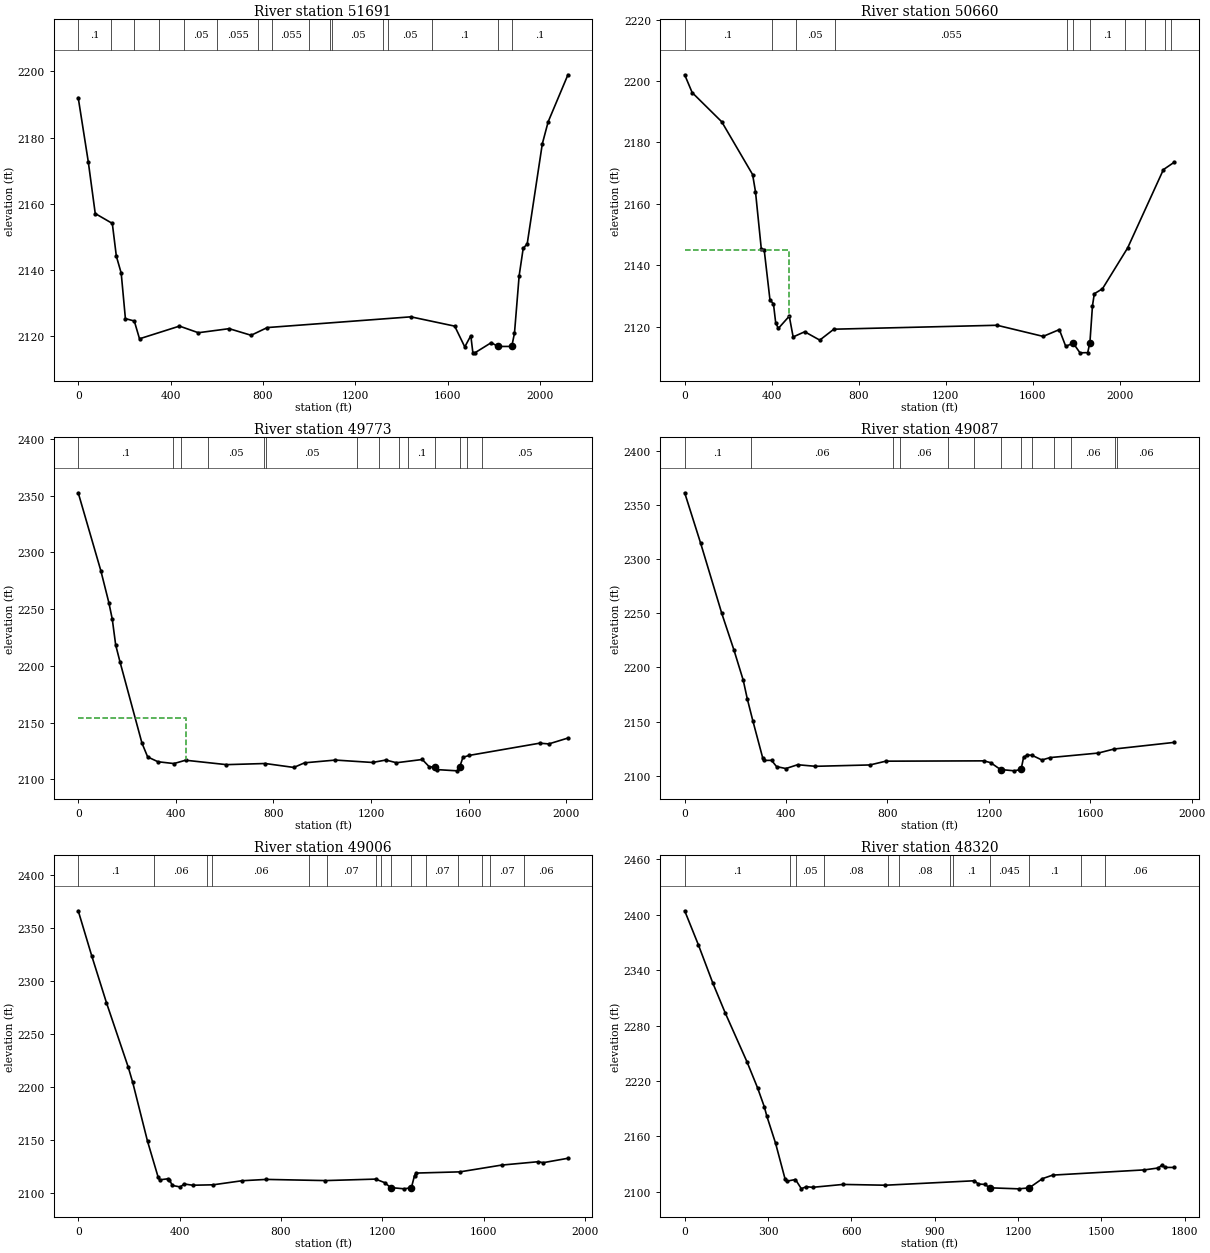
Type RM Length L Ch R = 1 ,51691   ,1030.9,1030.9,1030.9
XS GIS Cut Line= 2
2248926.82320664597476.6244543742249770.91146511595531.487288871
#Sta/Elev= 30
       0 2192.04    43.6 2172.68    73.7 2157.06   147.6 2154.08   165.1 2144.19
   186.1 2139.09   204.3 2125.34   242.8 2124.62   265.4 2119.25   438.5 2123.08
   520.1 2121.08   653.5 2122.31   748.6 2120.31   818.6 2122.64  1440.3 2125.88
  1630.2 2123.07  1673.8 2116.79  1699.9  2120.2  1708.7 2115.11  1717.4 2115.01
  1788.6 2118.09 1816.852116.936 1877.21 2116.94    1889 2120.96  1909.2 2138.29
  1926.7 2146.54  1944.1 2147.92  2009.5 2178.11  2034.9 2184.77  2120.4 2198.95
#Mann= 16 ,-1,0
       0      .1       0     140     .06       0     240     .05       0
     350    .055       0     460     .05       0     600    .055       0
     780     .05       0     840    .055       0    1000     .05       0
    1090    .055       0    1100     .05       0    1320      .1       0
    1340     .05       0    1530      .1       0 1816.85    .045       0
 1877.21      .1       0
Bank Sta=1816.85,1877.21
XS Rating Curve= 0 ,0
Exp/Cntr=0.3,0.1

Type RM Length L Ch R = 1 ,50660   ,887.4,887.4,887.4
XS GIS Cut Line= 4
2249655.67493336597906.6369713642250260.90073929596644.787981246
2250546.09557855  596289.00214432250763.84570195 595958.87909649
#Sta/Elev= 30
       0 2202.02    34.4 2196.23   170.2 2186.74   312.2 2169.57   325.5 2163.97
   352.1  2145.4   365.4 2145.11     392  2128.8   408.1 2127.48   418.2 2121.43
   430.2 2119.49   480.7  2123.5   498.5 2116.74   551.7 2118.43   620.9 2115.71
   685.6 2119.26  1435.7 2120.54  1647.7 2116.92    1722 2119.13  1751.5 2113.68
  1785.7 2114.74    1817 2111.57  1852.4 2111.64  1862.6 2114.93  1874.4  2126.9
  1882.8 2130.79  1920.4 2132.42  2035.9 2145.68  2200.4 2171.17  2250.9 2173.61
#Mann= 11 ,-1,0
       0      .1       0     400     .06       0     510     .05       0
     690    .055       0 1759.49      .1       0  1785.7    .045       0
  1862.6      .1       0 2025.47     .05       0 2115.47      .1       0
 2205.47     .05       0 2235.47      .1       0
#XS Ineff= 2 , 0
          478.34  2145.1
Permanent Ineff=
       F       F
Bank Sta=1785.7,1862.6
XS Rating Curve= 0 ,0
Exp/Cntr=0.3,0.1

Type RM Length L Ch R = 1 ,49773   ,685.2,685.2,685.2
XS GIS Cut Line= 4
2250339.34028498598200.4547301932250864.25735293597334.829502948
  2251182.504167 596883.75409584 2251428.4964009596516.728045339
#Sta/Elev= 30
       0 2352.47    92.7 2283.77   125.5 2255.68   139.5 2241.16   153.5 2218.35
   171.3 2203.36   261.1 2131.93   284.5 2119.71   326.6 2115.47   392.1 2113.86
   439.8  2116.8   607.3 2112.91     766 2113.91   883.3 2110.44   927.3 2114.52
  1053.5 2116.94  1205.8 2114.82  1260.3 2116.98  1303.6 2114.59  1409.6 2117.45
  1438.3 2110.97  1463.2 2110.76  1469.8 2108.54  1553.1 2107.45  1562.6 2110.71
  1576.1 2119.35  1601.2 2121.03  1890.7 2131.83  1927.8 2131.17  2006.2 2136.34
#Mann= 14 ,-1,0
       0      .1       0     390     .06       0     420     .07       0
     530     .05       0     760     .08       0     770     .05       0
 1142.35     .08       0 1232.35     .05       0 1312.35     .08       0
 1352.35      .1       0  1463.2    .045       0  1562.6     .06       0
 1594.39     .07       0 1654.39     .05       0
#XS Ineff= 2 , 0
          441.06 2154.34
Permanent Ineff=
       F       F
Bank Sta=1463.2,1562.6
XS Rating Curve= 0 ,0
Exp/Cntr=0.3,0.1

Type RM Length L Ch R = 1 ,49087   ,81.1,81.1,81.1
BEGIN DESCRIPTION:
structure
END DESCRIPTION:
XS GIS Cut Line= 6
2251137.31501389598475.0517523432251270.06812691598175.484424683
2251574.91126011597631.517257285 2251734.6945444597277.855177397
2251986.86217517597090.9049859642252162.61426903596879.843251637
#Sta/Elev= 30
       0 2361.21    63.3 2314.41   146.4 2249.84   194.6 2215.91     231  2188.2
   247.1 2170.88   268.9 2150.75   308.3 2116.08   312.7 2114.22   342.7  2114.3
   362.4 2108.53   399.1 2106.73   445.5 2110.25     516 2108.79   731.1 2110.05
   793.4 2113.53    1180 2113.82  1206.6 2112.18  1245.8 2105.83  1300.9 2104.61
 1324.782105.912  1327.8  2106.9  1336.9 2117.13  1350.7 2119.19  1369.6 2119.03
  1409.1 2114.61  1441.3 2116.84  1631.8 2121.03  1693.3 2124.72  1931.7 2130.88
#Mann= 13 ,-1,0
       0      .1       0     260     .06       0  823.08     .07       0
  850.33     .06       0 1037.86     .07       0  1143.1     .12       0
  1245.8    .045       0 1324.78     .06       0 1370.65     .08       0
 1457.25     .07       0 1523.71     .06       0 1697.04     .05       0
 1707.04     .06       0
Bank Sta=1245.8,1324.78
XS Rating Curve= 0 ,0
Exp/Cntr=0.3,0.1

Type RM Length L Ch R = 1 ,49006   ,686.7,686.7,686.7
BEGIN DESCRIPTION:
structure
END DESCRIPTION:
XS GIS Cut Line= 6
 2251206.6668669598515.0624367742251339.41997992598215.495109114
2251644.26311312597671.5279417162251804.04639741597317.865861828
2252056.21402818597130.9156703952252231.96612204596919.853936068
#Sta/Elev= 30
       0 2366.27    53.1 2323.98   111.4 2279.68   197.2 2219.05   214.8 2204.74
   273.3 2149.22   314.8 2115.69   320.9 2112.78   353.3 2113.76   359.3 2112.83
   371.6 2107.51   402.7 2106.07   417.5  2108.9   451.7  2107.7   532.1 2108.11
   646.2 2111.94   741.9 2113.19   975.3 2112.09  1173.1 2113.48  1209.4 2110.09
  1232.2  2105.5  1286.8 2104.31 1314.322105.521  1326.5  2116.7  1332.5 2119.17
  1505.9 2120.31  1669.7 2126.67  1814.5 2129.87  1834.3 2128.96  1931.7  2133.1
#Mann= 15 ,-1,0
       0      .1       0     300     .06       0  507.62     .05       0
  527.62     .06       0  911.42     .08       0  981.31     .07       0
  1173.1     .05       0  1193.1     .06       0  1232.2    .045       0
 1314.32     .06       0 1370.65     .07       0 1497.25     .05       0
 1593.71     .06       0 1622.95     .07       0 1757.04     .06       0
Bank Sta=1232.2,1314.32
XS Rating Curve= 0 ,0
Exp/Cntr=0.3,0.1

Type RM Length L Ch R = 1 ,48320   ,1179.8,1179.8,1179.8
XS GIS Cut Line= 4
2251705.57372279598754.2256239742252122.90434134598100.761924497
2252484.11897519597514.6397572152252654.16503455597269.186721317
#Sta/Elev= 30
       0 2404.23      49 2367.61   101.4 2325.85     146 2293.56   224.3 2240.63
   262.3  2212.5   286.5 2192.05   295.5 2182.02     327 2152.62   361.5 2113.56
   366.7 2111.38   398.7 2113.24   419.7 2103.31   437.9 2105.48   460.3 2104.77
   569.6 2107.91   722.7 2107.07  1042.7 2111.89  1056.8 2108.36  1080.3 2107.93
 1097.762104.249  1202.4 2103.14    1240  2104.2  1287.6 2114.19  1324.6 2118.01
  1654.7 2123.67  1704.1 2125.72  1717.9 2128.94  1728.4 2126.36  1762.4 2126.28
#Mann= 12 ,-1,0
       0      .1       0     380     .06       0     400     .05       0
     500     .08       0     730     .05       0     770     .08       0
  955.36     .05       0  965.36      .1       0 1097.76    .045       0
    1240      .1       0 1425.36     .05       0 1513.85     .06       0
Bank Sta=1097.76,1240
XS Rating Curve= 0 ,0
Exp/Cntr=0.3,0.1

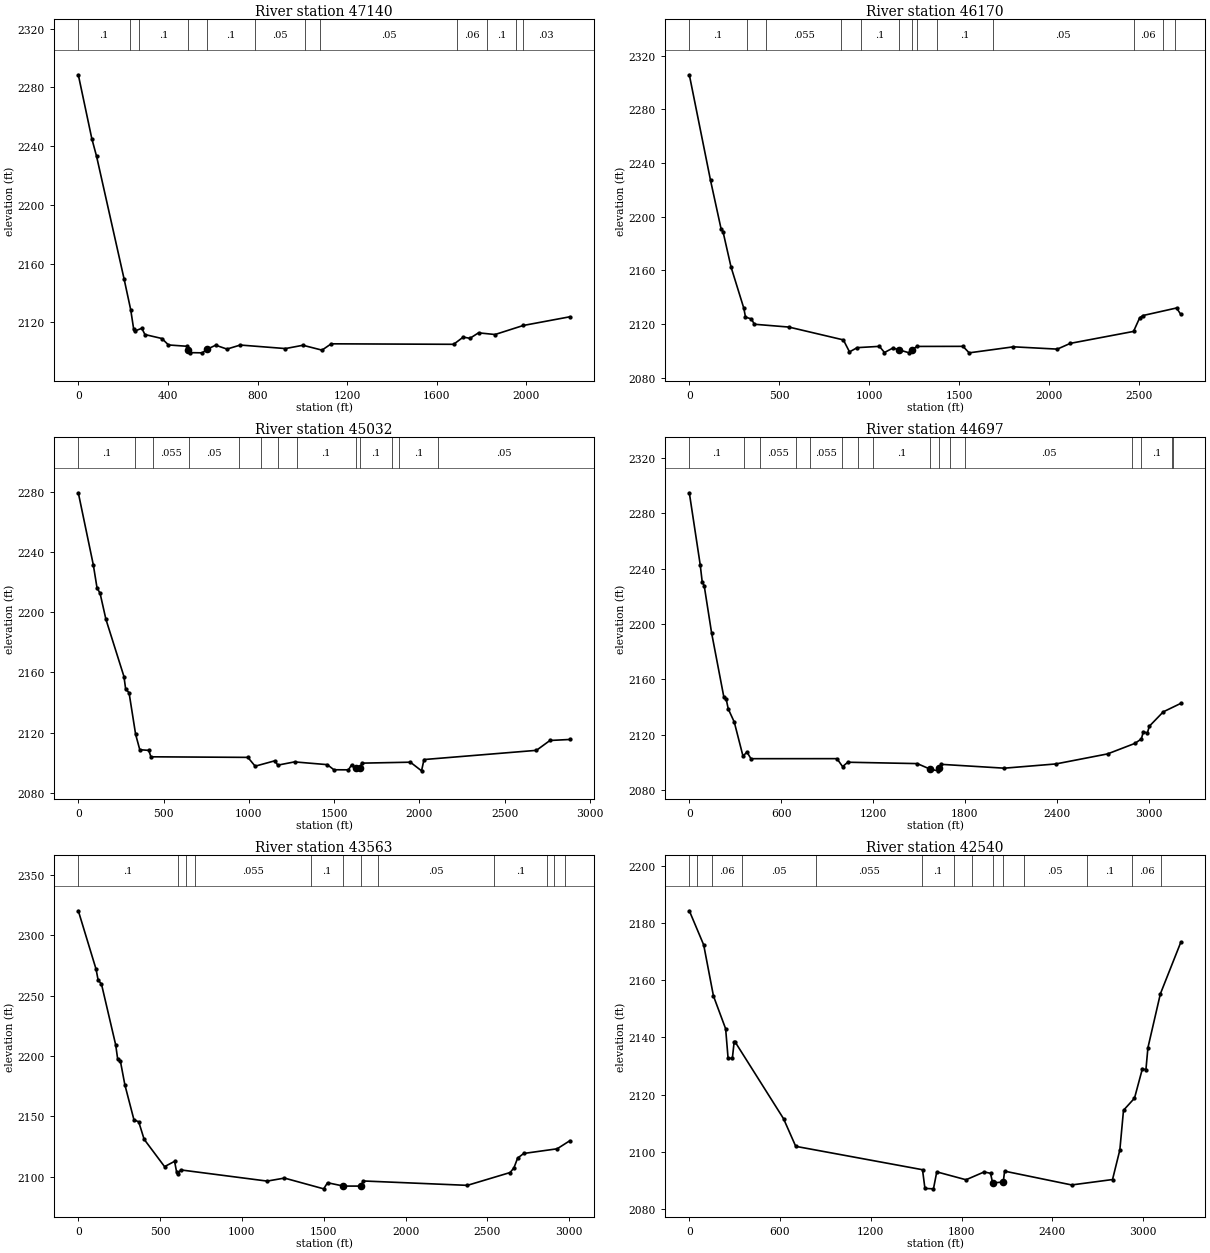
Type RM Length L Ch R = 1 ,47140   ,970.2,970.2,970.2
XS GIS Cut Line= 4
2252108.72981221599132.8457903312252338.63201361599035.351433263
2253608.82775697598328.3281998712253926.53076506597954.803246029
#Sta/Elev= 30
       0 2288.57    60.2 2245.17    81.7 2232.95   204.1 2149.73     234 2128.55
   247.1 2115.44   251.5 2114.08   283.5    2116   297.3 2111.74     373 2109.04
   402.4 2104.65   484.5 2103.76   490.7  2101.3   498.7 2099.41   553.6 2099.28
     573 2101.57   613.1 2104.48   663.5 2101.84     723 2104.59   924.4 2102.19
  1002.6 2104.44  1087.7 2101.12  1128.8 2105.42  1675.2 2105.09  1718.1    2110
  1747.8 2109.16  1786.3  2112.9  1859.9 2111.75  1986.1 2117.91  2193.8 2123.82
#Mann= 12 ,-1,0
       0      .1       0     230     .06       0  269.72      .1       0
   490.7    .045       0     573      .1       0  789.72     .05       0
 1009.72      .1       0 1079.72     .05       0 1689.72     .06       0
 1823.43      .1       0 1953.43     .05       0 1983.43     .03       0
Bank Sta=490.7,573
XS Rating Curve= 0 ,0
Exp/Cntr=0.3,0.1

Type RM Length L Ch R = 1 ,46170   ,1137.8,1137.8,1137.8
XS GIS Cut Line= 4
 2252138.7845025599993.1308900872252436.38322853599818.733897678
2254214.92888921599165.3000704492254602.93368209598863.017544432
#Sta/Elev= 30
       0  2305.7   117.9 2226.97   176.4 2190.92   187.1 2188.86   231.9 2162.38
     303 2131.61   312.2 2125.07   344.7 2123.66   361.8 2119.72   553.5 2117.62
   856.1 2108.06   890.2 2099.11   932.8 2102.28  1056.4 2103.24  1084.6 2098.65
  1131.3 2101.99  1167.2 2100.56  1218.6 2098.56  1237.3  2100.7  1265.2 2103.19
  1520.8 2103.25  1555.2 2098.41  1801.4  2102.9    2045 2101.18  2117.5 2105.48
  2468.7 2114.38  2502.9 2124.53    2520 2126.19  2707.8 2131.85  2731.6    2127
#Mann= 13 ,-1,0
       0      .1       0     320     .06       0  424.93    .055       0
  844.93     .05       0  954.93      .1       0  1167.2    .045       0
  1237.3      .1       0 1264.93     .05       0 1374.93      .1       0
 1684.93     .05       0 2469.72     .06       0 2629.72     .05       0
 2699.72     .06       0
Bank Sta=1167.2,1237.3
XS Rating Curve= 0 ,0
Exp/Cntr=0.3,0.1

Type RM Length L Ch R = 1 ,45032   ,334.3,334.3,334.3
XS GIS Cut Line= 5
2252301.64048881600639.323239582 2253789.8943484600077.332922129
2253803.62689503600007.9731512852254211.50605318 599759.77260421
2254847.78168266599373.737430993
#Sta/Elev= 30
       0 2279.27    88.2  2231.3   109.6 2216.24   127.8 2212.46   161.9 2195.26
   267.8 2157.23   277.8 2148.86   297.7 2146.49   336.2 2118.84   360.6 2108.63
   413.2 2108.19     426 2103.92   994.7 2103.54  1037.4 2097.69  1152.9 2101.27
    1170 2098.38  1268.3 2100.54  1460.7 2098.71  1499.2 2095.31  1584.7 2095.27
  1603.1  2098.6 1626.552096.196 1652.252096.216  1662.2 2099.71  1947.8 2100.34
  2013.4  2094.6  2027.8  2102.1  2687.2 2108.21  2766.7 2114.77  2883.2 2115.43
#Mann= 13 ,-1,0
       0      .1       0     330     .06       0     440    .055       0
     650     .05       0     940    .055       0    1070      .1       0
    1170     .08       0    1280      .1       0 1626.55    .045       0
 1652.25      .1       0 1841.53     .05       0 1881.53      .1       0
 2111.53     .05       0
Bank Sta=1626.55,1652.25
XS Rating Curve= 0 ,0
Exp/Cntr(USF)=0,0
Exp/Cntr=0.3,0.1

Type RM Length L Ch R = 1 ,44697   ,1134.1,1134.1,1134.1
XS GIS Cut Line= 4
 2252383.0147766600781.2215636022253356.94148468600356.857483003
2254368.17722931600225.4833834422255410.20056071599791.239050977
#Sta/Elev= 30
       0 2294.79    71.1 2242.83    84.2 2230.39    97.3  2227.6   145.3 2193.68
   225.8 2147.05   241.2 2145.52   254.3 2138.59   293.6 2129.12   350.6 2104.48
   376.5 2107.42   402.7 2102.62   964.3 2102.65  1001.5  2096.9  1035.3 2100.06
  1489.2 2099.07  1569.8 2095.22  1621.9 2093.84  1631.32095.596  1646.5 2098.53
  2057.9 2095.76  2394.3 2098.82  2732.1 2106.07  2911.3 2113.69  2953.1 2116.91
  2966.1 2122.13  2992.1 2121.15  3005.1 2126.07  3096.1 2136.47    3211 2142.61
#Mann= 16 ,-1,0
       0      .1       0     360     .06       0     460    .055       0
     700     .05       0     790    .055       0    1000     .05       0
 1102.36     .08       0 1202.36      .1       0  1569.8    .045       0
  1631.3      .1       0 1702.36    .025       0 1802.36     .05       0
  2892.1     .06       0  2952.1      .1       0  3152.1     .05       0
  3162.1      .1       0
Bank Sta=1569.8,1631.3
XS Rating Curve= 0 ,0
Exp/Cntr=0.3,0.1

Type RM Length L Ch R = 1 ,43563   ,1023.9,1023.9,1023.9
XS GIS Cut Line= 4
2252411.16721955601422.6315505592253071.57015093601595.884890593
2254890.21674557601143.7699505132255294.28705162600952.713699485
#Sta/Elev= 30
       0 2320.41   108.6 2271.95     121 2263.06   141.6 2259.64   228.5 2209.21
   240.9 2197.19   257.4 2195.63   284.6  2176.1   340.1 2147.11   369.1  2145.5
   402.2 2131.01   527.1 2108.33   588.3 2112.71   600.7 2103.95   608.9 2102.16
   625.5 2105.62  1154.2 2096.34  1259.9 2098.84  1499.5 2089.92    1523 2094.98
  1620.32092.215  1725.3  2092.2  1741.8 2096.44  2377.4 2092.81  2638.6 2103.43
  2662.3 2107.35  2684.5 2115.36  2721.9 2119.24  2926.2 2123.11  3003.7  2129.8
#Mann= 12 ,-1,0
       0      .1       0     610     .06       0     660     .05       0
  712.75    .055       0 1422.75      .1       0  1620.3    .045       0
  1725.3      .1       0 1832.75     .05       0 2542.75      .1       0
 2866.75     .06       0 2906.75      .1       0 2976.75     .06       0
Bank Sta=1620.3,1725.3
XS Rating Curve= 0 ,0
Exp/Cntr=0.3,0.1

Type RM Length L Ch R = 1 ,42540   ,785.1,785.1,785.1
XS GIS Cut Line= 4
2252561.73441847602616.9193076692254170.54405436602420.560590664
2254827.74725725602044.0855089412255691.98874801601929.738659104
#Sta/Elev= 30
       0 2184.25    95.1 2172.32   159.6 2154.48   240.2 2143.01   256.3 2132.73
   284.5 2132.68   296.6 2138.51   304.7 2138.26     623  2111.6   703.6 2101.94
  1541.8 2093.77  1557.9 2087.23  1614.3 2087.09  1636.1 2093.02  1829.6 2090.26
  1949.7    2093  1991.4 2092.51  2005.8 2089.14  2075.8 2089.49  2084.6 2093.27
  2527.9 2088.45  2798.2 2090.34  2846.6 2100.68  2870.8 2114.54  2943.5 2118.77
  2995.9  2129.1    3019 2128.67  3032.2 2136.38  3114.6 2155.23  3249.9 2173.28
#Mann= 14 ,-1,0
       0     .05       0      50      .1       0     150     .06       0
     350     .05       0     840    .055       0    1540      .1       0
 1750.75     .05       0 1870.75      .1       0  2005.8    .045       0
  2075.8      .1       0 2210.75     .05       0 2628.14      .1       0
 2928.14     .06       0 3118.14      .1       0
Bank Sta=2005.8,2075.8
XS Rating Curve= 0 ,0
Exp/Cntr=0.3,0.1

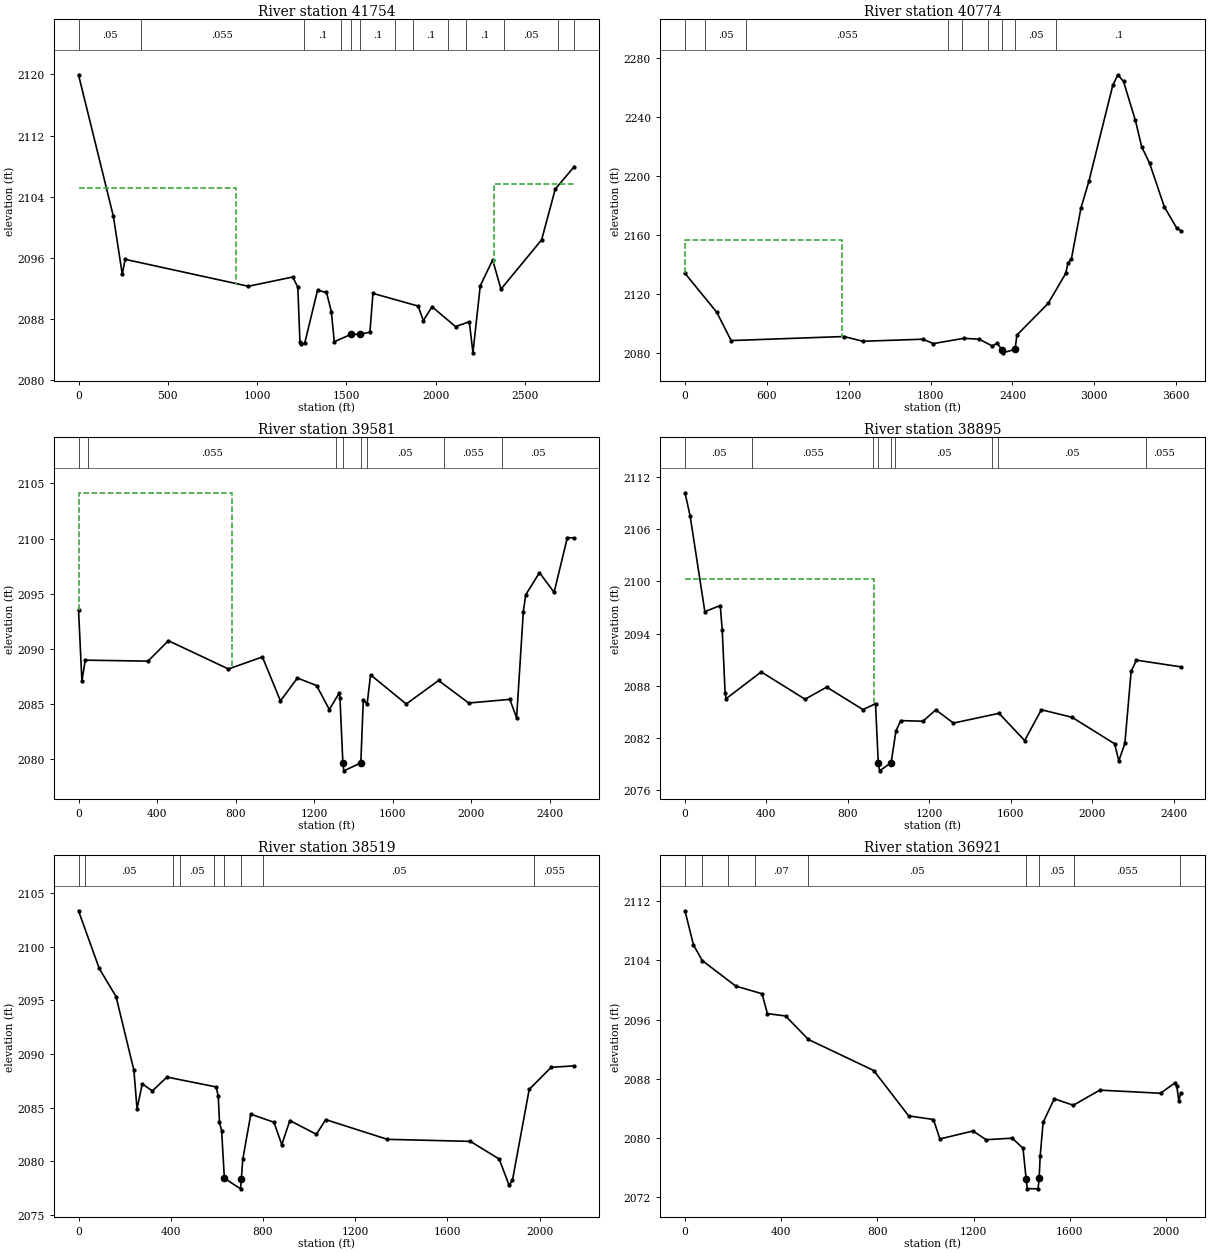
Type RM Length L Ch R = 1 ,41754   ,980.4,980.4,980.4
XS GIS Cut Line= 4
2253058.96716422602727.0834098822254241.65606626 603032.67099621
2255320.83637321602806.2408872872255659.20715769602506.902362822
#Sta/Elev= 30
       0 2119.95   195.4 2101.44     245 2093.89   261.5 2095.83   951.4 2092.31
  1199.3 2093.52  1228.2 2092.22  1240.1 2085.08  1244.5 2084.73  1267.1 2084.89
  1338.5 2091.77  1388.8 2091.51  1415.8 2089.01  1432.5 2085.06  1526.5 2086.03
 1577.552086.027    1632 2086.32  1649.2 2091.38  1902.3 2089.72  1931.2 2087.82
    1980 2089.63  2111.7 2087.04  2188.7 2087.68  2209.1 2083.61    2250 2092.37
  2319.4 2095.75  2366.1 2091.94  2593.7 2098.38  2670.2 2105.01    2776 2107.94
#Mann= 13 ,-1,0
       0     .05       0     350    .055       0 1261.53      .1       0
 1471.53     .08       0  1526.5    .045       0 1577.55      .1       0
 1771.53     .05       0 1871.53      .1       0 2071.53     .05       0
 2171.53      .1       0 2384.21     .05       0 2684.21      .1       0
 2775.98     .05       0
#XS Ineff= 2 , 0
          883.75 2105.14 2326.35         2105.72
Permanent Ineff=
       F       F
Bank Sta=1526.5,1577.55
XS Rating Curve= 0 ,0
Exp/Cntr=0.3,0.1

Type RM Length L Ch R = 1 ,40774   ,1192.7,1192.7,1192.7
XS GIS Cut Line= 4
2252857.79555345603323.2874583242253192.78577114603374.685171612
2255273.43616838603466.4647609472256439.11867192 603794.02919184
#Sta/Elev= 30
       0 2134.25   233.1 2107.81   338.3 2088.63  1165.2 2091.38  1303.2 2088.16
  1743.7 2089.55  1819.7 2086.57    2044 2090.17  2156.1 2089.54  2252.2 2084.97
  2288.2 2086.88  2321.1 2082.54  2328.2 2080.31  2419.1 2082.68  2432.7 2092.39
  2661.3 2113.77  2790.1 2134.14  2806.7 2141.09  2831.6 2143.89  2902.2 2178.58
  2960.4 2196.78  3134.9 2261.64  3172.3 2268.87  3213.9 2264.32  3301.1 2237.87
  3346.8  2220.1    3405 2208.87    3513 2179.29  3604.4  2164.8  3632.4 2163.24
#Mann= 9 ,-1,0
       0     .06       0     150     .05       0  448.91    .055       0
 1928.91      .1       0 2028.91     .05       0 2218.91      .1       0
  2321.1    .045       0  2419.1     .05       0 2721.58      .1       0
#XS Ineff= 2 , 0
         1149.46  2156.9
Permanent Ineff=
       F       F
Bank Sta=2321.1,2419.1
XS Rating Curve= 0 ,0
Exp/Cntr=0.3,0.1

Type RM Length L Ch R = 1 ,39581   ,686.6,686.6,686.6
XS GIS Cut Line= 5
2253156.01025901603561.3095653532254000.20004499603879.536309632
2254289.97779301604178.8105964362254367.42304319604283.886338554
2255190.27831181604976.141137507
#Sta/Elev= 30
       0 2093.57    17.3  2087.1    34.2 2088.99   353.9  2088.9   457.6 2090.75
   763.7 2088.19   936.6 2089.28  1028.6  2085.3  1114.9 2087.37  1212.7 2086.69
  1277.5 2084.52  1327.7 2086.01  1331.6 2085.59  1346.5 2079.69  1351.5 2078.97
 1437.912079.688  1450.7 2085.42  1469.9 2084.99  1487.6 2087.66  1669.3 2085.02
    1834 2087.15  1987.3 2085.11  2196.9 2085.44  2231.4 2083.77  2265.7 2093.39
  2277.7  2094.9  2347.8 2096.91  2422.5 2095.13  2489.8 2100.08  2524.6 2100.05
#Mann= 8 ,-1,0
       0     .05       0      50    .055       0 1312.18     .05       0
  1346.5    .045       0 1437.91      .1       0 1469.29     .05       0
 1859.29    .055       0 2159.29     .05       0
#XS Ineff= 2 , 0
          784.12 2104.14
Permanent Ineff=
       F       F
Bank Sta=1346.5,1437.91
XS Rating Curve= 0 ,0
Exp/Cntr=0.3,0.1

Type RM Length L Ch R = 1 ,38895   ,375.6,375.6,375.6
XS GIS Cut Line= 4
2252963.27952531603771.6556109982253534.73670228604146.741239099
2253892.78225974604715.9138610072254471.02666725605625.998065018
#Sta/Elev= 30
       0 2110.17      25 2107.55    97.5 2096.52   173.3 2097.21   182.9  2094.4
   197.2 2087.13     202 2086.51   374.5 2089.59   589.6 2086.45   695.9 2087.84
   874.1 2085.26   935.8 2085.93   949.2 2079.15   955.8 2078.22  1012.5 2079.15
  1036.1 2082.81  1059.8 2083.99  1168.5 2083.92  1231.7 2085.22  1318.7 2083.71
  1542.3 2084.83  1668.1  2081.7  1750.2 2085.24  1901.3 2084.37  2109.9 2081.33
  2130.6 2079.37  2160.4 2081.37    2191 2089.64  2217.1 2090.94  2434.2 2090.17
#Mann= 9 ,-1,0
       0     .05       0     330    .055       0  923.56     .08       0
   949.2    .045       0  1012.5      .1       0 1033.56     .05       0
 1505.98     .06       0 1535.98     .05       0 2265.98    .055       0
#XS Ineff= 2 , 0
           929.6 2100.24
Permanent Ineff=
       F       F
Bank Sta=949.2,1012.5
XS Rating Curve= 0 ,0
Exp/Cntr=0.3,0.1

Type RM Length L Ch R = 1 ,38519   ,1598.4,1598.4,1598.4
XS GIS Cut Line= 4
2252877.30606138604084.1786440522253130.90134031604222.434757017
2253651.52267286604990.4832836262254167.45568475 605768.24227995
#Sta/Elev= 30
       0 2103.36    89.8 2097.98   162.7 2095.36   240.2 2088.48   253.8 2084.88
   276.6  2087.2   320.5 2086.55   383.8 2087.84     597 2086.92   606.3 2086.04
   611.4 2083.61   620.8 2082.85   632.62078.403   702.9 2077.41   706.22078.317
   712.6 2080.18   747.4 2084.38   847.9 2083.62   881.7 2081.53   916.7 2083.78
  1031.9  2082.5  1072.2 2083.87  1339.9 2082.03  1699.9 2081.84  1824.8 2080.19
    1868 2077.73  1882.4 2078.22    1955 2086.69  2050.2 2088.75    2150 2088.89
#Mann= 9 ,-1,0
       0     .06       0      30     .05       0  408.83    .055       0
  438.83     .05       0  588.83      .1       0   632.6    .045       0
   706.2      .1       0  798.83     .05       0 1976.71    .055       0
Bank Sta=632.6,706.2
XS Rating Curve= 0 ,0
Exp/Cntr=0.3,0.1

Type RM Length L Ch R = 1 ,36921   ,251,251,251
XS GIS Cut Line= 4
2252356.85369494605039.2134501972253137.08369017605450.271887188
2253694.88436128605733.2989752492254186.45630797605988.888765887
#Sta/Elev= 30
       0  2110.7    35.4 2106.08    71.6 2103.98   211.2 2100.52   320.2 2099.49
   342.8  2096.8   418.5 2096.48   513.2 2093.31   785.1 2089.11   930.2 2082.98
  1033.4 2082.49  1060.3 2079.86  1197.7 2080.94  1252.4 2079.76  1360.8 2079.97
  1405.7 2078.62    1419 2074.44  1423.6 2073.15  1468.5 2073.12  1472.9 2074.52
  1477.4 2077.59  1489.4  2082.1  1535.9 2085.29    1615 2084.42  1725.2 2086.46
  1977.7 2086.04    2036  2087.4  2045.1 2087.07    2054    2085  2061.4 2086.04
#Mann= 9 ,-1,0
       0     .06       0      70     .05       0     180     .06       0
     290     .07       0     510     .05       0    1419    .045       0
  1472.9     .05       0 1617.39    .055       0 2057.39     .05       0
Bank Sta=1419,1472.9
XS Rating Curve= 0 ,0
Exp/Cntr=0.3,0.1

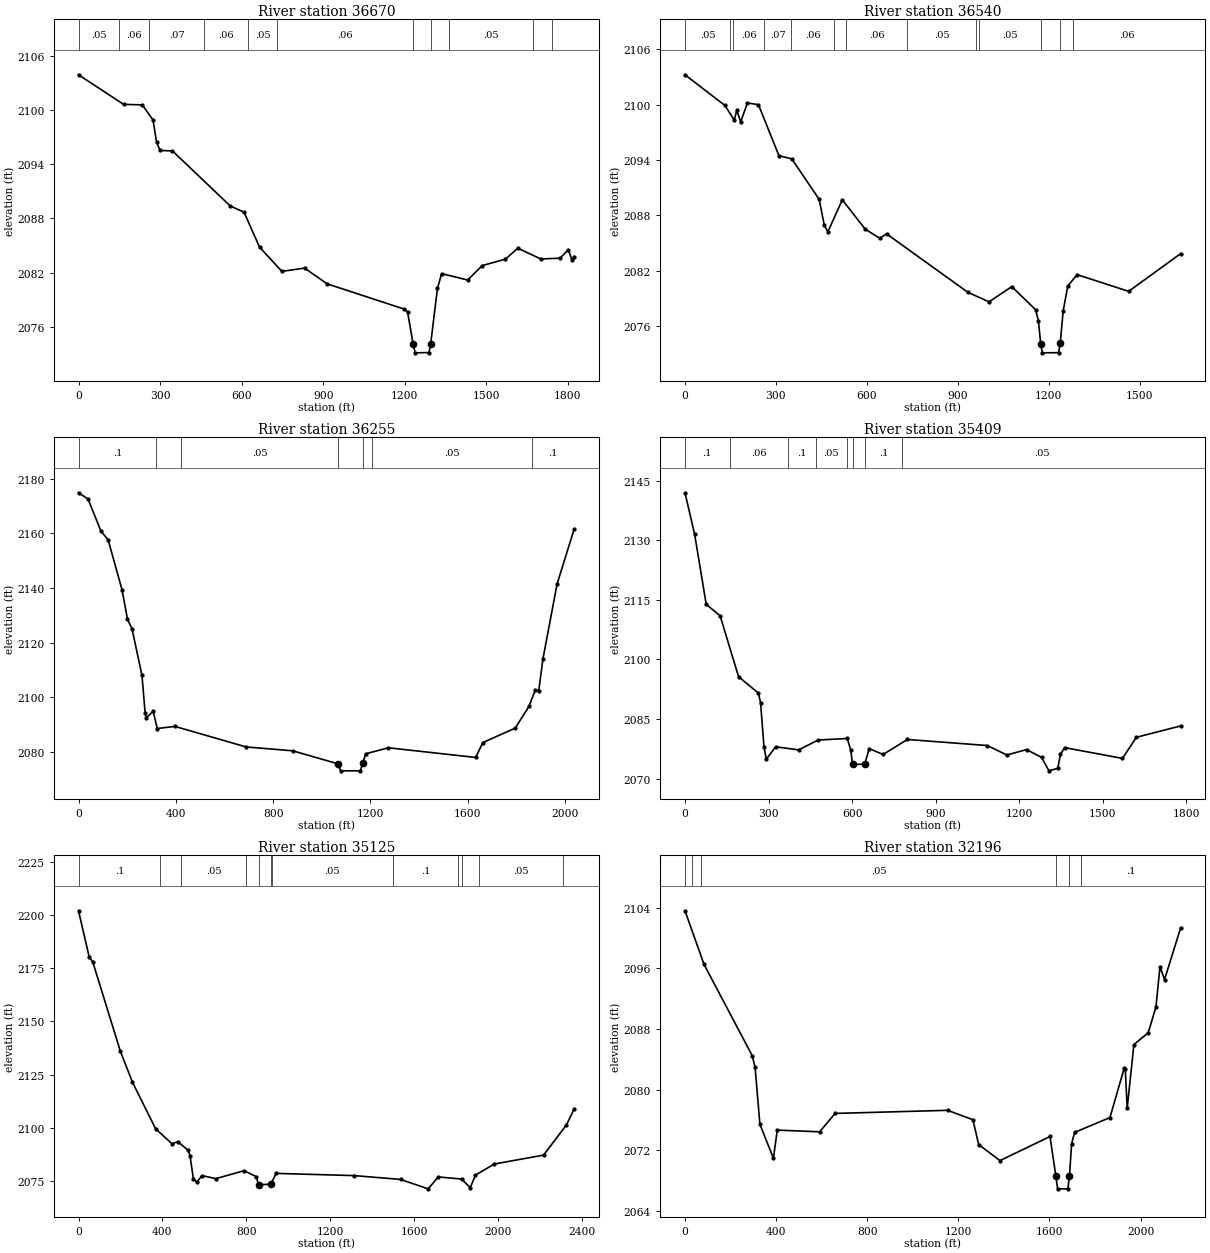
Type RM Length L Ch R = 1 ,36670   ,129.8,129.8,129.8
BEGIN DESCRIPTION:
structure
END DESCRIPTION:
XS GIS Cut Line= 5
2252374.42322022605383.6810331642252663.22445161605514.095115521
2252744.72206884605621.6712294492253724.11602495606000.318720924
2253950.38920172606228.224688078
#Sta/Elev= 30
       0 2103.87   165.7  2100.6   234.5 2100.54     274 2098.88   287.2  2096.4
   300.4  2095.5   345.5 2095.45   558.5 2089.35   608.8 2088.67   665.7 2084.82
   747.9 2082.13   831.5 2082.49   914.4 2080.75  1197.5 2077.96  1210.3 2077.64
 1230.452074.132    1238 2073.12  1289.2 2073.15  1295.4 2074.14  1320.1 2080.24
  1335.6 2081.88  1431.5 2081.17  1484.8 2082.77  1570.1 2083.48  1615.8 2084.69
  1700.4  2083.5  1771.2 2083.59  1801.8 2084.53  1814.2 2083.43    1823 2083.75
#Mann= 11 ,-1,0
       0     .05       0     150     .06       0     260     .07       0
  461.84     .06       0  621.84     .05       0  731.84     .06       0
 1230.45    .045       0  1295.4     .08       0 1361.84     .05       0
 1671.88     .06       0 1741.88     .05       0
Bank Sta=1230.45,1295.4
XS Rating Curve= 0 ,0
Exp/Cntr(USF)=0,0
Exp/Cntr=0.3,0.1

Type RM Length L Ch R = 1 ,36540   ,285,285,285
BEGIN DESCRIPTION:
structure
END DESCRIPTION:
XS GIS Cut Line= 4
2252361.39158684605481.1161815272252600.49954816605557.515839902
2252756.08334933605713.5104834872253815.28544338 606195.17827779
#Sta/Elev= 30
       0 2103.23   131.6 2099.91   162.5 2098.33   170.9 2099.38   183.7 2098.12
   205.9 2100.18   242.3 2099.99   309.9 2094.47   352.4 2094.12   442.6 2089.74
   459.6 2086.93   471.3 2086.22   518.9 2089.69   594.5 2086.51   642.8 2085.52
   664.8 2086.01   933.3 2079.67  1003.1 2078.64  1077.8 2080.29  1156.6 2077.79
  1165.7 2076.62  1173.3 2074.09  1178.9 2073.12  1232.3 2073.14  1237.8 2074.17
  1247.4 2077.64  1262.5 2080.34  1293.1 2081.59  1463.4 2079.78  1634.9 2083.86
#Mann= 13 ,-1,0
       0     .05       0     150      .1       0     160     .06       0
  261.02     .07       0  351.02     .06       0  491.34     .05       0
  531.34     .06       0  731.34     .05       0  961.34     .06       0
  971.34     .05       0  1173.3    .045       0  1237.8     .05       0
 1281.34     .06       0
Bank Sta=1173.3,1237.8
XS Rating Curve= 0 ,0
Exp/Cntr(USF)=0,0
Exp/Cntr=0.3,0.1

Type RM Length L Ch R = 1 ,36255   ,845.9,845.9,845.9
XS GIS Cut Line= 4
2252202.03091019605816.1179741282252790.20952738605959.406330446
2253453.57642368606367.3765786022254049.36207119606636.674338126
#Sta/Elev= 30
       0 2174.89    39.3 2172.59    92.8 2160.73   121.6 2157.76   179.2 2139.29
   201.3 2128.63   220.4 2124.96   260.9 2108.05   273.9 2094.33     278 2092.45
   306.9 2094.93   323.8 2088.61   396.6 2089.38   689.5 2081.86   880.1 2080.46
  1067.5 2075.68  1077.3 2073.12  1158.5 2073.12 1169.362076.036  1180.9 2079.36
    1274 2081.56  1632.8 2078.02  1662.6 2083.47  1795.2 2088.74  1852.3 2096.71
  1878.6  2102.8  1892.4 2102.46  1909.4    2114  1967.9 2141.56    2038 2161.61
#Mann= 7 ,-1,0
       0      .1       0     320     .06       0     420     .05       0
  1067.5    .045       0 1169.36      .1       0 1205.38     .05       0
 1864.16      .1       0
Bank Sta=1067.5,1169.36
XS Rating Curve= 0 ,0
Exp/Cntr=0.3,0.1

Type RM Length L Ch R = 1 ,35409   ,284.4,284.4,284.4
XS GIS Cut Line= 2
2251962.69224492606453.9475559492253677.36464455606930.015331559
#Sta/Elev= 30
       0 2141.98    34.7  2131.5    76.3 2113.86   126.1 2111.01   192.5 2095.62
   263.8 2091.52   271.4 2089.07   283.8 2077.85   292.1 2074.86   325.3    2078
   408.4  2077.2   478.2  2079.7   582.7 2080.08   595.2 2077.13   601.7 2073.53
     645  2073.6   661.6 2077.51   711.4 2076.06   798.6 2079.83    1085 2078.31
  1155.6 2075.92  1226.2 2077.28  1280.1 2075.33  1306.8 2071.93  1338.3 2072.56
    1348  2076.1  1363.2 2077.78  1570.7 2075.06  1620.5 2080.38  1779.5 2083.24
#Mann= 8 ,-1,0
       0      .1       0     160     .06       0     370      .1       0
     470     .05       0     580      .1       0   601.7    .045       0
     645      .1       0     780     .05       0
Bank Sta=601.7,645
XS Rating Curve= 0 ,0
Exp/Cntr=0.3,0.1

Type RM Length L Ch R = 1 ,35125   ,2928.3,2928.3,2928.3
XS GIS Cut Line= 3
2251637.62210717606702.8676601452253519.40589585607122.974402443
2253948.60805462607054.738467302
#Sta/Elev= 30
       0 2201.94      51 2180.22    67.7 2177.97   199.3 2136.02   256.7  2121.5
   367.4 2099.51   445.3 2092.52   473.1 2093.43   523.1 2089.42   531.3 2086.91
   547.7 2075.94   564.1 2074.43   588.7 2077.55   654.3 2076.09   789.5 2079.84
   846.9 2077.06   858.4 2073.24   916.6 2073.48   942.2 2078.57  1314.1 2077.53
  1535.2 2075.73  1666.6 2071.31  1715.2 2076.91  1826.4  2075.9  1867.4 2071.83
    1892 2077.75  1981.5 2082.96  2216.9 2087.16  2325.8 2101.33  2362.7 2108.79
#Mann= 12 ,-1,0
       0      .1       0     390     .06       0     490     .05       0
     800      .1       0   858.4    .045       0   916.6      .1       0
     920     .05       0    1500      .1       0    1810     .05       0
    1830      .1       0    1910     .05       0 2308.11      .1       0
Bank Sta=858.4,916.6
XS Rating Curve= 0 ,0
Exp/Cntr=0.3,0.1

Type RM Length L Ch R = 1 ,32196   ,702.7,702.7,702.7
XS GIS Cut Line= 4
 2251853.1306667608287.6264121632253384.43384895607759.522161256
2253460.84514028  607741.61720522253915.25505212 607594.07122447
#Sta/Elev= 30
       0 2103.59    83.6 2096.53   295.2 2084.49   307.9 2082.94     329 2075.44
   388.3 2070.97   405.2 2074.68   591.4 2074.46   659.1 2076.88  1152.7 2077.29
  1264.1 2076.05  1289.5 2072.77  1383.1 2070.66  1602.6 2073.84  1628.2 2068.64
    1636 2066.94  1681.2 2066.94  1688.1 2068.69  1697.6 2072.91  1710.8 2074.38
  1865.8 2076.34  1928.9  2082.9  1933.1  2082.7  1941.5 2077.55  1970.9 2085.95
    2034 2087.52  2067.7 2090.91  2085.4 2096.21  2105.5 2094.53  2176.1 2101.33
#Mann= 6 ,-1,0
       0     .05       0      30     .06       0      70     .05       0
  1628.2    .045       0  1688.1     .05       0 1738.29      .1       0
Bank Sta=1628.2,1688.1
XS Rating Curve= 0 ,0
Exp/Cntr=0.3,0.1

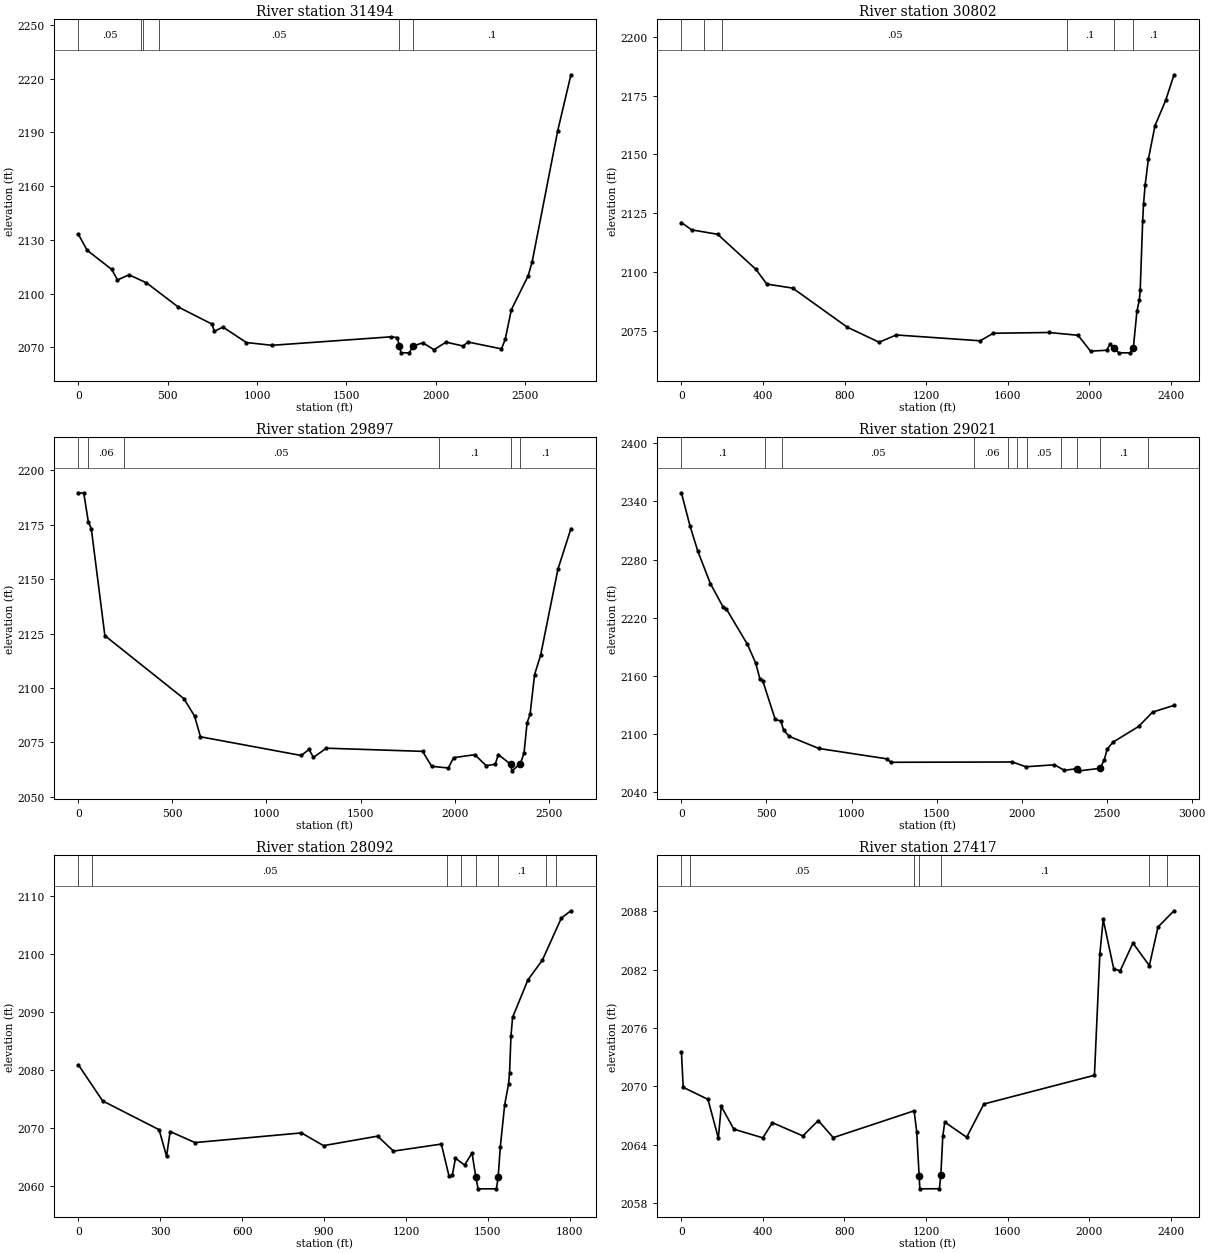
Type RM Length L Ch R = 1 ,31494   ,692,692,692
XS GIS Cut Line= 4
2251383.46262525608724.5766996372252207.63318889608605.892721622
2253723.96337935608261.6052467732254064.22188614608120.546584897
#Sta/Elev= 30
       0 2133.11    49.2 2124.18   186.6 2113.49   218.9 2107.63   283.6 2110.48
   380.6 2106.05   558.2 2092.57   748.4 2082.94   760.5 2078.96   809.1 2081.32
   939.9  2072.7  1083.4 2071.14  1747.9 2075.87  1784.8 2075.47 1795.692070.904
  1805.4 2066.95  1850.5 2066.94  1875.1 2070.93  1928.4 2072.49  1989.9 2068.68
  2057.2 2072.92  2154.1 2070.71  2178.6 2073.01  2367.3 2069.16  2388.1 2074.39
  2422.5 2090.98  2516.7 2109.93  2539.4 2117.91  2681.9 2190.85  2755.9 2222.14
#Mann= 6 ,-1,0
       0     .05       0     350     .07       0     360     .06       0
     450     .05       0 1795.69    .045       0  1875.1      .1       0
Bank Sta=1795.69,1875.1
XS Rating Curve= 0 ,0
Exp/Cntr=0.3,0.1

Type RM Length L Ch R = 1 ,30802   ,905,905,905
XS GIS Cut Line= 4
2251522.47673771609028.433798647 2252571.7499794609027.770554687
2253705.01875629608813.2575859082253916.85563361608790.993909206
#Sta/Elev= 30
       0 2121.03    49.7 2117.91   177.7 2116.02   365.7 2101.07   418.7 2094.82
   545.7 2093.11   813.7 2076.46   969.7 2070.08  1053.8 2073.17    1465 2070.69
  1530.1  2073.9  1802.8 2074.22  1945.3 2073.03  2006.4 2066.28  2085.6 2066.66
  2101.1 2069.15  2119.9 2067.73  2144.8 2065.56  2201.8 2065.56  2216.5  2067.8
    2234 2083.32  2246.1 2088.14  2250.1 2092.42  2262.1 2121.62  2266.2 2128.71
  2274.2 2136.98  2290.3 2148.07  2322.5 2162.22  2374.8 2172.97  2415.7 2183.91
#Mann= 6 ,-1,0
       0     .05       0     110     .06       0     200     .05       0
 1889.27      .1       0  2119.9    .045       0  2216.5      .1       0
Bank Sta=2119.9,2216.5
XS Rating Curve= 0 ,0
Exp/Cntr=0.3,0.1

Type RM Length L Ch R = 1 ,29897   ,875.5,875.5,875.5
XS GIS Cut Line= 4
2251483.28876233609553.0771209882252619.94546258609576.274697132
2253826.96054616609714.3942176222254092.94148309 609729.75169671
#Sta/Elev= 30
       0 2189.71    28.9 2189.54    52.9 2176.41    68.9 2173.15   140.9 2124.06
     561 2095.11   617.5 2087.13     649 2077.59  1184.9 2068.99  1225.7 2071.79
  1249.8 2068.12    1318 2072.35  1829.6 2070.89  1877.9 2064.02  1966.5 2063.24
  1994.7    2068  2107.4 2069.36  2167.8 2064.31  2216.1    2065  2232.2 2069.41
  2297.6 2065.01  2304.7 2061.94    2350 2065.25    2369 2070.21  2385.1 2083.99
  2401.1 2087.94  2425.1 2106.18  2457.2 2115.08  2549.3 2154.65  2618.2 2173.23
#Mann= 6 ,-1,0
       0      .1       0      50     .06       0     240     .05       0
 1916.89      .1       0  2297.6    .045       0    2350      .1       0
Bank Sta=2297.6,2350
XS Rating Curve= 0 ,0
Exp/Cntr=0.3,0.1

Type RM Length L Ch R = 1 ,29021   ,929.6,929.6,929.6
XS GIS Cut Line= 4
2251154.02509216610122.7223328592251849.46974361609966.256898447
 2253528.2752223610500.5651308652253938.51813755610597.373392406
#Sta/Elev= 30
       0 2348.94    49.9 2315.04    96.5  2288.6   170.4 2255.18   244.1 2231.31
   264.6  2228.9   387.6 2192.64   436.8 2173.21   461.4 2156.85   477.8 2155.06
   551.6 2114.98   584.4 2113.39   600.8 2103.99   633.6 2097.59     808 2085.05
  1206.8 2074.38    1232 2070.79  1945.6 2071.09  2025.4 2066.19  2193.3 2068.19
  2251.8 2062.48  2325.4 2064.19  2340.2 2061.96  2461.9 2064.55  2486.8  2073.6
  2503.3  2084.5  2538.2 2091.62  2688.2 2107.77  2770.4  2122.6  2896.1 2129.53
#Mann= 11 ,-1,0
       0      .1       0     490     .06       0     590     .05       0
 1722.83     .06       0 1922.83     .05       0 1972.83      .1       0
 2032.83     .05       0 2232.83      .1       0  2325.4    .045       0
  2461.9      .1       0 2744.61     .05       0
Bank Sta=2325.4,2461.9
XS Rating Curve= 0 ,0
Exp/Cntr=0.3,0.1

Type RM Length L Ch R = 1 ,28092   ,674.5,674.5,674.5
XS GIS Cut Line= 5
 2251760.9998135610621.4173226352253062.71967535611288.269915927
2253089.41960932611309.6586549722253116.11954328611331.047394016
2253343.13004539611482.677906474
#Sta/Elev= 30
       0 2080.84      89 2074.61   295.7 2069.64   323.1 2065.05   336.1 2069.33
   427.2 2067.42     817 2069.09   897.9 2066.89  1096.1 2068.53  1154.1 2065.95
  1329.4 2067.16  1357.4 2061.67  1369.8 2061.82  1381.1 2064.71  1414.8 2063.55
  1441.8 2065.63  1455.8 2061.43    1464 2059.44  1531.1 2059.44 1537.462061.445
  1545.5 2066.72  1561.4 2073.95  1575.8 2077.57  1579.2 2079.47  1584.5 2085.85
  1590.3 2089.01  1646.5 2095.49  1699.4 2098.89  1769.1 2106.17    1804 2107.41
#Mann= 8 ,-1,0
       0     .06       0      50     .05       0    1350     .08       0
    1400      .1       0  1455.8    .045       0 1537.46      .1       0
 1711.01     .07       0 1751.01     .05       0
Bank Sta=1455.8,1537.46
XS Rating Curve= 0 ,0
Exp/Cntr=0.3,0.1

Type RM Length L Ch R = 1 ,27417   ,432.4,432.4,432.4
XS GIS Cut Line= 4
2251632.29296214611216.7042140512252494.36762989611730.407713565
2253004.97225909612043.0659809592253725.54788409 611663.26342853
#Sta/Elev= 30
       0 2073.54     8.7 2069.89   130.2 2068.65   181.2 2064.66   195.4 2067.94
     257 2065.58   399.4 2064.69   446.3 2066.25   595.9 2064.89   671.3 2066.47
   744.9 2064.71  1141.7 2067.47  1154.4 2065.331166.3132060.803  1169.8 2059.44
  1265.8 2059.45 1272.892060.875  1282.4 2064.87  1292.2 2066.31  1399.6 2064.75
  1483.9 2068.17  2026.5 2071.13  2053.1 2083.63  2069.5 2087.17  2121.3 2082.07
    2153 2081.89  2215.4 2084.74  2295.9 2082.41  2338.4 2086.39  2416.8 2088.06
#Mann= 7 ,-1,0
       0     .06       0      40     .05       0 1143.53      .1       0
1166.313    .045       0 1272.89      .1       0 2292.25     .05       0
 2382.25     .06       0
Bank Sta=1166.313,1272.89
XS Rating Curve= 0 ,0
Exp/Cntr(USF)=0,0
Exp/Cntr=0.3,0.1