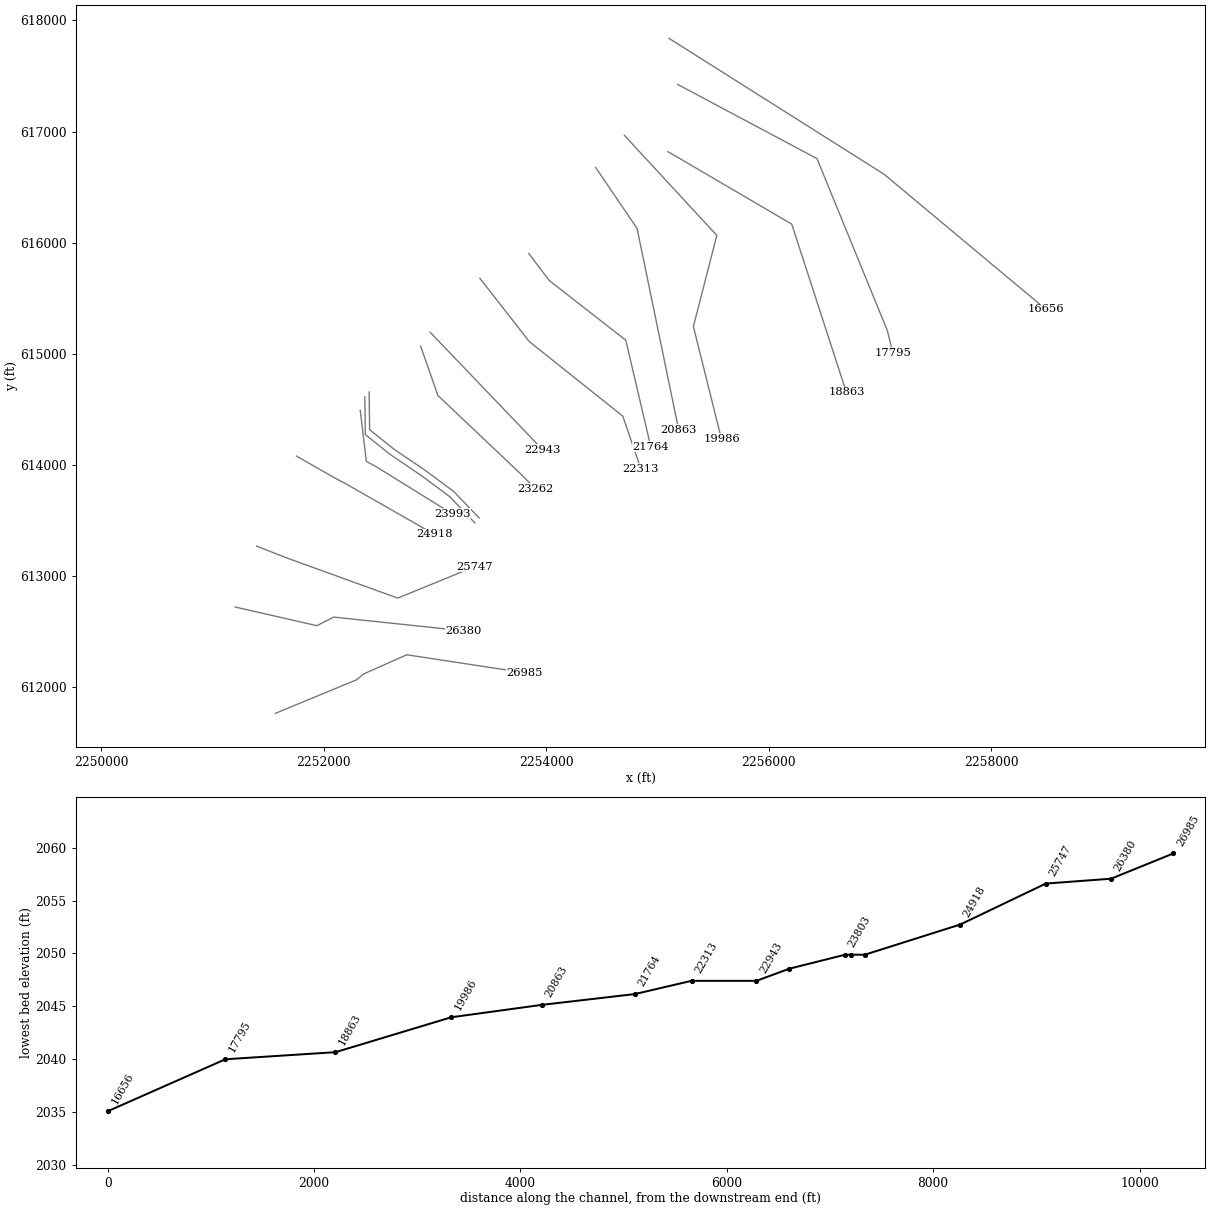
HEC-RAS study TYGVRV2.prj: TYGVRV2

--- TYGVRV2.g01 (geometry) --- (continued)

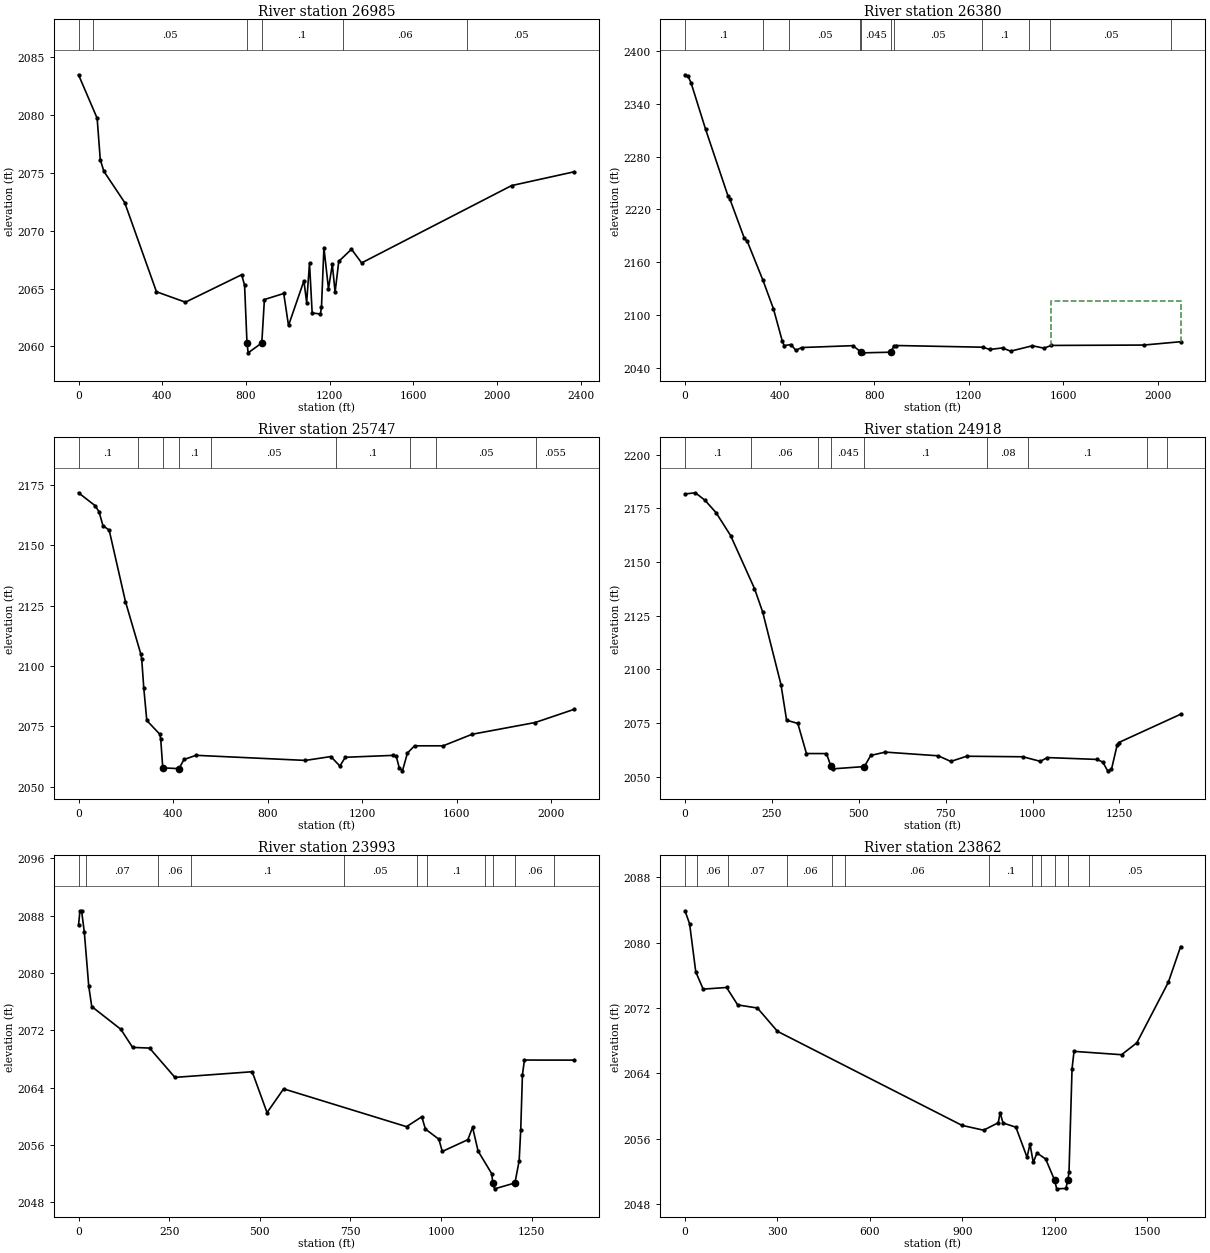
Type RM Length L Ch R = 1 ,26985   ,604.4,604.4,604.4
XS GIS Cut Line= 5
2251564.19149181611764.8974834032252296.77525716612067.951655825
2252356.88907013612118.793848214 2252745.8081862612292.194368967
2253803.61943721612130.945166806
#Sta/Elev= 30
       0 2083.44      89 2079.69   103.9 2076.12   121.2 2075.11   220.5 2072.42
   372.3 2064.72   510.8 2063.82   779.2 2066.19   793.2 2065.28   804.6 2060.34
   810.3 2059.45  875.422060.302   887.9 2064.05   980.2 2064.57    1003 2061.81
  1076.6 2065.66  1089.7 2063.79  1103.3 2067.18    1116 2062.89  1155.4  2062.8
  1160.5 2063.39  1172.1 2068.53  1193.9 2064.98  1212.3 2067.08  1225.5 2064.68
    1243 2067.34  1303.8 2068.39  1352.3 2067.21  2068.5 2073.88  2367.4 2075.07
#Mann= 6 ,-1,0
       0     .07       0      70     .05       0   804.6    .045       0
  875.42      .1       0 1261.52     .06       0 1857.35     .05       0
Bank Sta=804.6,875.42
XS Rating Curve= 0 ,0
Exp/Cntr=0.3,0.1

Type RM Length L Ch R = 1 ,26380   ,632.8,632.8,632.8
XS GIS Cut Line= 4
2251203.29744842612721.8682037782251938.05510863612553.884588795
2252089.83967956612631.3196518152253255.41510529612508.105947854
#Sta/Elev= 30
       0 2373.07    13.2 2371.26    25.5 2364.09    87.1  2311.2   181.4 2235.78
   189.6 2232.04   251.2 2187.09   263.5 2183.78     330 2139.36   374.3    2107
   411.2 2070.79   419.4 2065.19   448.1 2066.52   468.7 2059.88   493.3 2063.08
   710.8 2065.22     745 2057.75   751.8 2057.06   870.2 2057.79   882.6 2064.35
   894.5 2065.38  1260.3 2063.46  1288.5 2060.87  1342.9 2062.65    1377 2058.96
  1469.5 2065.11  1517.7 2062.37  1549.9 2065.47  1940.1  2065.9  2096.2  2069.7
#Mann= 11 ,-1,0
       0      .1       0     330     .06       0     440     .05       0
     740     .08       0     745    .045       0   870.2      .1       0
  883.72     .05       0 1254.11      .1       0 1454.11     .06       0
 1544.11     .05       0 2054.11     .06       0
#XS Ineff= 2 , 0
                         1547.99         2115.96
Permanent Ineff=
       F       F
Bank Sta=745,870.2
XS Rating Curve= 0 ,0
Exp/Cntr(USF)=0,0
Exp/Cntr=0.3,0.1

Type RM Length L Ch R = 1 ,25747   ,829.5,829.5,829.5
XS GIS Cut Line= 4
 2251395.3489577 613270.212127662251665.07379607613164.416970863
2252665.28926335612802.0605187242253352.93104048613083.497631207
#Sta/Elev= 30
       0 2171.81    69.6 2166.52    86.8 2163.96   103.3 2158.21   129.8 2156.31
   198.5 2126.75   263.8 2104.91   267.3 2102.99   276.1 2090.92   288.8 2077.46
   344.1 2071.74   347.8 2069.69  356.412057.833   424.9 2057.51   446.2  2061.3
   497.2 2063.03   959.9 2060.92  1067.3 2062.52  1105.6 2058.59  1128.5 2062.22
  1331.1 2063.01  1343.9 2062.66  1356.7 2057.86  1370.4  2056.6  1391.3 2063.99
  1421.5 2066.97  1542.5 2066.97  1664.8 2071.75  1931.7 2076.62  2096.6 2082.09
#Mann= 9 ,-1,0
       0      .1       0     250     .06       0  356.41    .045       0
   424.9      .1       0  559.73     .05       0 1089.73      .1       0
 1403.56     .06       0 1513.56     .05       0 1933.56    .055       0
Bank Sta=356.41,424.9
XS Rating Curve= 0 ,0
Exp/Cntr=0.3,0.1

Type RM Length L Ch R = 1 ,24918   ,924.6,924.6,924.6
XS GIS Cut Line= 4
2251754.24915792614080.0583686572252078.99590297613894.539913336
 2252223.5487689613816.4241849972252994.53909577613375.998607544
#Sta/Elev= 30
       0 2181.64    29.9  2182.2    57.5 2178.72    89.7 2172.89   131.2  2162.3
     200 2137.62   223.4 2126.77   276.2 2092.91   292.4 2076.32   324.7 2074.79
   349.5 2060.79   407.2 2060.76  419.472055.095   425.4 2053.66   516.3 2054.72
   534.5  2059.9   576.3 2061.45   728.8 2059.73   764.8 2057.11   810.6 2059.53
   972.1 2059.28  1022.7 2057.15  1042.5 2058.91  1186.2 2058.04  1202.4 2056.75
  1216.2 2052.73  1227.2 2053.42  1243.8 2064.93  1247.7 2065.87  1426.2 2079.09
#Mann= 9 ,-1,0
       0      .1       0     190     .06       0     384      .1       0
  419.47    .045       0   516.3      .1       0  868.31     .08       0
  988.31      .1       0 1328.31     .08       0 1388.31     .06       0
Bank Sta=419.47,516.3
XS Rating Curve= 0 ,0
Exp/Cntr=0.3,0.1

Type RM Length L Ch R = 1 ,23993   ,131.6,131.6,131.6
XS GIS Cut Line= 4
2252327.58973293614493.1758964812252382.63539677614032.716977887
2252469.35450347613985.5836205622253153.46669205613561.554474848
#Sta/Elev= 30
       0 2086.67     3.9 2088.66     8.5  2088.7    16.1 2085.68    28.2  2078.2
    36.5 2075.33   116.8 2072.15   149.1 2069.63   196.1 2069.53   265.9 2065.44
   479.1 2066.23   520.1 2060.52   565.8 2063.84   904.9 2058.56   946.9 2059.94
     957 2058.22     994 2056.81  1003.5  2055.1    1074 2056.74  1087.1 2058.47
  1102.2 2055.16  1139.9 2051.99  1142.9 2050.66  1147.8 2049.88  1203.9  2050.7
  1215.6 2053.81  1219.9 2058.12  1224.6 2065.81  1230.1 2067.86  1367.3 2067.85
#Mann= 11 ,-1,0
       0     .06       0      20     .07       0     220     .06       0
     310      .1       0  732.44     .05       0  932.44     .08       0
  962.44      .1       0 1122.44     .07       0  1142.9    .045       0
  1203.9     .06       0 1312.44     .05       0
Bank Sta=1142.9,1203.9
XS Rating Curve= 0 ,0
Exp/Cntr=0.3,0.1

Type RM Length L Ch R = 1 ,23862   ,58.7,58.7,58.7
BEGIN DESCRIPTION:
structure
END DESCRIPTION:
XS GIS Cut Line= 6
2252369.18971142614612.1697892182252373.79568336614273.630851053
2252589.59183377614099.9854423492252871.64313196613908.593490001
2253131.86903208613715.5226608792253358.51739671613478.801035606
#Sta/Elev= 30
       0 2083.88      15 2082.28      35 2076.41      59  2074.3     135  2074.5
     171 2072.37     235 2071.99   300.1 2069.14   898.8 2057.64   968.9 2057.05
  1016.4 2057.96  1022.6  2059.2  1031.8 2057.93  1073.6 2057.42  1109.8 2053.75
  1119.4 2055.36    1130 2053.12  1142.2 2054.26  1170.3 2053.53  1199.4 2050.93
  1206.1 2049.88    1236 2049.93  1242.3 2051.01    1246  2051.9  1255.9 2064.59
  1262.3 2066.69  1416.6 2066.28    1466 2067.73  1568.1 2075.12  1608.2 2079.51
#Mann= 12 ,-1,0
       0      .1       0      40     .06       0     140     .07       0
     330     .06       0  478.57      .1       0  518.57     .06       0
  986.41      .1       0 1126.41     .06       0 1156.41     .07       0
  1199.4    .045       0  1242.3     .07       0 1310.44     .05       0
Bank Sta=1199.4,1242.3
XS Rating Curve= 0 ,0
Exp/Cntr(USF)=0,0
Exp/Cntr=0.3,0.1

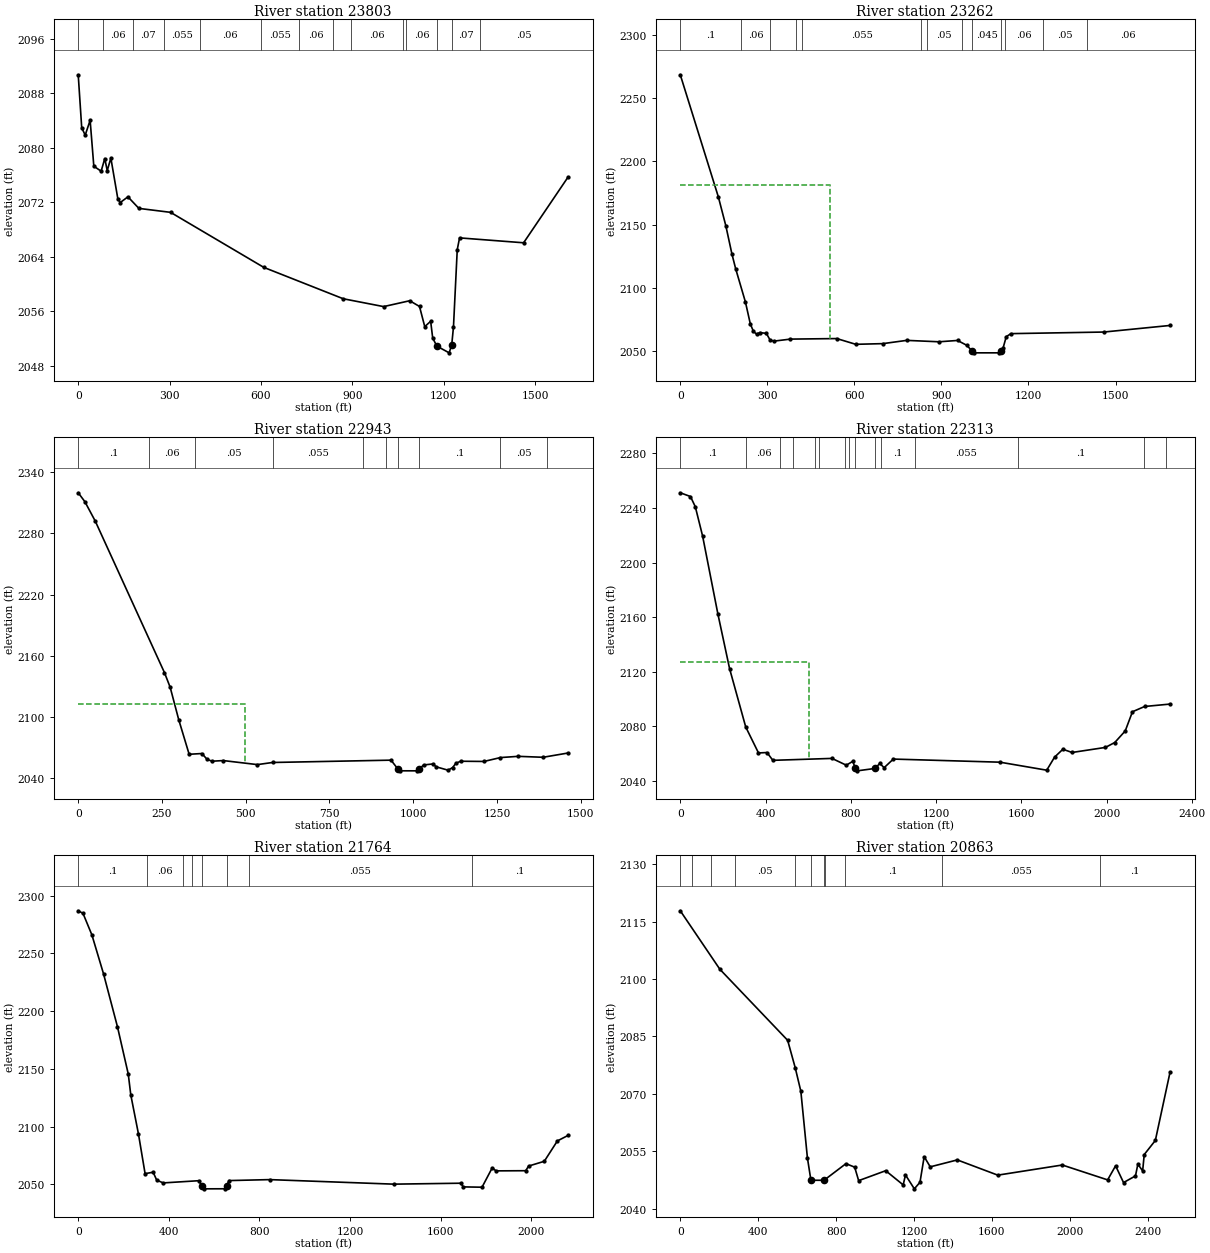
Type RM Length L Ch R = 1 ,23803   ,540.6,540.6,540.6
BEGIN DESCRIPTION:
structure
END DESCRIPTION:
XS GIS Cut Line= 6
 2252407.7329657614656.3447928672252412.33893764614317.805854702
2252628.13508805614144.1604459982252910.18638624 613952.76849365
2253170.41228636613759.6976645282253397.06065099613522.976039255
#Sta/Elev= 30
       0 2090.71    11.5 2082.91      23 2081.85    39.1 2084.03    51.2 2077.29
    75.2 2076.55    87.2 2078.41    95.2 2076.64   107.2 2078.47   129.9 2072.54
   137.7 2071.94   163.2 2072.79   199.2 2071.09   303.2 2070.51   609.2 2062.43
   870.2 2057.82  1002.7 2056.67  1088.4 2057.53  1120.5 2056.69  1137.7 2053.73
  1157.1 2054.51  1163.8 2052.06  1177.3 2050.87  1217.9 2049.88  1226.3 2051.07
    1232 2053.67  1244.4 2065.03    1252 2066.76  1462.3 2066.04  1608.2 2075.69
#Mann= 14 ,-1,0
       0      .1       0      80     .06       0     180     .07       0
     280    .055       0  398.57     .06       0  598.57    .055       0
  725.56     .06       0  835.56    .055       0  895.56     .06       0
 1066.41      .1       0 1076.41     .06       0  1177.3    .045       0
  1226.3     .07       0 1320.44     .05       0
Bank Sta=1177.3,1226.3
XS Rating Curve= 0 ,0
Exp/Cntr(USF)=0,0
Exp/Cntr=0.3,0.1

Type RM Length L Ch R = 1 ,23262   ,319.5,319.5,319.5
XS GIS Cut Line= 4
2252871.03479076615069.1909285232253025.91943044614625.389442307
2253756.77467716613932.9536592022253905.89997051613783.441267722
#Sta/Elev= 30
       0 2268.39   131.3 2171.78   156.8 2149.21   177.9  2126.8   190.7  2115.2
   224.6 2088.68   241.5 2071.33   252.1 2065.55   262.7 2063.37   274.1 2064.55
   296.6 2063.96   309.3 2058.78     322  2057.8   379.8 2059.42   539.3 2059.84
   604.8  2055.3   698.2 2055.84   780.2 2058.41   891.9  2057.3   955.6 2058.35
     988 2054.42  1005.4 2049.98  1011.2 2048.56  1098.5 2048.56  1105.6 2049.91
  1112.3 2052.26  1123.4 2061.37  1139.5 2063.74  1459.5    2065    1688 2070.22
#Mann= 13 ,-1,0
       0      .1       0     210     .06       0     310     .07       0
     400     .05       0     420    .055       0  830.05      .1       0
  850.05     .05       0  970.05      .1       0  1005.4    .045       0
  1105.6      .1       0 1120.05     .06       0 1250.05     .05       0
 1400.05     .06       0
#XS Ineff= 2 , 0
          515.96 2181.55
Permanent Ineff=
       F       F
Bank Sta=1005.4,1105.6
XS Rating Curve= 0 ,0
Exp/Cntr=0.3,0.1

Type RM Length L Ch R = 1 ,22943   ,629.4,629.4,629.4
XS GIS Cut Line= 2
2252956.84401416615193.9270898152253967.74515536  614137.5528869
#Sta/Elev= 30
       0 2319.67    19.9 2310.93    50.9 2291.91   257.5 2143.52   274.5  2129.2
     300  2097.5   331.1 2063.62   369.3 2064.37   384.8 2058.58   399.7 2056.84
   432.9 2057.47   534.8 2053.51     580 2055.59   933.7 2057.87  954.362049.125
   959.1 2047.45  1011.5 2047.41  1017.92049.141  1030.8 2053.16  1057.8 2054.11
  1069.3 2051.27  1104.1 2048.03  1117.6 2050.66  1127.2 2054.79  1141.5 2056.81
  1210.9  2056.6  1260.3  2060.4  1313.2 2061.61  1387.5 2060.69  1462.1 2064.87
#Mann= 10 ,-1,0
       0      .1       0     210     .06       0     350     .05       0
     580    .055       0     850      .1       0     920     .05       0
  954.36    .045       0  1017.9      .1       0    1260     .05       0
    1400     .06       0
#XS Ineff= 2 , 0
          497.28 2113.06
Permanent Ineff=
       F       F
Bank Sta=954.36,1017.9
XS Rating Curve= 0 ,0
Exp/Cntr(USF)=0,0
Exp/Cntr=0.3,0.1

Type RM Length L Ch R = 1 ,22313   ,549.2,549.2,549.2
XS GIS Cut Line= 4
2253403.59433624615679.6563341512253847.94726035615110.121440696
2254688.66535305614439.5130217812254850.93735221 613966.05854431
#Sta/Elev= 30
       0 2251.14    47.8  2248.4    70.6 2240.88   104.8 2219.43   176.5 2162.33
   231.4 2122.28   307.1 2079.55     367 2060.52   406.9 2060.82   434.4 2055.11
   711.8 2056.52   778.9 2051.55   809.6 2054.38  821.242049.279   830.1 2047.41
  915.52  2049.2   935.6 2052.86   956.6 2049.75   999.7 2056.03  1500.2 2053.75
  1719.4 2047.88  1756.2 2057.45  1795.1 2063.22  1838.3 2060.87  1994.8 2064.57
  2038.6 2068.16  2087.8 2076.65  2121.6  2090.7  2178.7 2094.56  2298.3 2096.33
#Mann= 15 ,-1,0
       0      .1       0     310     .06       0     470      .1       0
     530     .05       0     630      .1       0     650     .05       0
  772.37      .1       0  792.37     .05       0  821.24    .045       0
  915.52     .08       0  942.37      .1       0 1102.37    .055       0
 1582.37      .1       0 2177.79     .06       0 2277.79     .07       0
#XS Ineff= 2 , 0
          602.97 2127.18
Permanent Ineff=
       F       F
Bank Sta=821.24,915.52
XS Rating Curve= 0 ,0
Exp/Cntr=0.3,0.1

Type RM Length L Ch R = 1 ,21764   ,901.3,901.3,901.3
XS GIS Cut Line= 4
2253843.71310092615902.2325789622254027.34325091615659.653729378
2254715.64497636615122.5827371122254940.39911237614163.387474154
#Sta/Elev= 30
       0 2286.93    21.1  2284.7    60.4 2266.02   111.7 2232.35   173.1  2186.6
   220.9 2145.58   232.1 2127.47   265.9 2093.72   295.2 2059.33   330.7 2060.54
   346.5 2053.73     375 2051.29   533.6 2053.22  545.36  2048.5   553.9 2046.16
   646.4 2046.21   655.4 2048.79   665.5 2053.31   845.2 2054.15  1392.4 2050.22
  1688.2 2051.03  1700.5 2047.85  1782.7 2047.57  1827.8 2064.37  1844.3 2061.72
  1975.7 2061.86  1988.1 2065.87  2057.6 2070.01  2115.4 2087.66  2162.5 2092.41
#Mann= 8 ,-1,0
       0      .1       0  304.24     .06       0  464.24     .08       0
  504.24      .1       0  545.36    .045       0   655.4      .1       0
  754.24    .055       0 1737.29      .1       0
Bank Sta=545.36,655.4
XS Rating Curve= 0 ,0
Exp/Cntr=0.3,0.1

Type RM Length L Ch R = 1 ,20863   ,877.3,877.3,877.3
XS GIS Cut Line= 3
2254444.42243959616677.3558384362254817.07732954616128.295359339
2255191.64721501614315.080296597
#Sta/Elev= 30
       0 2117.83   203.3 2102.54   551.3 2083.97     590 2076.84   619.1 2070.65
   652.8 2053.24   670.8 2047.38  738.082047.378   850.6 2051.72   895.5 2050.81
   915.9 2047.28  1054.8 2049.88  1144.6 2046.17  1156.3 2048.78  1201.8 2045.14
  1230.8 2046.85  1252.3 2053.55  1283.5 2050.89  1422.4  2052.7  1630.2 2048.72
  1961.5 2051.37  2194.3 2047.48  2235.2 2051.16    2276 2046.78  2337.3 2048.52
  2349.6  2051.6  2374.1 2049.82  2382.2  2054.1  2439.3 2057.79  2515.1 2075.71
#Mann= 11 ,-1,0
       0      .1       0      60     .07       0     160     .06       0
     280     .05       0     590      .1       0   670.8    .045       0
  738.08      .1       0  743.58    .025       0  843.58      .1       0
 1343.58    .055       0 2153.58      .1       0
Bank Sta=670.8,738.08
XS Rating Curve= 0 ,0
Exp/Cntr=0.3,0.1

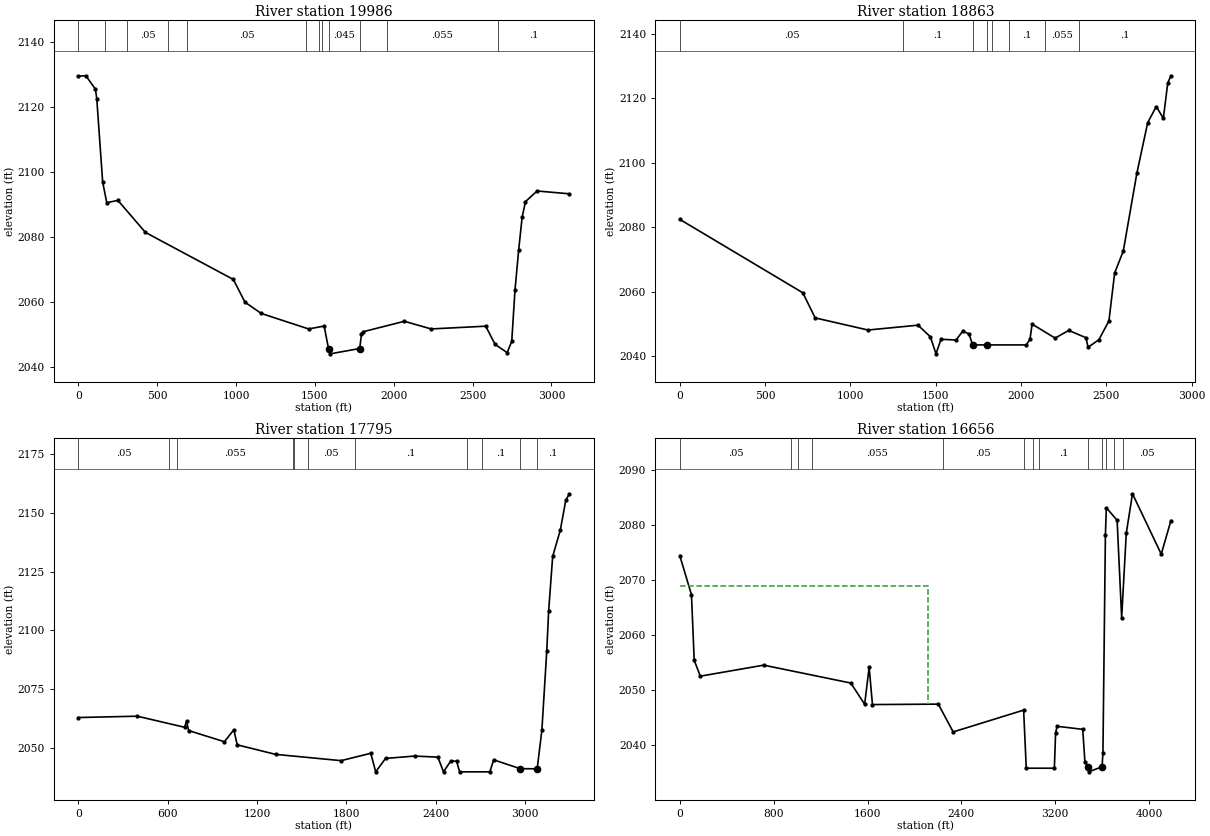
Type RM Length L Ch R = 1 ,19986   ,1122.7,1122.7,1122.7
XS GIS Cut Line= 4
2254703.38298546616965.7895935072255534.13814034616065.441005686
2255323.49404504615245.4219015492255575.59996776614234.391077748
#Sta/Elev= 30
       0 2129.54    48.4 2129.63   108.6 2125.51   117.1 2122.62   154.5 2096.93
   180.4 2090.54   251.2 2091.23   425.9 2081.37   983.2 2066.88    1057 2059.87
  1160.1 2056.41  1460.2 2051.64  1558.8 2052.53  1586.7 2045.47    1597 2043.97
 1784.122045.613  1795.3 2049.99  1807.6  2050.8  2067.4    2054  2236.9 2051.64
  2583.1 2052.49  2642.3 2046.89  2719.2 2044.34    2748 2047.82  2768.7 2063.67
  2791.8 2075.89    2814 2086.11    2835 2090.86  2908.8 2094.14  3113.7 2093.27
#Mann= 12 ,-1,0
       0      .1       0     170     .06       0     310     .05       0
     570     .06       0     690     .05       0 1445.06      .1       0
 1525.06     .05       0 1545.06     .08       0  1586.7    .045       0
 1784.12    .025       0 1955.06    .055       0 2661.71      .1       0
Bank Sta=1586.7,1784.12
XS Rating Curve= 0 ,0
Exp/Cntr=0.3,0.1

Type RM Length L Ch R = 1 ,18863   ,1067.5,1067.5,1067.5
XS GIS Cut Line= 3
2255095.63867448  616819.08581382256208.00474297616166.939885247
 2256698.6062491614655.521906873
#Sta/Elev= 30
       0 2082.39   720.9 2059.62   793.5 2051.82  1103.1 2048.06  1396.4 2049.56
  1468.8 2045.93  1501.6 2040.67    1531 2045.19  1619.3 2044.96  1657.2 2047.65
    1695 2046.89    1716 2043.44 1802.04 2043.44  2031.4 2043.44  2052.5 2045.24
  2065.1 2049.88  2199.7 2045.55  2279.6 2047.94    2380 2045.68  2393.1 2042.73
  2456.2 2045.04  2515.1 2050.91  2548.7 2065.77  2599.2 2072.55  2679.1 2096.78
  2742.2 2112.38  2792.5  2117.4    2834 2113.73  2859.9 2124.74  2878.5 2126.94
#Mann= 8 ,-1,0
       0     .05       0 1309.44      .1       0    1716    .045       0
 1802.04      .1       0 1829.44    .025       0 1929.44      .1       0
 2139.44    .055       0 2339.44      .1       0
Bank Sta=1716,1802.04
XS Rating Curve= 0 ,0
Exp/Cntr=0.3,0.1

Type RM Length L Ch R = 1 ,17795   ,1139.7,1139.7,1139.7
XS GIS Cut Line= 4
2255182.69824545617423.7509227382256434.74937827616756.939690179
2257067.27517884615210.0711646032257116.92196849 615009.66205275
#Sta/Elev= 30
       0 2063.05   395.9 2063.62   713.2 2058.92   726.8 2061.48   740.4 2057.52
   980.6 2052.78  1043.6 2057.84  1066.7 2051.46  1324.4 2047.41    1764 2044.75
  1962.8 2047.88  1996.1    2040  2062.2  2045.7  2256.7 2046.69  2413.2 2046.25
  2451.1    2040  2500.3 2044.66    2539 2044.48  2559.2    2040  2762.3    2040
  2787.5  2045.1  2965.4 2041.35 3079.782041.277  3111.3 2057.68  3144.1 2091.34
  3156.6 2108.21  3183.7 2131.41  3234.9 2142.56    3272 2155.34  3296.2 2158.02
#Mann= 11 ,-1,0
       0     .05       0     610      .1       0     660    .055       0
 1438.54     .05       0 1448.54    .055       0 1538.54     .05       0
 1858.54      .1       0 2608.54    .025       0 2708.54      .1       0
  2965.4    .045       0 3079.78      .1       0
Bank Sta=2965.4,3079.78
XS Rating Curve= 0 ,0
Exp/Cntr=0.3,0.1

Type RM Length L Ch R = 1 ,16656   ,429.8,429.8,429.8
XS GIS Cut Line= 3
2255104.21163639617838.8613669452257039.35887663616615.054010079
2258494.39384308615399.068896887
#Sta/Elev= 30
       0 2074.36    99.3 2067.28     123 2055.34   175.1 2052.47   715.5 2054.47
  1457.6 2051.22  1575.5 2047.36  1613.8 2054.08  1642.1 2047.31  2203.4 2047.39
    2330 2042.34  2930.5  2046.3  2952.8 2035.75  3192.5 2035.75    3203 2042.17
  3215.8 2043.36  3434.1 2042.81  3452.8 2036.92 3480.392036.052  3484.5 2035.09
  3599.2 2036.01  3606.4 2038.57  3627.4 2078.16  3635.6 2083.07  3727.3 2080.77
    3766 2063.06  3805.1  2078.4  3858.2  2085.6  4103.3 2074.64  4185.9 2080.73
#Mann= 13 ,-1,0
       0     .05       0     950     .08       0    1010     .06       0
    1130    .055       0    2240     .05       0 2929.65      .1       0
 3009.65     .08       0 3059.65      .1       0 3480.39    .045       0
  3599.2      .1       0 3629.65    .025       0 3699.65      .1       0
 3779.65     .05       0
#XS Ineff= 2 , 0
         2111.91  2068.9
Permanent Ineff=
       F       F
Bank Sta=3480.39,3599.2
XS Rating Curve= 0 ,0
Exp/Cntr=0.3,0.1