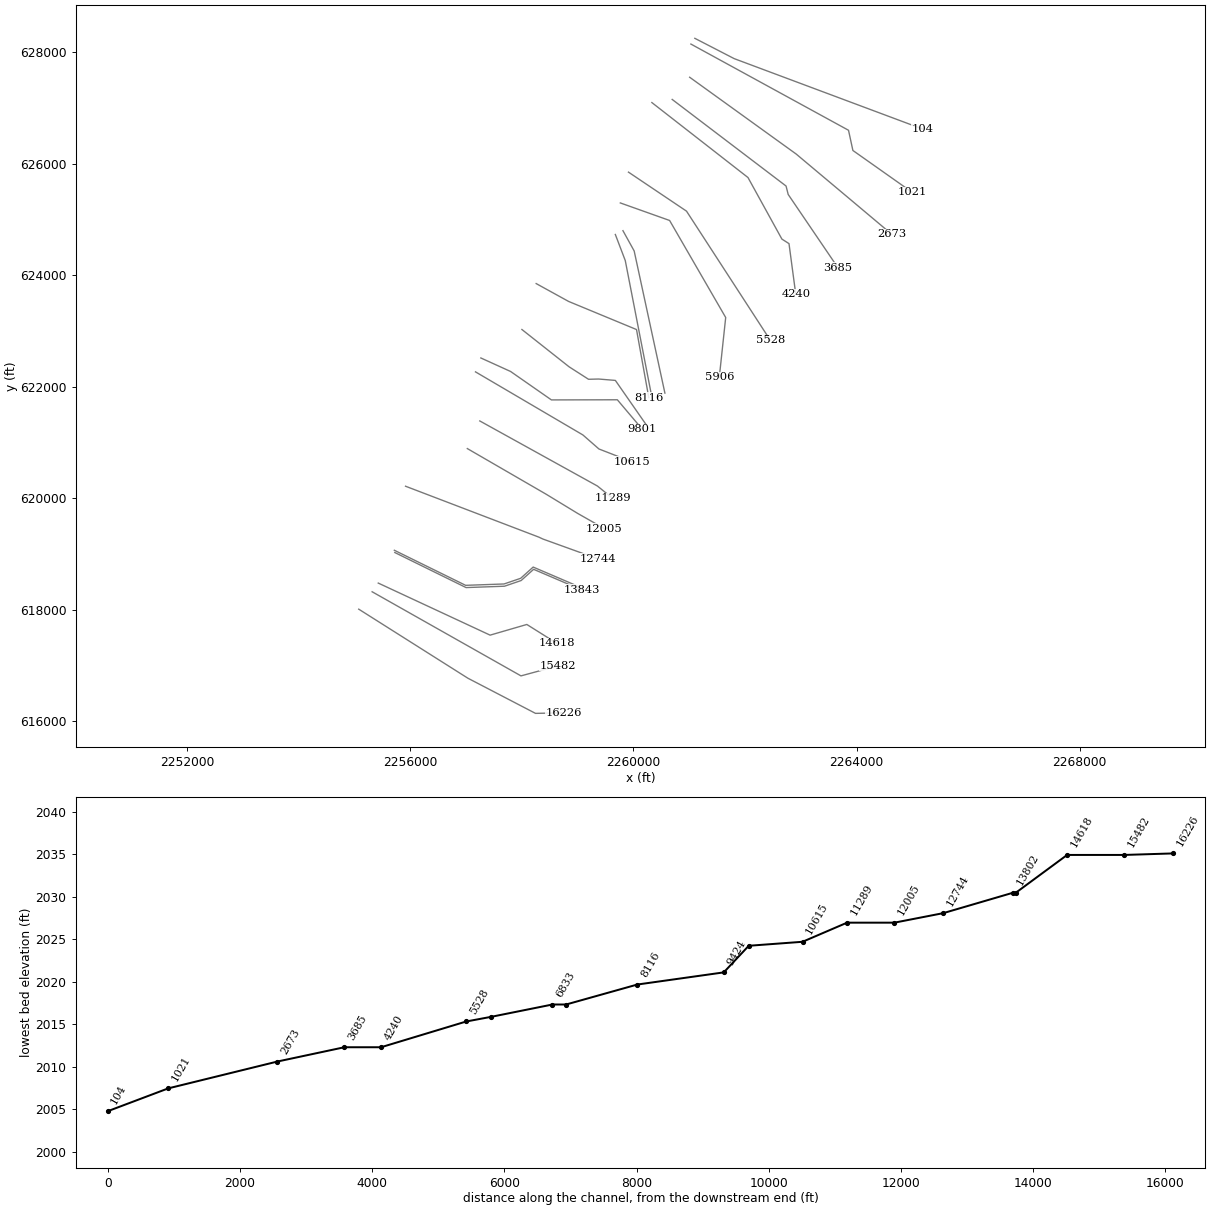
HEC-RAS study TYGVRV2.prj: TYGVRV2

--- TYGVRV2.g01 (geometry) --- (continued)

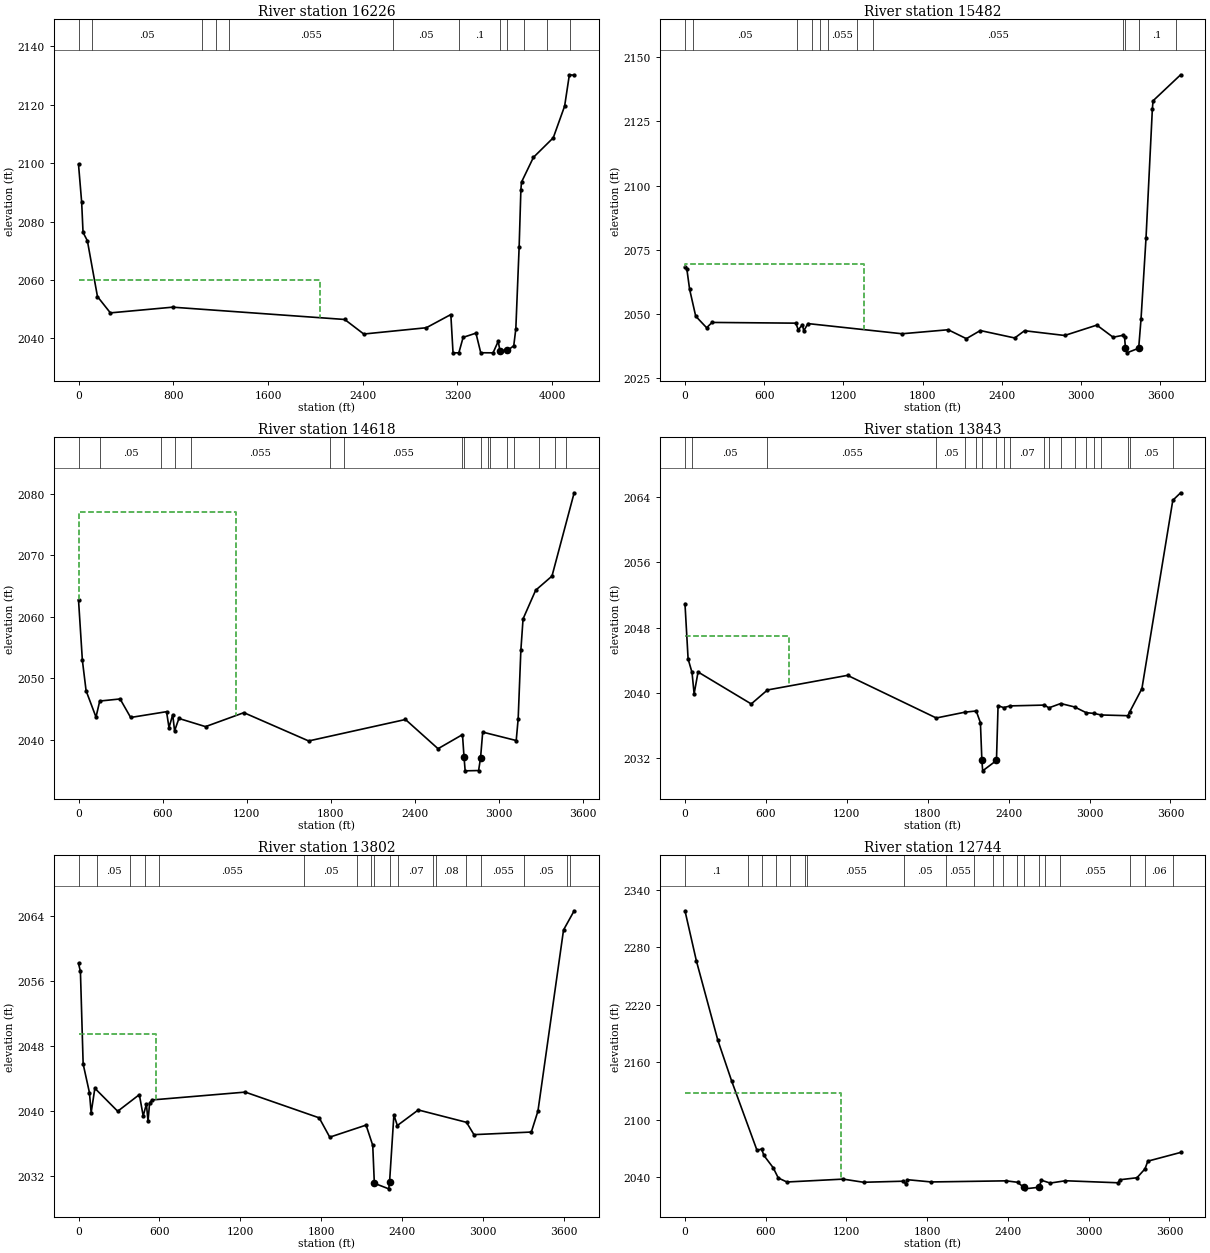
Type RM Length L Ch R = 1 ,16226   ,743.8,743.8,743.8
XS GIS Cut Line= 4
2255076.88470792 618014.546678312257032.64316058616776.504270751
2258245.44106238616145.3619375782258748.63827802616155.587449245
#Sta/Elev= 30
       0 2099.58    26.6 2086.66    38.2 2076.33    74.9 2073.45   160.1 2054.34
     269 2048.77   794.5 2050.72  2247.8 2046.51  2408.5 2041.53  2936.7 2043.68
  3143.8  2048.2  3162.4 2035.09  3211.5 2035.09  3247.6 2040.39  3355.8 2041.83
  3396.4 2035.12  3500.3 2035.09  3543.6 2039.01  3558.7 2035.89  3622.1  2035.9
  3675.1 2037.51  3692.6 2043.31  3720.6 2071.39  3735.3 2090.97  3740.6 2093.53
  3841.2    2102  4008.7  2108.7  4104.7 2119.56  4144.7 2130.27  4185.2 2130.11
#Mann= 12 ,-1,0
       0     .06       0     110     .05       0    1040     .06       0
    1160     .05       0    1270    .055       0 2654.68     .05       0
 3214.68      .1       0  3558.7    .045       0  3622.1      .1       0
 3761.87     .05       0 3951.87     .06       0 4151.87     .05       0
#XS Ineff= 2 , 0
         2042.72 2060.09
Permanent Ineff=
       F       F
Bank Sta=3558.7,3622.1
XS Rating Curve= 0 ,0
Exp/Cntr=0.3,0.1

Type RM Length L Ch R = 1 ,15482   ,864.2,864.2,864.2
XS GIS Cut Line= 3
2255317.52354805618326.3220158962257984.97826628616817.788826701
2258649.74047647616998.323825936
#Sta/Elev= 30
       0 2068.46    14.5 2067.39    35.1 2059.66    81.2 2049.19   163.9 2044.68
     205 2046.75   839.4 2046.47   857.8 2043.88   889.9 2045.87   899.1 2043.44
   931.3  2046.3  1643.6 2042.34  1992.9  2043.9  2130.7 2040.43  2236.4 2043.59
  2496.9  2040.7  2571.2 2043.52  2875.1 2041.67  3118.7 2045.71  3241.9 2040.99
  3316.5 2041.74  3328.9 2040.93 3335.48 2036.77  3346.9 2034.91 3435.59 2036.72
  3453.3 2048.01    3491 2079.45  3539.2 2129.88  3544.4 2133.06  3753.3 2143.19
#Mann= 12 ,-1,0
       0     .06       0      60     .05       0     850     .06       0
     960     .05       0    1020     .06       0    1080    .055       0
    1300     .05       0    1420    .055       0 3314.47      .1       0
 3335.48    .045       0 3435.59      .1       0 3714.47     .05       0
#XS Ineff= 2 , 0
         1355.09 2069.51
Permanent Ineff=
       F       F
Bank Sta=3335.48,3435.59
XS Rating Curve= 0 ,0
Exp/Cntr=0.3,0.1

Type RM Length L Ch R = 1 ,14618   ,774.8,774.8,774.8
XS GIS Cut Line= 4
 2255427.1117666618482.1393027052257431.68760616617548.522502205
 2258089.9627894617739.9675659452258630.08367024617400.560374143
#Sta/Elev= 30
       0 2062.72    27.6 2052.87    54.1 2047.93   124.7 2043.65   151.2 2046.26
   296.5  2046.6   371.8 2043.59   627.8 2044.53   645.4 2041.94   671.9 2044.04
   685.1 2041.41     716 2043.43   905.7  2042.1  1179.3 2044.37  1641.3 2039.77
  2331.7 2043.26    2564 2038.51  2738.3  2040.8  2749.2  2037.2  2757.4 2034.91
  2853.4 2034.96  2867.4 2037.07  2882.5 2041.21  3121.5 2039.84  3135.5 2043.39
  3154.6 2054.51  3170.3 2059.62  3260.2 2064.28  3376.6 2066.58  3534.8 2080.13
#Mann= 17 ,-1,0
       0     .06       0     150     .05       0     590     .06       0
     690     .05       0     800    .055       0    1790     .05       0
    1890    .055       0 2731.33    .025       0  2749.2    .045       0
  2867.4      .1       0 2916.88    .025       0 2936.88    .055       0
 3056.88     .05       0 3106.88      .1       0 3286.88    .055       0
 3396.88     .05       0 3476.88     .06       0
#XS Ineff= 2 , 0
         1120.58 2076.97
Permanent Ineff=
       F       F
Bank Sta=2749.2,2867.4
XS Rating Curve= 0 ,0
Exp/Cntr=0.3,0.1

Type RM Length L Ch R = 1 ,13843   ,40.9,40.9,40.9
BEGIN DESCRIPTION:
structure
END DESCRIPTION:
XS GIS Cut Line= 6
2255723.36062418619030.2057724462257000.93166095618401.463895175
2257689.60533834618425.9459496492257987.60813836618527.659480197
2258211.81694323618729.0438446262259065.44950638618363.256588496
#Sta/Elev= 30
       0 2050.93    23.2 2044.16    52.2 2042.52    67.8  2039.9      97 2042.57
   491.4 2038.66   611.7 2040.37  1205.4 2042.16  1863.5 2036.94  2075.6 2037.65
  2159.6  2037.8  2190.8 2036.37 2201.642031.757  2207.5 2030.47  2309.8 2031.74
  2321.7 2038.44  2363.5 2038.21  2411.2 2038.42  2665.9 2038.52  2698.3 2038.18
  2786.2 2038.71  2889.3 2038.29    2975 2037.59  3033.4  2037.5  3085.2 2037.31
  3284.4 2037.22  3296.5 2037.64  3388.3 2040.53  3617.5 2063.59  3675.5 2064.51
#Mann= 20 ,-1,0
       0     .06       0    52.2     .05       0   611.7    .055       0
  1863.5     .05       0  2075.6     .06       0  2159.6     .07       0
 2201.64    .045       0  2309.8     .07       0  2363.5     .06       0
  2411.2     .07       0  2665.9    .055       0  2698.3     .08       0
  2786.2     .07       0  2889.3      .1       0    2975    .055       0
  3033.4     .08       0  3085.2    .055       0  3284.4     .07       0
  3296.5     .05       0  3617.5     .08       0
#XS Ineff= 2 , 0
          771.12 2047.02
Permanent Ineff=
       F       F
Bank Sta=2201.64,2309.8
XS Rating Curve= 0 ,0
Exp/Cntr=0.3,0.1

Type RM Length L Ch R = 1 ,13802   ,1058.6,1058.6,1058.6
BEGIN DESCRIPTION:
structure
END DESCRIPTION:
XS GIS Cut Line= 6
2255715.43141053619070.556465323 2256993.0024473618441.814588052
 2257681.6761247618466.2966425252257979.67892472618568.010173072
2258203.88772959618769.3945375022259057.52029274618403.607281371
#Sta/Elev= 30
       0 2058.13    14.2 2057.14    34.4 2045.79    81.1 2042.27    93.7 2039.81
   121.2 2042.81   290.6 2039.99   451.1 2042.03   479.6 2039.41   503.5 2040.87
   515.5 2038.78   527.4 2041.02   546.6 2041.38  1236.3 2042.34  1784.8 2039.18
  1863.1 2036.81  2132.3 2038.29  2181.8 2035.81 2193.682031.151  2300.4 2030.47
  2306.4 2031.25  2338.7 2039.54  2364.3 2038.24  2519.6 2040.15  2877.3 2038.63
  2932.4 2037.12  3357.9 2037.44  3406.9 2040.01  3596.7 2062.24  3675.5 2064.59
#Mann= 18 ,-1,0
       0     .06       0     140     .05       0     380     .06       0
     490     .05       0     600    .055       0  1673.9     .05       0
  2063.9     .06       0 2168.31     .07       0 2193.68    .045       0
  2306.4      .1       0 2371.71     .07       0 2627.68      .1       0
 2647.68     .08       0 2874.52      .1       0 2984.52    .055       0
 3304.52     .05       0 3624.52     .06       0 3644.52     .08       0
#XS Ineff= 2 , 0
          577.03 2049.47
Permanent Ineff=
       F       F
Bank Sta=2193.68,2306.4
XS Rating Curve= 0 ,0
Exp/Cntr=0.3,0.1

Type RM Length L Ch R = 1 ,12744   ,738.7,738.7,738.7
XS GIS Cut Line= 5
2255916.23880943620219.2369013312258305.65021675619306.174309791
2258341.55171627 619289.30814647 2258377.4532158619272.441983149
2259361.44190486618917.204549693
#Sta/Elev= 30
       0 2317.87    85.2 2265.41     244 2183.04   346.8 2140.47   535.2 2068.22
   569.5 2069.53   586.6 2062.84   655.1 2050.15   693.6 2039.35   757.5 2035.19
  1175.8 2038.19    1327 2034.91  1618.8    2036    1640 2033.32  1652.9 2037.59
  1829.5 2035.24  2387.2  2036.4  2471.1  2034.9 2516.882029.734  2526.4 2028.06
  2631.4 2029.72  2648.7 2037.02  2713.8 2034.07  2827.3 2036.48  3218.5 2034.38
  3231.3 2037.52  3358.9 2039.62  3418.4 2048.84  3439.7 2056.92  3683.4    2066
#Mann= 20 ,-1,0
       0      .1       0     470     .06       0     570     .05       0
     680     .06       0     780    .055       0     890     .07       0
     910    .055       0    1630     .05       0    1940    .055       0
    2150     .05       0    2290      .1       0    2360     .05       0
    2470    .025       0 2516.88    .045       0  2631.4    .055       0
 2677.25      .1       0 2787.25    .055       0 3307.25     .05       0
 3417.25     .06       0 3627.25     .08       0
#XS Ineff= 2 , 0
         1158.12 2127.93
Permanent Ineff=
       F       F
Bank Sta=2516.88,2631.4
XS Rating Curve= 0 ,0
Exp/Cntr=0.3,0.1

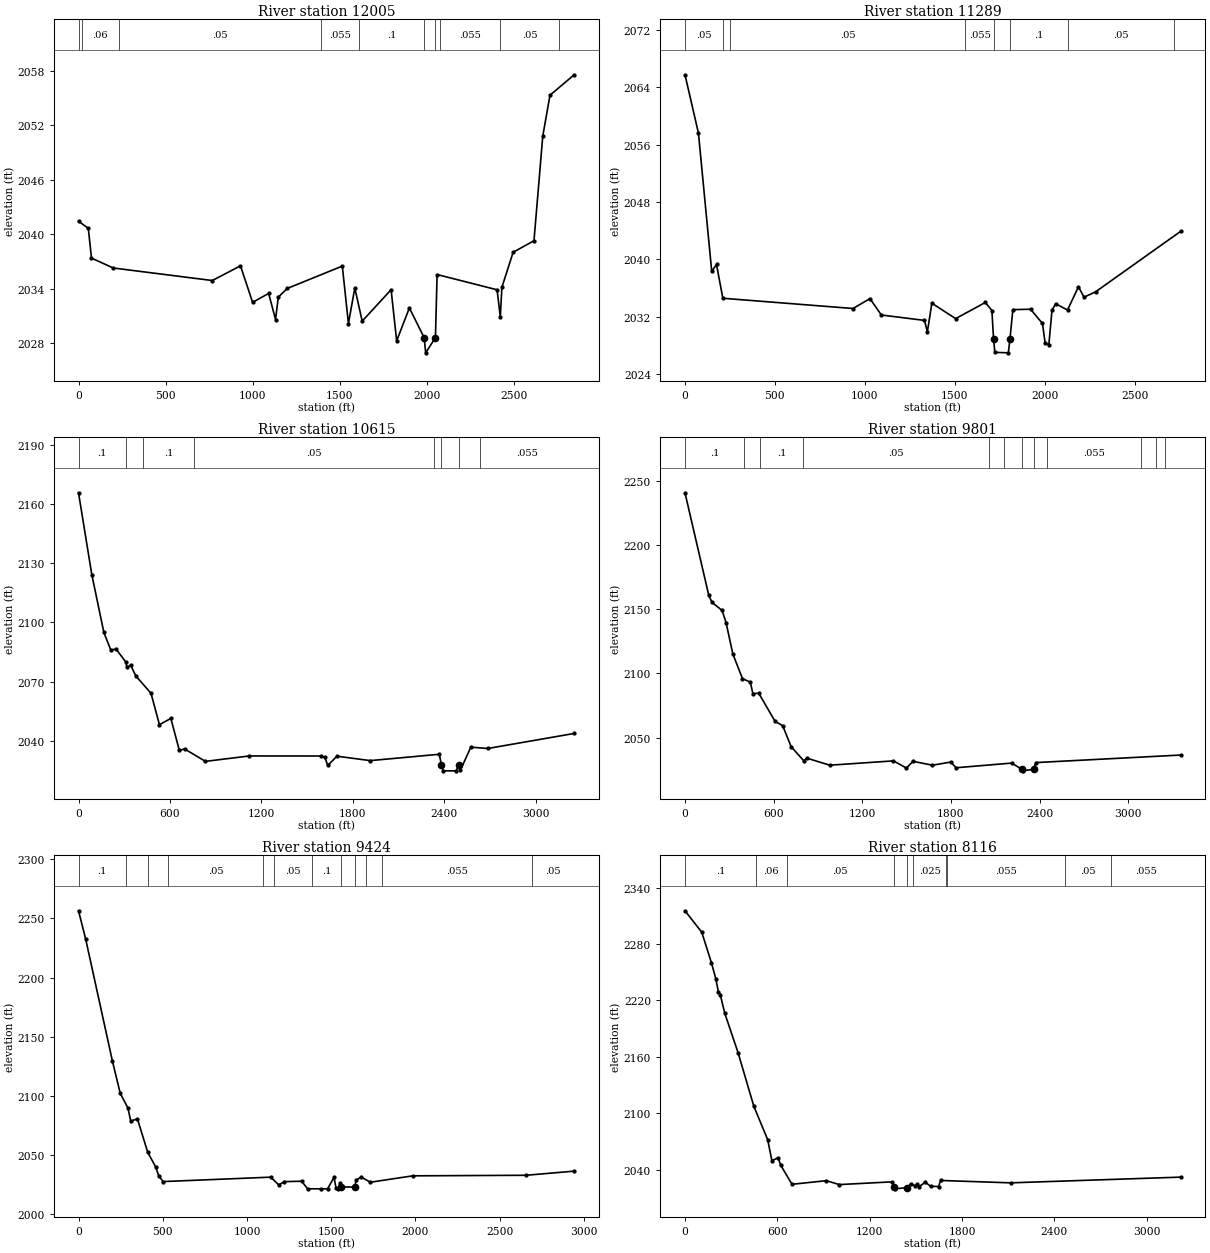
Type RM Length L Ch R = 1 ,12005   ,715.9,715.9,715.9
XS GIS Cut Line= 4
2257023.52422774620894.5519568252258436.43004879620075.860858751
2258998.83443323619733.1734050242259480.81052885619459.114971884
#Sta/Elev= 30
       0 2041.43    56.2 2040.65    74.5 2037.37   199.5 2036.28   768.2  2034.9
     930 2036.52   999.6  2032.5  1091.8 2033.48  1131.3 2030.61  1147.3 2033.08
  1198.6 2034.03  1514.7 2036.49  1549.9 2030.16  1586.4 2034.08  1628.9 2030.43
  1794.8 2033.89  1826.8 2028.26  1899.7 2031.88 1984.872028.609  1993.3 2026.94
  2049.5 2028.62  2058.9 2035.56  2403.5 2033.88  2421.9 2030.91  2431.1 2034.16
  2495.5 2038.01  2615.2 2039.28  2665.8 2050.81  2707.2  2055.3    2846 2057.55
#Mann= 10 ,-1,0
       0     .05       0      20     .06       0     230     .05       0
    1390    .055       0    1610      .1       0 1984.87    .045       0
  2049.5      .1       0 2072.96    .055       0 2421.54     .05       0
 2761.54     .07       0
Bank Sta=1984.87,2049.5
XS Rating Curve= 0 ,0
Exp/Cntr=0.3,0.1

Type RM Length L Ch R = 1 ,11289   ,673.6,673.6,673.6
XS GIS Cut Line= 3
  2257246.817697621390.1033994292259355.37791102620222.857064144
2259624.76777607 620005.17926358
#Sta/Elev= 30
       0 2065.76    74.7 2057.64   148.8  2038.3   175.3 2039.28   210.6 2034.56
   934.6 2033.13  1028.7 2034.51  1092.1 2032.22  1331.9 2031.47  1348.1 2029.89
  1372.9 2033.87  1505.1 2031.72  1670.3 2033.97  1706.9 2032.85    1716 2028.86
  1723.3 2027.01  1798.3 2026.94  1807.5 2028.93  1823.3 2032.97  1921.8 2033.03
  1988.1 2031.04  2002.8 2028.31  2023.4 2028.07  2041.1  2032.9  2061.7 2033.79
  2127.5 2032.92  2188.2 2036.17    2219 2034.71    2283 2035.45  2756.4  2043.9
#Mann= 8 ,-1,0
       0     .05       0     210     .06       0     250     .05       0
    1560    .055       0    1716    .045       0  1807.5      .1       0
    2130     .05       0 2720.08     .06       0
Bank Sta=1716,1807.5
XS Rating Curve= 0 ,0
Exp/Cntr=0.3,0.1

Type RM Length L Ch R = 1 ,10615   ,814,814,814
XS GIS Cut Line= 4
2257169.84281799622270.2602900782259094.82246626621138.996208172
2259382.51815852620887.2697661652259976.95878204620655.840240919
#Sta/Elev= 30
       0 2165.78    87.2  2124.3   166.1 2095.01   211.5 2086.03   246.9 2086.46
     310 2079.95   318.2 2077.14   341.6 2078.36   376.5 2072.81   475.8 2064.04
   531.1 2048.12   605.9 2051.28   661.5 2035.13   696.9 2035.77   833.2 2029.49
  1120.8 2032.24  1589.4 2032.22  1617.3 2031.46  1635.8 2027.43  1696.2 2032.12
  1914.2 2029.88  2367.5 2033.09 2381.982027.741    2394 2024.69  2478.8 2024.69
    2495 2027.74  2505.6 2024.89  2574.7 2036.72  2685.9 2036.03    3253 2043.66
#Mann= 8 ,-1,0
       0      .1       0     310     .06       0     420      .1       0
     760     .05       0 2332.78    .025       0 2381.98    .045       0
    2495      .1       0 2635.06    .055       0
Bank Sta=2381.98,2495
XS Rating Curve= 0 ,0
Exp/Cntr=0.3,0.1

Type RM Length L Ch R = 1 ,9801    ,377.4,377.4,377.4
XS GIS Cut Line= 5
2257265.83016426622519.6299538382257798.77794549622277.380962371
2258530.62489865621767.3830855992259712.28641211621769.819888948
2260161.40307103621238.653071195
#Sta/Elev= 30
       0 2240.46   160.6 2160.91   182.7 2155.24   251.3 2148.97   278.5 2139.31
   323.8 2115.16   389.2 2095.93     442 2093.21   459.8 2084.21   499.1 2084.61
   609.6 2062.76   661.3 2059.31   718.7 2042.97   804.9 2031.93   823.6 2034.12
   980.2 2028.61  1411.3 2031.97    1499 2026.37    1543 2031.62    1675  2028.6
    1799 2031.05    1835 2026.62    2211 2030.25  2278.8 2025.52  2286.9 2024.22
    2359 2025.43    2359 2025.44    2359 2025.45  2374.9 2030.65  3354.7  2036.5
#Mann= 12 ,-1,0
       0      .1       0     400     .06       0     510      .1       0
  795.42     .05       0 2057.44    .025       0 2157.44      .1       0
  2278.8    .045       0    2359      .1       0 2447.44    .055       0
  3089.1     .05       0  3189.1    .055       0  3249.1     .05       0
Bank Sta=2278.8,2359
XS Rating Curve= 0 ,0
Exp/Cntr(USF)=0,0
Exp/Cntr=0.3,0.1

Type RM Length L Ch R = 1 ,9424    ,1307.6,1307.6,1307.6
XS GIS Cut Line= 6
2258001.79895456623030.0726169932258846.93090461622361.522681748
2259195.86425402622137.3553371952259377.11512543 622141.93661283
2259676.81986821622116.9853589992260229.24415069621322.394667694
#Sta/Elev= 30
       0 2256.53    42.2 2232.78   201.3 2129.24   247.8  2101.9   293.7 2089.42
   309.9 2078.48   349.6 2080.32     411 2051.98     457 2039.91   477.4 2031.66
   502.9 2027.24  1140.9 2030.98  1188.7 2024.47  1221.7 2027.18  1324.8 2027.55
  1359.6 2021.14  1440.6 2021.09  1478.4 2021.09  1516.6 2030.79  1528.7 2021.78
  1540.7 2021.17  1552.7 2026.22 1560.052022.737 1638.47 2022.54  1648.7 2028.45
  1676.7 2031.07  1732.9 2026.69  1983.9  2032.1  2656.2 2032.57  2942.1 2036.07
#Mann= 12 ,-1,0
       0      .1       0     280     .06       0     410      .1       0
     530     .05       0 1097.59      .1       0 1157.59     .05       0
 1387.59      .1       0 1560.05    .045       0 1638.47      .1       0
 1703.64     .05       0 1803.64    .055       0 2694.38     .05       0
Bank Sta=1560.05,1638.47
XS Rating Curve= 0 ,0
Exp/Cntr=0.3,0.1

Type RM Length L Ch R = 1 ,8116    ,1077.4,1077.4,1077.4
XS GIS Cut Line= 4
2258257.45464484623853.8096182942258839.07750942623533.408332872
2260055.88581301623029.3250887582260275.60262337 621809.26353193
#Sta/Elev= 30
       0  2315.4   109.1 2292.58   172.1 2259.96   200.3  2243.2   216.8 2229.39
   229.2 2226.21   258.8 2206.29   345.6 2164.15   447.1 2107.62   537.4 2071.94
   564.8  2049.5   605.9 2052.81   620.8 2045.11   695.5  2024.5   919.1 2028.34
  1002.9 2024.18    1345  2027.1    1358 2021.17  1366.6 2019.66  1442.6 2020.97
  1466.2 2024.84  1497.8 2022.79  1509.5  2025.2  1522.5 2022.12  1561.5 2026.68
  1595.7 2022.38  1648.1  2022.1    1661 2028.58  2115.8 2026.04  3220.8 2032.11
#Mann= 10 ,-1,0
       0      .1       0     460     .06       0     660     .05       0
    1358    .045       0  1442.6     .05       0 1484.03    .025       0
 1694.03      .1       0 1704.03    .055       0 2471.12     .05       0
 2771.12    .055       0
Bank Sta=1358,1442.6
XS Rating Curve= 0 ,0
Exp/Cntr=0.3,0.1

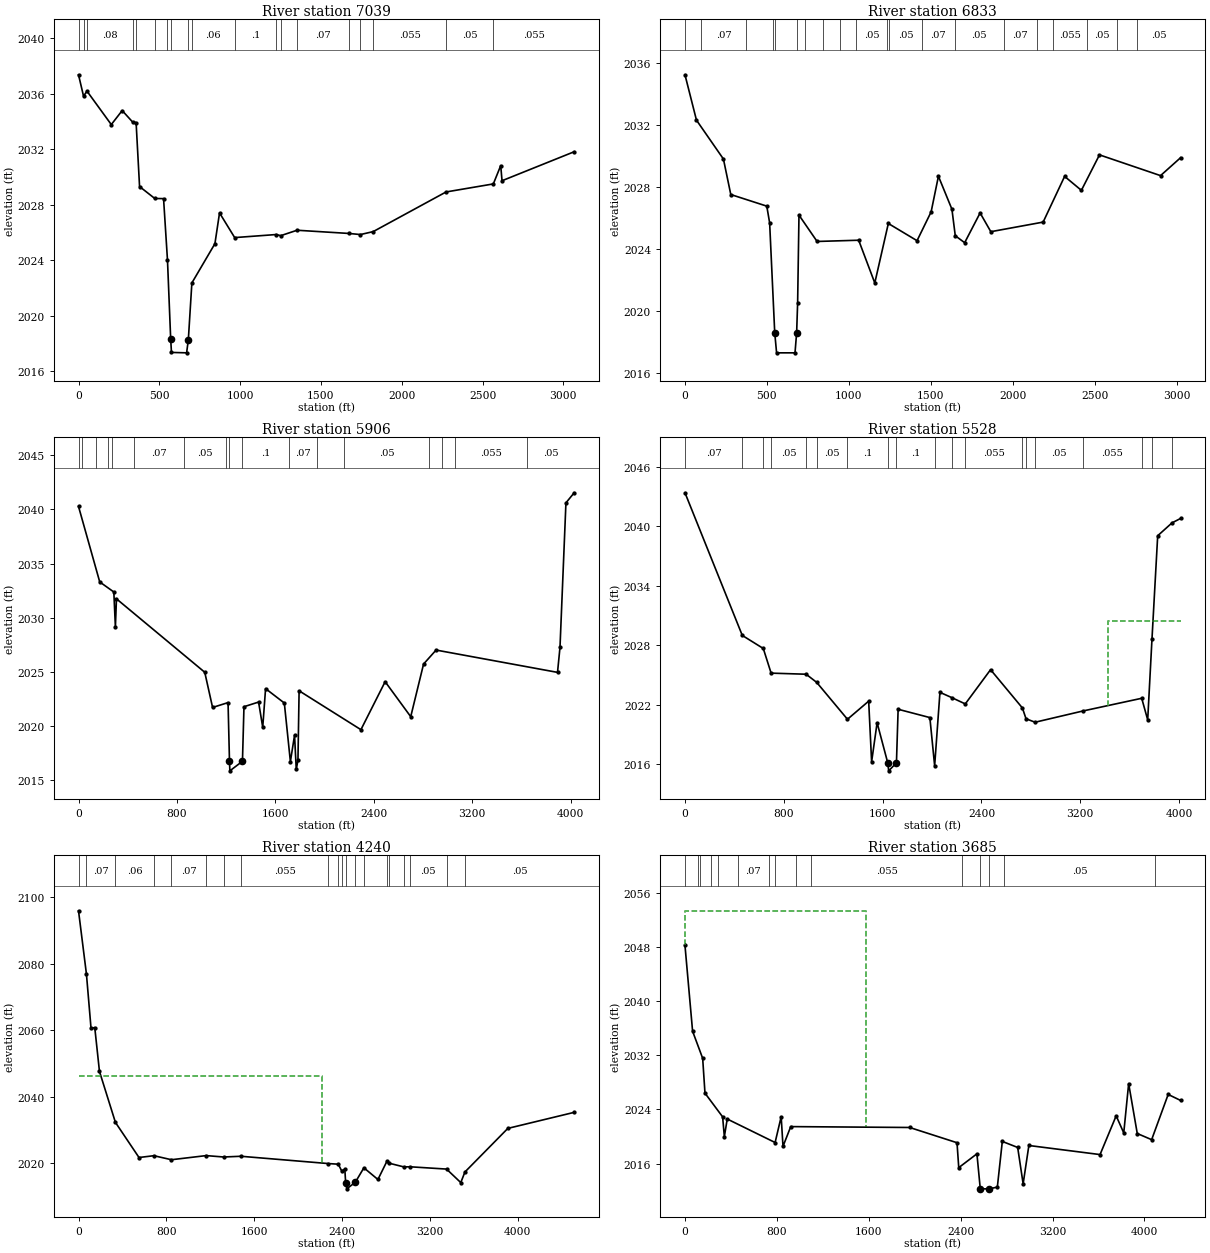
Type RM Length L Ch R = 1 ,7039    ,205.9,205.9,205.9
BEGIN DESCRIPTION:
structure
END DESCRIPTION:
XS GIS Cut Line= 3
2259676.46706756624734.269806465 2259854.3821948624266.810716556
2260344.52921728 621747.03647558
#Sta/Elev= 30
       0 2037.36    31.1 2035.82    52.5 2036.18   202.8 2033.77   270.3 2034.78
     335 2033.95   356.4 2033.91   377.8  2029.3     472 2028.44   526.3 2028.43
   550.6 2023.99   570.42018.299   575.2 2017.34   668.9 2017.31  679.532018.238
   701.5 2022.35   844.1 2025.18   872.7  2027.4   966.4 2025.62  1222.9 2025.84
  1251.6 2025.76  1352.5 2026.15  1671.4 2025.92  1744.7 2025.84  1823.3 2026.05
  2274.4 2028.91    2567 2029.49  2612.7 2030.81  2620.8 2029.72  3067.2 2031.81
#Mann= 19 ,-1,0
       0     .05       0    31.1     .07       0    52.5     .08       0
     335      .1       0   356.4     .08       0     472     .06       0
   550.6      .1       0   570.4    .045       0  679.53      .1       0
   701.5     .06       0   966.4      .1       0  1222.9     .06       0
  1251.6     .05       0  1352.5     .07       0  1671.4    .055       0
  1744.7     .06       0  1823.3    .055       0  2274.4     .05       0
    2567    .055       0
Bank Sta=570.4,679.53
XS Rating Curve= 0 ,0
Exp/Cntr=0.3,0.1

Type RM Length L Ch R = 1 ,6833    ,926.9,926.9,926.9
BEGIN DESCRIPTION:
structure
END DESCRIPTION:
XS GIS Cut Line= 3
2259812.81770703624802.4751325672260013.77070571624439.364048594
2260564.85800944621889.360744266
#Sta/Elev= 30
       0 2035.26    70.1 2032.33   234.6 2029.82   279.5 2027.53   499.1 2026.78
   516.5  2025.7  547.542018.606   558.9 2017.31   671.3 2017.31   681.3 2018.62
   687.3 2020.55   695.5  2026.2     806  2024.5  1059.7 2024.58    1158 2021.82
  1240.6 2025.66  1415.8 2024.55  1501.7 2026.41  1546.2 2028.71  1628.6 2026.58
    1649 2024.87  1706.3 2024.42  1800.5 2026.34  1865.9 2025.13  2185.1 2025.75
  2316.1  2028.7  2418.4  2027.8  2528.8 2030.09  2901.3 2028.75  3023.9 2029.91
#Mann= 20 ,-1,0
       0     .06       0     100     .07       0     370     .05       0
  535.01    .025       0  547.54    .045       0   681.3    .025       0
  735.01     .08       0  845.01     .07       0  945.01    .055       0
 1045.01     .05       0 1235.01     .07       0 1245.01     .05       0
 1445.01     .07       0 1645.01     .05       0 1945.01     .07       0
 2145.01     .05       0 2245.01    .055       0 2455.01     .05       0
 2635.01    .055       0 2755.01     .05       0
Bank Sta=547.54,681.3
XS Rating Curve= 0 ,0
Exp/Cntr=0.3,0.1

Type RM Length L Ch R = 1 ,5906    ,378.1,378.1,378.1
XS GIS Cut Line= 4
2259765.73934709625300.1322080032260649.26980829624985.452271013
2261654.43127555623245.2970606412261539.36100743622170.625035038
#Sta/Elev= 30
       0 2040.27   172.4  2033.3   287.1 2032.37   299.8 2029.13   308.3 2031.74
    1026 2024.96  1089.6 2021.71  1215.4 2022.161226.9572016.768  1230.1 2015.86
 1332.462016.744  1344.7 2021.78  1463.5 2022.21  1497.2 2019.88  1520.3 2023.45
  1672.7 2022.12    1722 2016.71  1755.8 2019.15  1769.7    2016  1783.5 2016.84
  1792.8 2023.25  2295.2 2019.66  2492.1 2024.09    2700 2020.86  2804.4 2025.72
  2906.1 2027.01    3893 2024.95  3913.1 2027.26  3961.4  2040.6  4028.3 2041.53
#Mann= 17 ,-1,0
       0     .07       0      30     .08       0     140     .06       0
     240     .05       0     270     .06       0     450     .07       0
     860     .05       0  1197.9      .1       01226.957    .045       0
 1332.46      .1       0  1707.9     .07       0  1937.9    .055       0
  2157.9     .05       0  2847.9     .06       0  2957.5     .05       0
  3057.5    .055       0  3647.5     .05       0
Bank Sta=1226.957,1332.46
XS Rating Curve= 0 ,0
Exp/Cntr=0.3,0.1

Type RM Length L Ch R = 1 ,5528    ,1288.3,1288.3,1288.3
XS GIS Cut Line= 3
2259911.77653838625852.5829497072260952.23586861625152.645197889
2262453.24185655622838.605859519
#Sta/Elev= 30
       0  2043.4   463.9 2028.99   633.9 2027.67   697.3 2025.18   980.7 2025.07
  1065.9 2024.25  1315.3 2020.52    1487 2022.35  1510.8 2016.22  1555.2 2020.17
  1641.1 2016.13  1649.1 2015.311711.8142016.123  1725.4 2021.53  1982.3 2020.69
    2021 2015.82  2063.9 2023.24  2159.2 2022.71  2268.9 2022.07  2473.7 2025.53
  2731.4 2021.66  2760.7 2020.57  2834.2 2020.22  3222.4 2021.36  3697.2 2022.64
  3745.6 2020.46  3780.3 2028.63  3826.5 2039.06  3942.4 2040.36  4012.2 2040.81
#Mann= 19 ,-1,0
       0     .07       0   463.9     .06       0   633.9     .07       0
   697.3     .05       0   980.7     .06       0  1065.9     .05       0
  1315.3      .1       0  1641.1    .045       01711.814      .1       0
    2021     .07       0  2159.2    .055       0  2268.9    .055       0
  2731.4     .05       0  2760.7    .055       0  2834.2     .05       0
  3222.4    .055       0  3697.2     .05       0  3780.3      .1       0
  3942.4     .05       0
#XS Ineff= 2 , 0
                         3422.38         2030.47
Permanent Ineff=
       F       F
Bank Sta=1641.1,1711.814
XS Rating Curve= 0 ,0
Exp/Cntr=0.3,0.1

Type RM Length L Ch R = 1 ,4240    ,554.8,554.8,554.8
XS GIS Cut Line= 5
 2260331.2036399627100.0648492752262053.73822923625755.903925515
2262661.72574107624651.8303143512262789.05532285624570.558842319
2262910.44774453623660.787581234
#Sta/Elev= 30
       0 2095.86    72.3 2076.81   113.9 2060.57   148.1 2060.74   190.8 2047.58
   336.1 2032.26   550.9  2021.7   686.7 2022.24   846.3 2021.03  1162.6 2022.27
  1322.2 2021.85    1479 2022.07  2274.1 2019.88  2365.4 2019.69  2397.3 2017.65
  2425.5 2018.21  2433.1    2014  2443.8 2012.28  2521.4 2014.28    2599  2018.6
  2726.9 2015.09  2809.1 2020.59  2827.3    2020  2963.2 2018.87    3019 2018.91
  3351.9 2018.22  3481.5 2014.16  3519.4 2017.35  3910.1 2030.45  4514.2 2035.27
#Mann= 20 ,-1,0
       0     .06       0    72.3     .07       0   336.1     .06       0
   686.7     .08       0   846.3     .07       0  1162.6     .05       0
  1322.2     .07       0    1479    .055       0  2274.1     .05       0
  2365.4    .025       0  2397.3      .1       0  2433.1    .045       0
  2521.4    .025       0    2599      .1       0  2809.1    .025       0
  2827.3     .05       0  2963.2    .055       0    3019     .05       0
  3351.9    .055       0  3519.4     .05       0
#XS Ineff= 2 , 0
         2220.22  2046.1
Permanent Ineff=
       F       F
Bank Sta=2433.1,2521.4
XS Rating Curve= 0 ,0
Exp/Cntr=0.3,0.1

Type RM Length L Ch R = 1 ,3685    ,1012,1012,1012
XS GIS Cut Line= 4
2260695.40556961627156.3490958242262736.34391692625603.307470304
2262774.55084678625452.2181753162263670.33555345 624132.77732974
#Sta/Elev= 30
       0 2048.22    66.3 2035.55   154.1 2031.55   174.1 2026.41   327.7 2022.91
   342.8 2019.99   367.9 2022.59   784.7 2019.12   837.5 2022.93   853.4 2018.55
   920.8 2021.47  1956.2 2021.34  2368.4 2019.09  2383.5 2015.41  2541.7 2017.45
    2571 2012.28 2649.92 2012.28  2719.5 2012.54  2762.8 2019.28  2896.6 2018.39
  2944.1 2013.02    2994 2018.68  3613.7 2017.34    3754 2023.06  3820.1 2020.54
  3862.8 2027.82  3937.7 2020.45  4062.9 2019.54  4206.9 2026.22  4315.3 2025.33
#Mann= 15, -1 ,  0
       0    0.07       0     110    0.08       0     130    0.07       0
     230    0.08       0     290     0.1       0     460    0.07       0
     730    0.06       0     780    0.07       0     970    0.05       0
    1100   0.055       0    2410     0.1       0    2571   0.045       0
 2649.92     0.1       0 2780.48    0.05       0 4090.48    0.06       0
#XS Ineff= 2 , 0
         1574.01 2053.34
Permanent Ineff=
       F       F
Bank Sta=2571,2649.92
XS Rating Curve= 0 ,0
Exp/Cntr=0.3,0.1

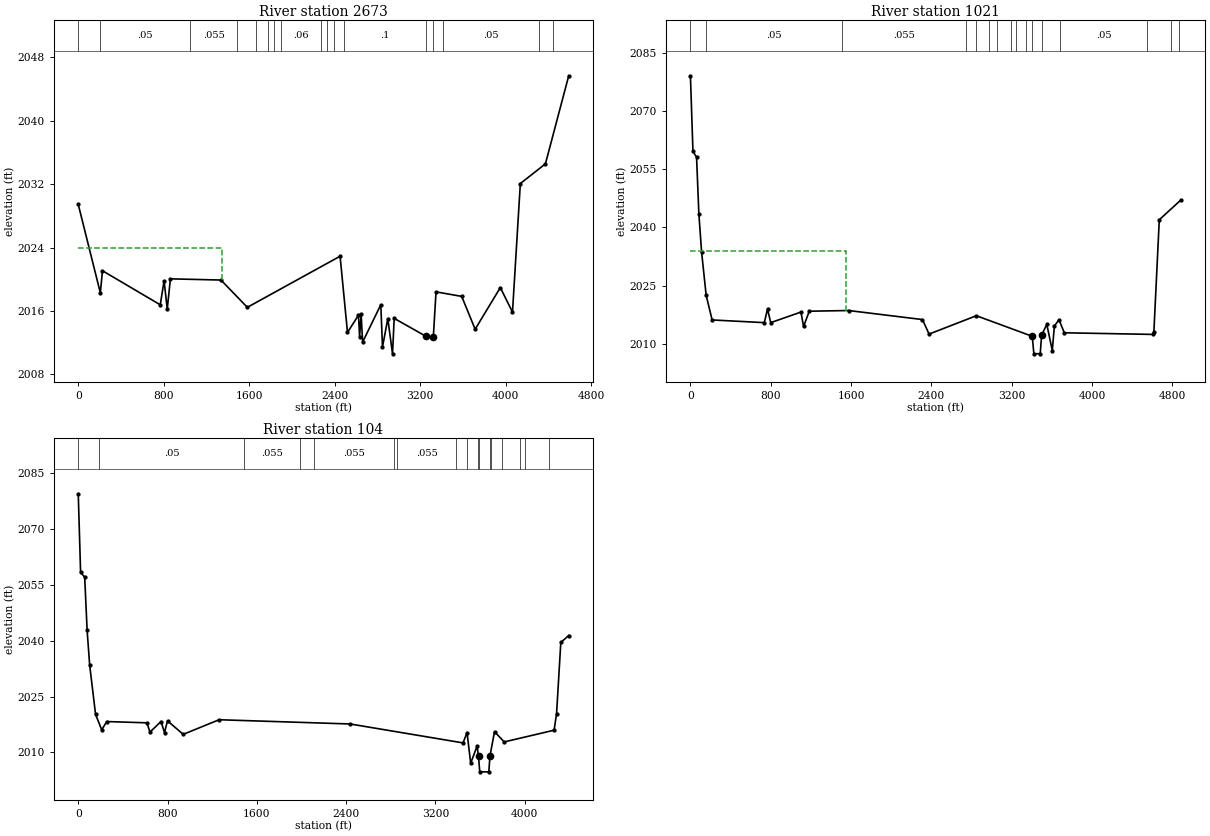
Type RM Length L Ch R = 1 ,2673    ,1652.4,1652.4,1652.4
XS GIS Cut Line= 4
 2261008.5835774627554.4017275672262918.94814851626176.155246924
2263861.64790076625384.8146685992264631.21497217624737.854528994
#Sta/Elev= 30
       0 2029.43   206.7 2018.29   226.9 2021.07   767.8 2016.78   803.5 2019.81
   833.1 2016.23   862.7 2020.05  1336.2  2019.9  1582.8 2016.46  2451.3  2022.9
  2520.5  2013.3  2623.6 2015.47    2634 2012.75  2648.2 2015.59  2662.4 2012.08
  2832.5 2016.79  2848.2 2011.45  2898.1 2015.04  2942.2  2010.6  2957.8 2015.07
 3257.242012.793    33242012.691  3349.5 2018.41  3589.8 2017.84  3715.7  2013.7
  3951.4 2018.95  4065.3 2015.86  4138.8 2032.06  4373.6 2034.54  4591.8 2045.64
#Mann= 17, -1 ,  0
       0    0.06       0     200    0.05       0    1050   0.055       0
    1490    0.06       0    1660   0.055       0    1780    0.05       0
    1830    0.07       0    1900    0.06       0    2270    0.07       0
    2330   0.055       0 2395.64    0.07       0 2485.64     0.1       0
 3257.24   0.045       0    3324     0.1       0 3415.64    0.05       0
 4316.46    0.06       0 4446.46    0.05       0
#XS Ineff= 2 , 0
         1350.18 2023.91
Permanent Ineff=
       F       F
Bank Sta=3257.24,3324
XS Rating Curve= 0 ,0
Exp/Cntr=0.3,0.1

Type RM Length L Ch R = 1 ,1021    ,916.5,916.5,916.5
XS GIS Cut Line= 4
2261030.40896184 628149.700405752263855.78380887626603.430059872
  2263934.231439626241.1094786822264991.97318586625493.956109021
#Sta/Elev= 30
       0 2079.01    25.3 2059.53    61.3 2058.06    84.1 2043.51   111.4  2033.6
     157 2022.48   216.3 2016.16   736.1 2015.47   768.1 2018.97     800 2015.47
  1100.9 2018.19  1127.4 2014.48  1184.2 2018.41  1575.4 2018.59  2312.1 2016.26
  2377.7 2012.52  2848.5 2017.25  3405.82011.949  3421.8 2007.44  3485.1 2007.49
 3498.822012.213  3550.5 2015.04  3605.3 2008.28  3626.1  2014.6  3672.3 2016.22
  3724.9 2012.86    4606 2012.44  4617.5 2013.18  4671.3 2041.95  4886.5 2047.04
#Mann= 16 ,-1,0
       0     .06       0     160     .05       0    1510    .055       0
    2750     .05       0    2850    .055       0    2970     .05       0
    3050    .055       0    3190     .05       0 3240.82    .055       0
 3340.82     .05       0  3405.8    .045       0 3498.82      .1       0
 3681.54     .05       0 4551.54      .1       0 4791.54     .05       0
 4871.54     .06       0
#XS Ineff= 2 , 0
         1548.74 2033.79
Permanent Ineff=
       F       F
Bank Sta=3405.8,3498.82
XS Rating Curve= 0 ,0
Exp/Cntr=0.3,0.1

Type RM Length L Ch R = 1 ,104     ,,,
XS GIS Cut Line= 4
2261101.51702036628252.2341245462261807.54558527627887.861153738
2265074.74260172626666.5620066942265179.39915401626629.472713114
#Sta/Elev= 30
       0 2079.52      21 2058.38    57.7  2057.1    79.5 2042.76   102.2 2033.47
   154.9 2020.22   210.1 2016.04   255.1 2018.27   615.2 2017.93   642.2 2015.44
   741.2 2018.28   772.7 2015.31   799.5 2018.46   940.4 2014.83  1261.6 2018.76
  2435.2 2017.62  3447.1 2012.53  3482.7 2015.31  3515.4 2007.06  3572.9 2011.69
  3585.3  2008.9  3596.5 2004.75  3677.7 2004.75 3688.052009.014  3728.9 2015.57
  3815.3 2012.79  4262.7 2015.95  4284.7 2020.42  4322.6 2039.53  4393.5 2041.41
#Mann= 17 ,-1,0
       0     .06       0     190     .05       0 1484.51    .055       0
 1984.51     .07       0 2114.51    .055       0 2824.51     .07       0
 2854.51    .055       0 3384.51      .1       0 3484.51     .05       0
 3584.51      .1       0  3585.3    .045       0 3688.05     .05       0
 3694.51      .1       0 3794.51     .05       0 3954.51     .08       0
 4004.51     .05       0 4214.51      .1       0
Bank Sta=3585.3,3688.05
XS Rating Curve= 0 ,0
Exp/Cntr(USF)=0,0
Exp/Cntr=0.3,0.1
LCMann Table=0

Chan Stop Cuts=-1
Use User Specified Reach Order=0
Composite Channel Slope=5